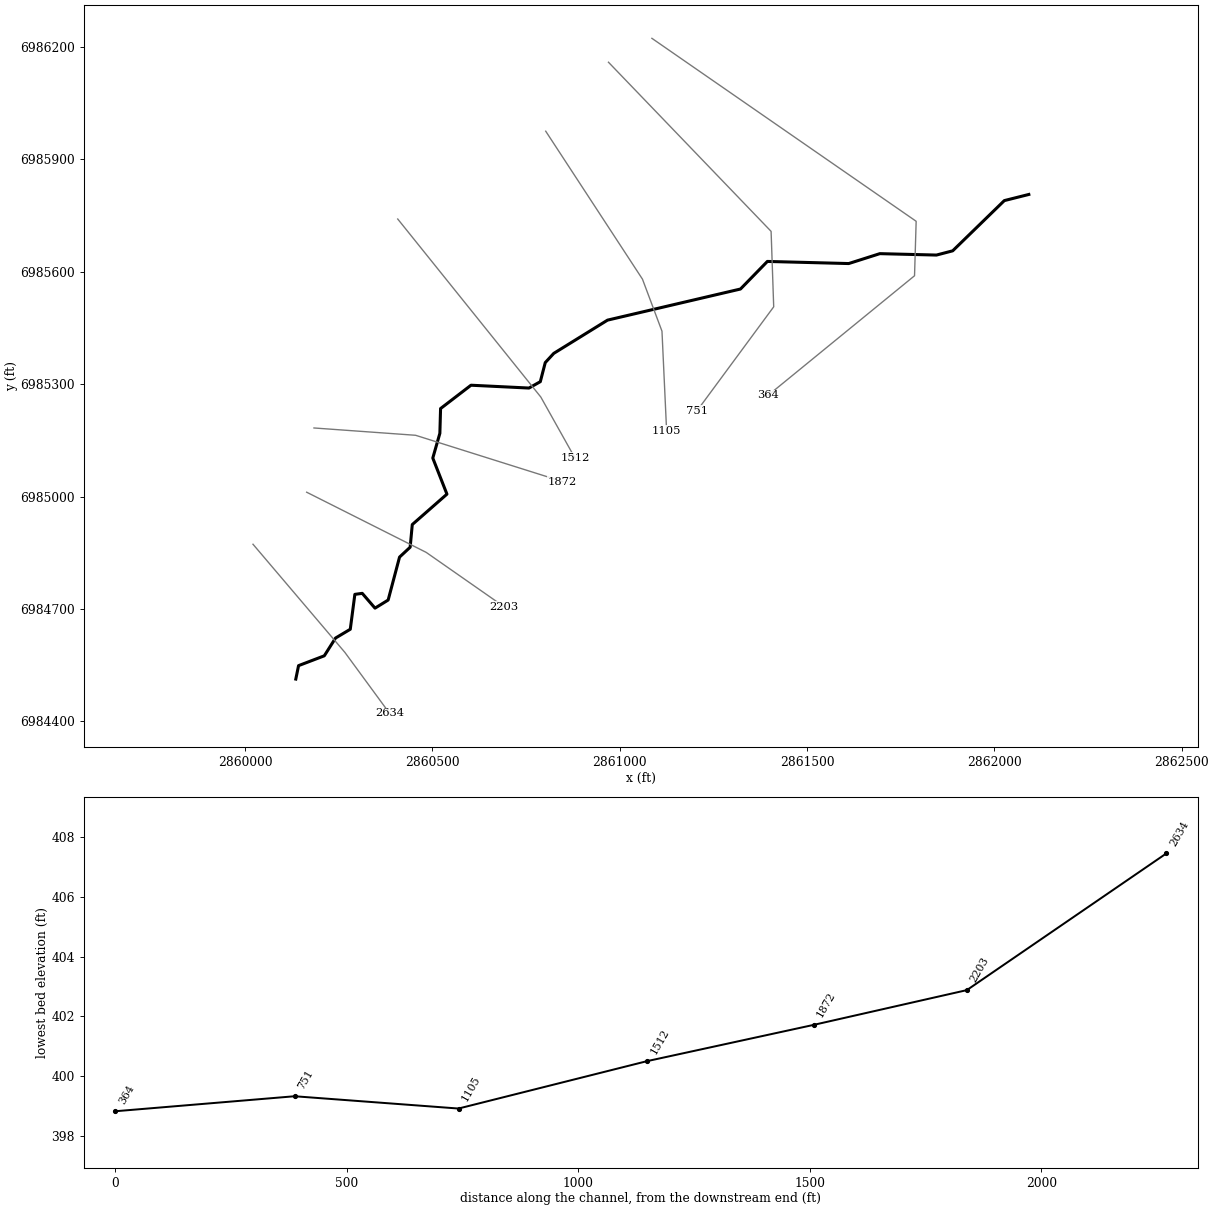
--- UNT 064 in Running Cr Watershed.prj (project) ---

Proj Title=UNT 064 in Running Cr Watershed Base Level Engineering
Current Plan=p01
Default Exp/Contr=0.3,0.1
English Units
Geom File=g01
Flow File=f01
Plan File=p01
BEGIN DESCRIPTION:
UNT 064 in Running Cr Watershed
END DESCRIPTION:

--- UNT 064 in Running Cr Watershed.p01 (plan) ---

Plan Title=Multiple Run
Short Identifier=Multiple
Geom File=g01
Flow File=f01
Subcritical Flow
K Sum by GR= 0
Std Step Tol= 0.01
Critical Tol= 0.01
Num of Std Step Trials= 20
Max Error Tol= 0.3
Flow Tol Ratio= 0.001
Split Flow NTrial= 30
Split Flow Tol= 0.02
Split Flow Ratio= 0.02
Log Output Level= 0
Friction Slope Method= 1
Unsteady Friction Slope Method= 2
Unsteady Bridges Friction Slope Method= 1
Parabolic Critical Depth
Global Vel Dist=  1 , 1 , 1
Global Log Level= 0
CheckData=True
Encroach Param= -1, 0, 0, 0
BEGIN DESCRIPTION:
Multiple Run
END DESCRIPTION:

--- UNT 064 in Running Cr Watershed.f01 (steady flow) ---

Flow Title=Multiple
Number of Profiles=7
Profile Names=10-year,25-year,50-year,1pct_min,100-year,1pct_plu,500-year
River Rch & RM= UNT 064 in Runni,Reach-1,2634
     526     702     844     505    1007    2009    1436
Boundary for River Rch & Prof#=UNT 064 in Runni,Reach-1,1
Up Type=0
Dn Type=3
Dn Slope=0.005
Boundary for River Rch & Prof#=UNT 064 in Runni,Reach-1,2
Up Type=0
Dn Type=3
Dn Slope=0.005
Boundary for River Rch & Prof#=UNT 064 in Runni,Reach-1,3
Up Type=0
Dn Type=3
Dn Slope=0.005
Boundary for River Rch & Prof#=UNT 064 in Runni,Reach-1,4
Up Type=0
Dn Type=3
Dn Slope=0.005
Boundary for River Rch & Prof#=UNT 064 in Runni,Reach-1,5
Up Type=0
Dn Type=3
Dn Slope=0.005
Boundary for River Rch & Prof#=UNT 064 in Runni,Reach-1,6
Up Type=0
Dn Type=3
Dn Slope=0.005
Boundary for River Rch & Prof#=UNT 064 in Runni,Reach-1,7
Up Type=0
Dn Type=3
Dn Slope=0.005

--- UNT 064 in Running Cr Watershed.g01 (geometry) ---

Geom Title=Existing Conditions

River Reach=UNT 064 in Runni,Reach-1
Reach XY= 30
      2860135.29      6984512.75      2860142.68      6984548.61
      2860211.38      6984574.85      2860241.33      6984622.21
      2860280.71      6984645.70      2860292.93      6984738.86
      2860312.68      6984741.52      2860346.73      6984702.03
      2860381.79      6984723.68      2860412.20      6984838.27
      2860440.52      6984864.70      2860446.18      6984925.12
      2860538.69      6985006.29      2860500.93      6985102.58
      2860519.81      6985168.65      2860521.70      6985234.73
      2860602.88      6985297.03      2860757.68      6985289.48
      2860787.89      6985306.47      2860801.11      6985357.44
      2860823.76      6985381.99      2860967.24      6985470.72
      2861322.17      6985553.79      2861393.91      6985627.41
      2861611.02      6985621.75      2861694.08      6985648.18
      2861845.12      6985644.41      2861888.54      6985655.73
      2862026.35      6985789.77      2862091.73      6985806.19

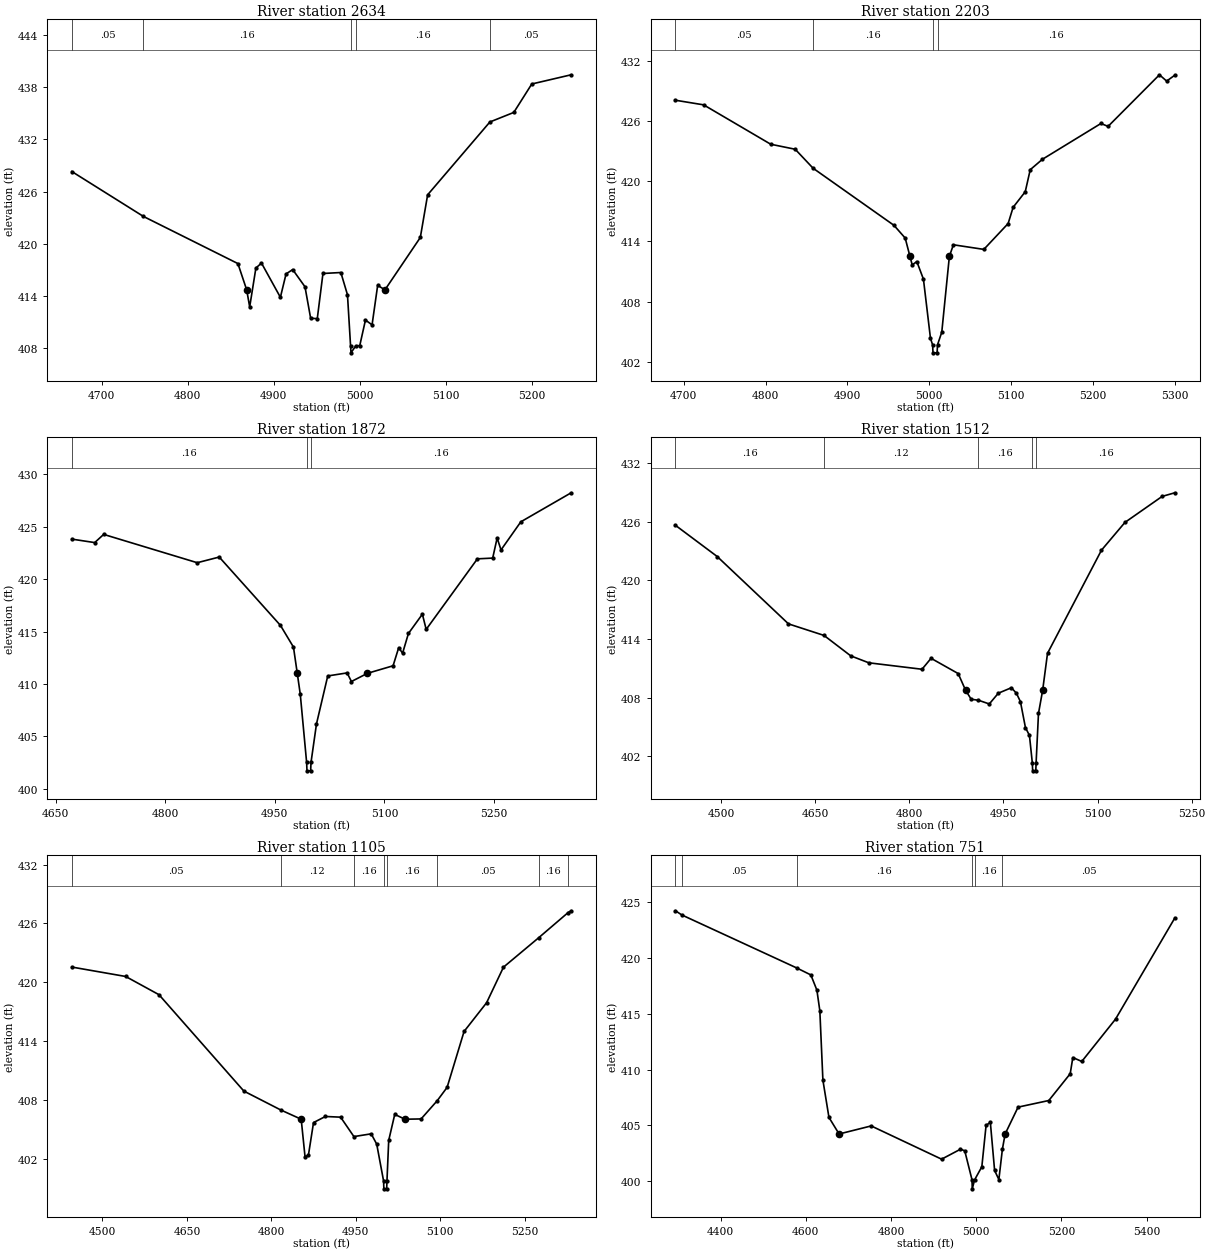
Type RM Length L Ch R = 1,2634,431,431,431
BEGIN DESCRIPTION:
UNT 064 in Running Cr Watershed 6.0
END DESCRIPTION:
XS GIS Cut Line= 3
      2860021.06      6984872.60      2860266.28      6984583.97
      2860385.65      6984421.19
#Sta/Elev= 30
  4665.3  428.30  4748.6  423.13  4858.4  417.71  4868.6  414.69  4872.1  412.72
  4879.3  417.19  4885.8  417.77  4907.8  413.83  4914.4  416.52  4922.1  417.02
  4936.4  415.04  4943.0  411.41  4950.7  411.38  4957.3  416.57  4978.1  416.68
  4985.8  414.12  4989.4  408.24  4989.9  407.44  4995.4  408.24  5000.1  408.28
  5006.7  411.21  5014.4  410.66  5020.9  415.20  5029.4  414.69  5070.5  420.71
  5079.0  425.62  5151.4  434.00  5179.2  435.10  5200.1  438.37  5245.9  439.43
#Mann=5,-1,0
  4665.3    0.05       0  4748.6    0.16       0  4989.4    0.07       0
  4995.4    0.16       0  5151.4    0.05       0
Bank Sta=4868.6,5029.4
Exp/Cntr=0.3,0.1

Type RM Length L Ch R = 1,2203,331,331,331
BEGIN DESCRIPTION:
UNT 064 in Running Cr Watershed 5.0
END DESCRIPTION:
XS GIS Cut Line= 3
      2860164.31      6985011.47      2860483.29      6984850.90
      2860690.83      6984706.06
#Sta/Elev= 30
  4690.0  428.08  4724.4  427.62  4806.4  423.69  4836.3  423.19  4858.1  421.30
  4957.0  415.60  4970.7  414.33  4976.5  412.51  4979.3  411.65  4984.9  411.99
  4993.0  410.23  5001.6  404.32  5004.2  403.68  5004.7  402.88  5009.7  402.88
  5010.2  403.68  5015.4  404.94  5024.7  412.51  5029.6  413.66  5066.8  413.20
  5096.5  415.78  5102.6  417.40  5117.4  418.95  5123.5  421.15  5138.4  422.19
  5209.9  425.76  5218.6  425.47  5281.4  430.62  5290.2  429.99  5300.2  430.58
#Mann=4,-1,0
  4690.0    0.05       0  4858.1    0.16       0  5004.2    0.07       0
  5010.2    0.16       0
Bank Sta=4976.5,5024.7
Exp/Cntr=0.3,0.1

Type RM Length L Ch R = 1,1872,360,360,360
BEGIN DESCRIPTION:
UNT 064 in Running Cr Watershed 4.0
END DESCRIPTION:
XS GIS Cut Line= 3
      2860183.81      6985182.93      2860455.08      6985163.40
      2860847.41      6985039.85
#Sta/Elev= 30
  4672.3  423.82  4703.6  423.49  4715.9  424.27  4843.9  421.57  4874.0  422.11
  4957.8  415.59  4975.6  413.52  4980.8  411.02  4984.9  409.03  4993.6  402.52
  4994.1  401.72  4999.1  401.72  4999.6  402.52  5007.1  406.20  5022.5  410.77
  5049.0  411.06  5054.9  410.24  5076.8  411.02  5111.9  411.74  5119.6  413.47
  5124.9  412.94  5132.9  414.82  5152.0  416.66  5157.2  415.21  5227.3  421.94
  5248.2  422.01  5254.3  423.93  5259.6  422.79  5286.7  425.47  5355.6  428.24
#Mann=3,-1,0
  4672.3    0.16       0  4993.6    0.07       0  4999.6    0.16       0
Bank Sta=4980.8,5076.8
Exp/Cntr=0.3,0.1

Type RM Length L Ch R = 1,1512,407,407,407
BEGIN DESCRIPTION:
UNT 064 in Running Cr Watershed 3.0
END DESCRIPTION:
XS GIS Cut Line= 3
      2860407.36      6985740.63      2860789.28      6985265.40
      2860880.22      6985103.01
#Sta/Elev= 30
  4427.3  425.62  4493.8  422.43  4607.4  415.54  4664.0  414.36  4706.6  412.27
  4735.4  411.56  4820.2  410.90  4834.6  412.02  4877.8  410.46  4889.8  408.73
  4898.6  407.83  4910.2  407.73  4927.4  407.35  4941.8  408.45  4962.6  409.01
  4970.6  408.45  4977.0  407.59  4985.0  404.94  4991.4  404.13  4996.0  401.31
  4996.5  400.51  5001.5  400.51  5002.0  401.31  5005.8  406.38  5012.4  408.73
  5020.2  412.53  5106.2  423.08  5143.6  425.92  5202.9  428.58  5223.1  428.95
#Mann=5,-1,0
  4427.3    0.16       0  4664.0    0.12       0  4910.2    0.16       0
  4996.0    0.07       0  5002.0    0.16       0
Bank Sta=4889.8,5012.4
Exp/Cntr=0.3,0.1

Type RM Length L Ch R = 1,1105,354,354,354
BEGIN DESCRIPTION:
UNT 064 in Running Cr Watershed 2.0
END DESCRIPTION:
XS GIS Cut Line= 4
      2860802.32      6985975.00      2861060.55      6985580.07
      2861112.63      6985441.18      2861125.00      6985174.97
#Sta/Elev= 30
  4445.7  421.55  4541.3  420.59  4600.5  418.73  4751.2  408.90  4816.5  406.98
  4853.0  406.03  4859.8  402.21  4865.8  402.35  4874.9  405.69  4896.0  406.31
  4923.0  406.24  4946.6  404.26  4977.3  404.54  4987.1  403.49  4999.3  399.73
  4999.8  398.93  5004.8  398.93  5005.3  399.73  5008.4  403.87  5019.1  406.52
  5037.4  406.03  5065.9  406.06  5094.4  407.91  5112.1  409.28  5142.2  414.98
  5182.2  417.91  5212.2  421.54  5274.5  424.53  5327.0  427.11  5332.4  427.29
#Mann=8,-1,0
  4445.7    0.05       0  4816.5    0.12       0  4946.6    0.16       0
  4999.3    0.07       0  5005.3    0.16       0  5094.4    0.05       0
  5274.5    0.16       0  5327.0    0.05       0
Bank Sta=4853,5037.4
Exp/Cntr=0.3,0.1

Type RM Length L Ch R = 1,751,387,387,387
BEGIN DESCRIPTION:
Mapping XS 51320a77
END DESCRIPTION:
XS GIS Cut Line= 4
      2860969.81      6986159.09      2861403.86      6985707.67
      2861410.81      6985506.28      2861206.48      6985229.23
#Sta/Elev= 30
  4294.2  424.18  4308.9  423.81  4578.9  419.07  4611.9  418.45  4626.1  417.09
  4633.0  415.25  4640.2  409.05  4654.4  405.72  4678.2  404.24  4753.5  404.96
  4918.8  401.99  4963.1  402.88  4973.1  402.74  4990.2  400.14  4990.7  399.34
  4996.2  400.14  5013.2  401.31  5023.2  405.01  5033.2  405.28  5043.2  400.98
  5053.2  400.17  5061.5  402.89  5067.9  404.24  5098.3  406.64  5170.4  407.23
  5220.6  409.62  5226.8  411.07  5247.8  410.72  5327.0  414.50  5466.2  423.54
#Mann=6,-1,0
  4294.2    0.16       0  4308.9    0.05       0  4578.9    0.16       0
  4990.2    0.07       0  4996.2    0.16       0  5061.5    0.05       0
Bank Sta=4678.2,5067.9
Exp/Cntr=0.3,0.1

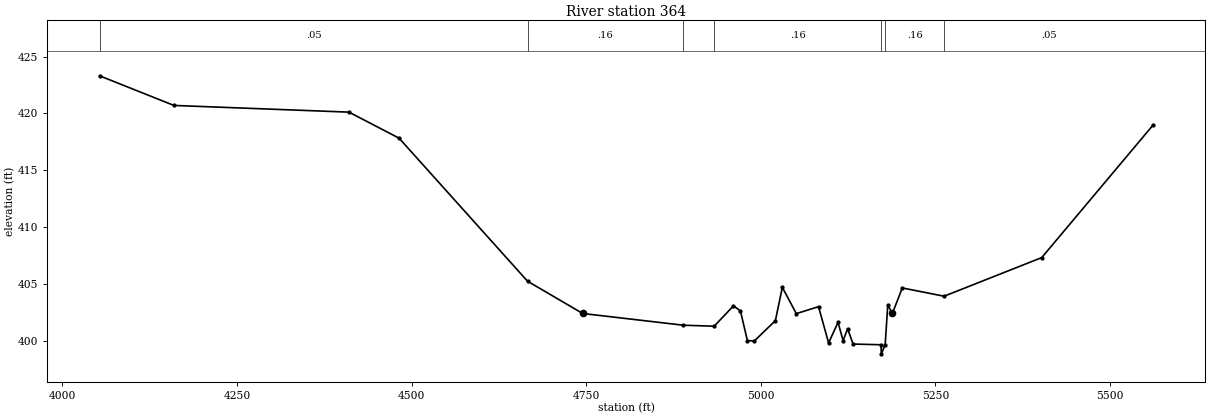
Type RM Length L Ch R = 1,364,0,0,0
BEGIN DESCRIPTION:
UNT 064 in Running Cr Watershed 1.0
END DESCRIPTION:
XS GIS Cut Line= 4
      2861085.74      6986222.85      2861791.02      6985734.58
      2861786.68      6985589.18      2861396.06      6985270.17
#Sta/Elev= 30
  4053.4  423.31  4159.9  420.70  4410.5  420.11  4482.2  417.82  4666.1  405.23
  4745.1  402.39  4888.9  401.36  4933.2  401.27  4960.8  403.06  4970.8  402.62
  4980.8  400.00  4990.8  399.98  5020.8  401.76  5030.8  404.69  5050.8  402.38
  5082.6  402.99  5097.0  399.80  5110.5  401.61  5117.8  400.00  5124.2  401.05
  5132.1  399.70  5172.0  399.64  5172.5  398.84  5178.0  399.64  5181.7  403.14
  5188.3  402.39  5202.5  404.64  5262.3  403.91  5402.1  407.31  5561.0  418.94
#Mann=7,-1,0
  4053.4    0.05       0  4666.1    0.16       0  4888.9    0.05       0
  4933.2    0.16       0  5172.0    0.07       0  5178.0    0.16       0
  5262.3    0.05       0
Bank Sta=4745.1,5188.3
Exp/Cntr=0.3,0.1

Chan Stop Cuts=-1