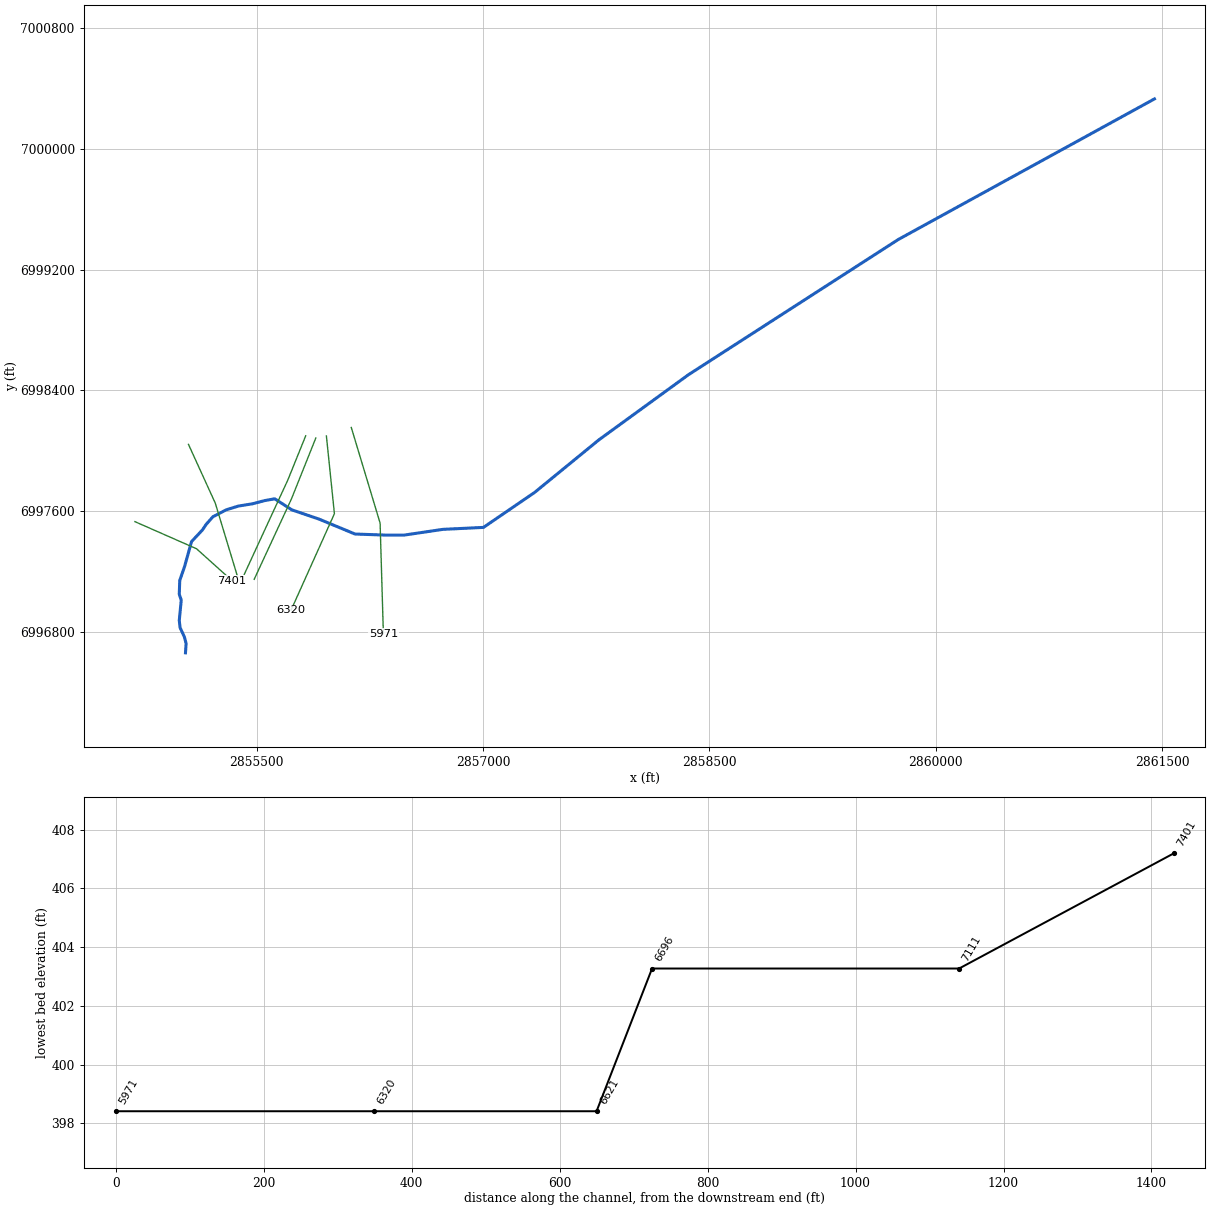
--- UNT 065 in Running Cr Watershed.prj (project) ---

Proj Title=UNT 065 in Running Cr Watershed Base Level Engineering
Current Plan=p01
Default Exp/Contr=0.3,0.1
English Units
Geom File=g01
Flow File=f01
Plan File=p01
BEGIN DESCRIPTION:
UNT 065 in Running Cr Watershed
END DESCRIPTION:

--- UNT 065 in Running Cr Watershed.p01 (plan) ---

Plan Title=Multiple Run
Short Identifier=Multiple
Geom File=g01
Flow File=f01
Subcritical Flow
K Sum by GR= 0
Std Step Tol= 0.01
Critical Tol= 0.01
Num of Std Step Trials= 20
Max Error Tol= 0.3
Flow Tol Ratio= 0.001
Split Flow NTrial= 30
Split Flow Tol= 0.02
Split Flow Ratio= 0.02
Log Output Level= 0
Friction Slope Method= 1
Unsteady Friction Slope Method= 2
Unsteady Bridges Friction Slope Method= 1
Parabolic Critical Depth
Global Vel Dist=  1 , 1 , 1
Global Log Level= 0
CheckData=True
Encroach Param= -1, 0, 0, 0
BEGIN DESCRIPTION:
Multiple Run
END DESCRIPTION:

--- UNT 065 in Running Cr Watershed.f01 (steady flow) ---

Flow Title=Multiple
Number of Profiles=7
Profile Names=10-year,25-year,50-year,1pct_min,100-year,1pct_plu,500-year
River Rch & RM= UNT 065 in Runni,Reach-1,7401
     429     558     659     387     772    1540    1060
Boundary for River Rch & Prof#=UNT 065 in Runni,Reach-1,1
Up Type=0
Dn Type=3
Dn Slope=0.005
Boundary for River Rch & Prof#=UNT 065 in Runni,Reach-1,2
Up Type=0
Dn Type=3
Dn Slope=0.005
Boundary for River Rch & Prof#=UNT 065 in Runni,Reach-1,3
Up Type=0
Dn Type=3
Dn Slope=0.005
Boundary for River Rch & Prof#=UNT 065 in Runni,Reach-1,4
Up Type=0
Dn Type=3
Dn Slope=0.005
Boundary for River Rch & Prof#=UNT 065 in Runni,Reach-1,5
Up Type=0
Dn Type=3
Dn Slope=0.005
Boundary for River Rch & Prof#=UNT 065 in Runni,Reach-1,6
Up Type=0
Dn Type=3
Dn Slope=0.005
Boundary for River Rch & Prof#=UNT 065 in Runni,Reach-1,7
Up Type=0
Dn Type=3
Dn Slope=0.005

--- UNT 065 in Running Cr Watershed.g01 (geometry) ---

Geom Title=Existing Conditions

River Reach=UNT 065 in Runni,Reach-1
Reach XY= 30
      2855028.30      6996661.67      2855032.31      6996723.82
      2855021.28      6996765.93      2854992.21      6996829.08
      2854987.20      6996876.20      2855000.23      6997011.53
      2854987.20      6997049.62      2854990.20      6997140.85
      2855022.28      6997233.07      2855068.40      6997398.48
      2855140.57      6997475.67      2855164.63      6997511.75
      2855209.74      6997562.88      2855297.96      6997608.99
      2855379.16      6997634.05      2855472.39      6997649.09
      2855552.58      6997670.14      2855619.75      6997682.17
      2855733.02      6997608.99      2855915.47      6997546.84
      2856152.05      6997448.60      2856356.55      6997441.58
      2856476.85      6997441.58      2856734.48      6997479.68
      2857003.14      6997492.71      2857342.03      6997724.42
      2857766.73      6998071.90      2858361.31      6998504.33
      2859751.23      6999400.06      2861449.38      7000332.12

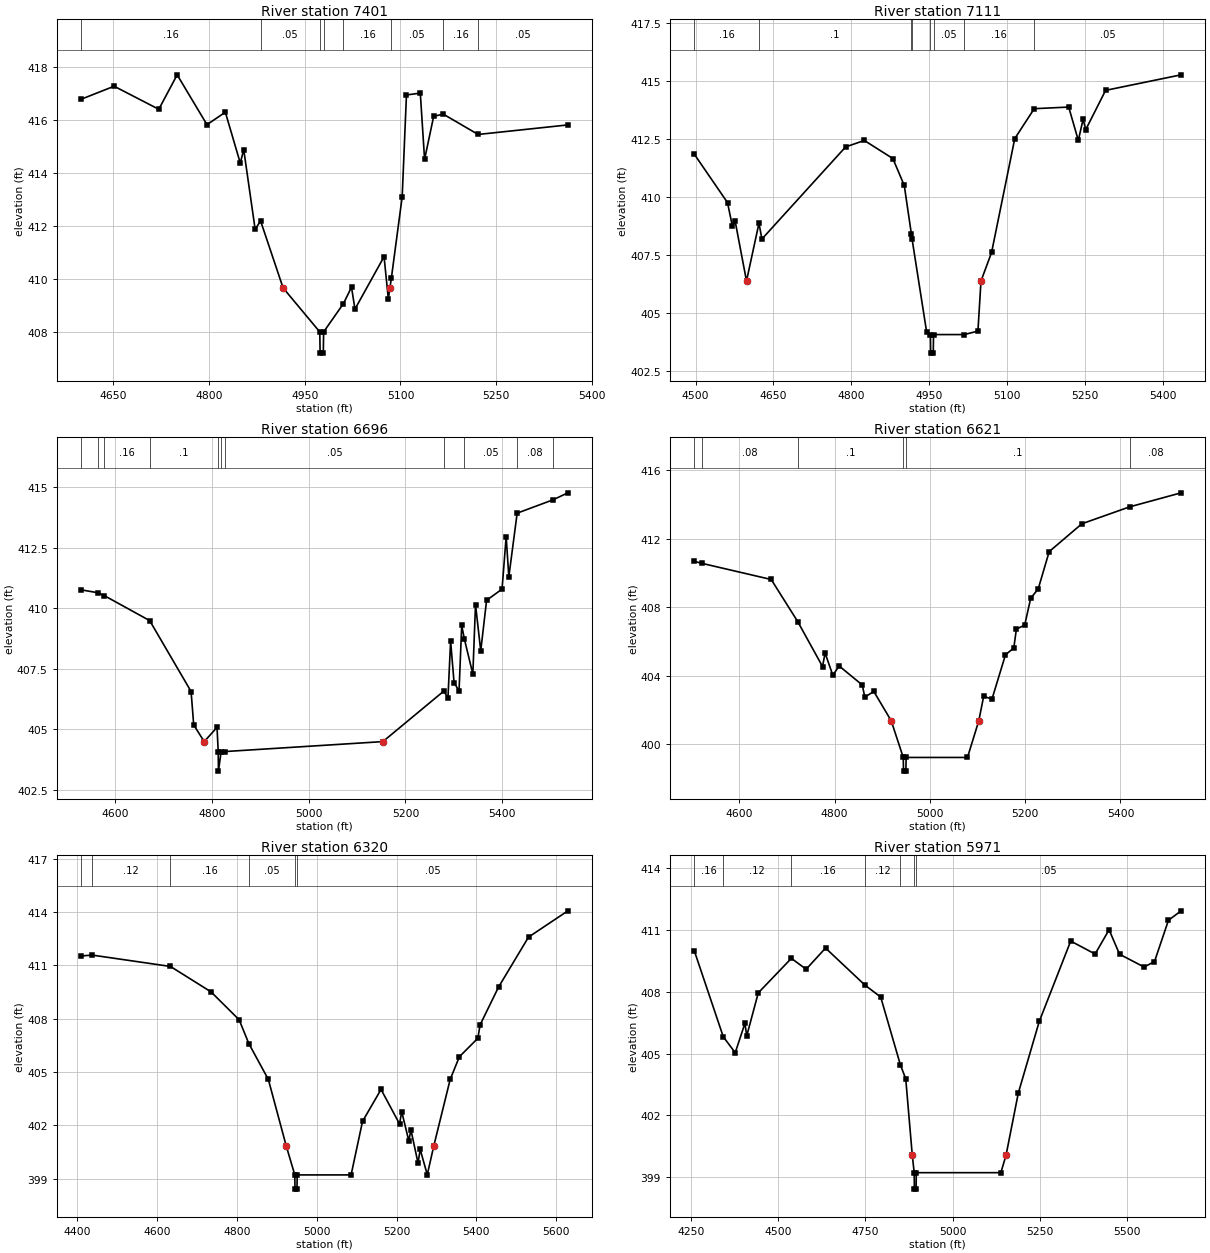
Type RM Length L Ch R = 1,7401,290,290,290
BEGIN DESCRIPTION:
UNT 065 in Running Cr Watershed 15.0
END DESCRIPTION:
XS GIS Cut Line= 3
      2854693.09      6997530.86      2855101.58      6997351.11
      2855336.83      6997139.67
#Sta/Elev= 30
  4599.8  416.77  4651.3  417.26  4721.3  416.39  4750.1  417.69  4796.8  415.81
  4825.6  416.28  4849.0  414.36  4854.4  414.87  4872.3  411.86  4880.8  412.18
  4916.1  409.65  4973.6  407.99  4974.1  407.19  4979.1  407.19  4979.6  407.99
  5010.7  409.06  5023.3  409.68  5028.7  408.85  5074.3  410.83  5081.0  409.24
  5083.5  409.65  5085.7  410.01  5102.7  413.09  5109.4  416.93  5131.1  417.00
  5137.8  414.50  5152.0  416.12  5166.9  416.21  5221.7  415.44  5362.4  415.80
#Mann=8,-1,0
  4599.8    0.16       0  4880.8    0.05       0  4973.6    0.03       0
  4979.6    0.05       0  5010.7    0.16       0  5085.7    0.05       0
  5166.9    0.16       0  5221.7    0.05       0
Bank Sta=4916.1,5083.5
Exp/Cntr=0.3,0.1

Type RM Length L Ch R = 1,7111,415,415,415
BEGIN DESCRIPTION:
UNT 065 in Running Cr Watershed 14.0
END DESCRIPTION:
XS GIS Cut Line= 3
      2855048.10      6998043.01      2855225.82      6997653.34
      2855373.62      6997165.41
#Sta/Elev= 30
  4497.7  411.84  4561.5  409.76  4570.8  408.75  4576.3  408.95  4598.1  406.38
  4622.1  408.87  4627.8  408.19  4789.1  412.16  4825.2  412.44  4880.2  411.66
  4902.2  410.50  4915.9  408.41  4917.3  408.18  4945.4  404.17  4952.6  404.07
  4953.1  403.27  4958.1  403.27  4958.6  404.07  5017.9  404.07  5044.2  404.22
  5050.1  406.38  5070.5  407.61  5115.2  412.52  5152.7  413.81  5219.2  413.88
  5237.7  412.44  5246.9  413.35  5252.1  412.91  5290.3  414.60  5435.8  415.27
#Mann=8,-1,0
  4497.7    0.16       0  4622.1     0.1       0  4915.9    0.16       0
  4917.3    0.05       0  4952.6   0.035       0  4958.6    0.05       0
  5017.9    0.16       0  5152.7    0.05       0
Bank Sta=4598.1,5050.1
Exp/Cntr=0.3,0.1

Type RM Length L Ch R = 1,6696,75,75,75
BEGIN DESCRIPTION:
Mapping XS 7ab0dcc9
END DESCRIPTION:
XS GIS Cut Line= 4
      2855825.12      6998099.91      2855706.51      6997806.48
      2855558.94      6997487.47      2855417.90      6997181.50
#Sta/Elev= 30
  4530.5  410.76  4565.2  410.64  4578.3  410.52  4671.8  409.49  4757.3  406.56
  4762.7  405.18  4784.4  404.49  4810.9  405.08  4813.3  404.07  4813.8  403.27
  4819.3  404.07  4828.1  404.08  5153.3  404.49  5279.3  406.58  5287.7  406.29
  5293.2  408.64  5300.3  406.93  5310.6  406.58  5316.1  409.29  5321.6  408.73
  5339.1  407.28  5344.6  410.15  5355.4  408.24  5367.5  410.33  5399.4  410.79
  5407.9  412.96  5413.4  411.30  5430.6  413.93  5504.5  414.48  5535.4  414.77
#Mann=11,-1,0
  4530.5    0.05       0  4565.2    0.08       0  4578.3    0.16       0
  4671.8     0.1       0  4813.3    0.04       0  4819.3     0.1       0
  4828.1    0.05       0  5279.3    0.16       0  5321.6    0.05       0
  5430.6    0.08       0  5504.5    0.05       0
Bank Sta=4784.4,5153.3
Exp/Cntr=0.3,0.1

Type RM Length L Ch R = 1,6621,301,301,301
BEGIN DESCRIPTION:
UNT 065 in Running Cr Watershed 13.0
END DESCRIPTION:
XS GIS Cut Line= 3
      2855891.84      6998084.68      2855730.38      6997681.04
      2855483.63      6997148.57
#Sta/Elev= 30
  4505.6  410.68  4522.0  410.56  4666.8  409.62  4722.6  407.15  4774.5  404.53
  4779.9  405.32  4796.1  404.02  4809.5  404.56  4857.9  403.45  4863.3  402.74
  4882.2  403.07  4918.6  401.36  4944.0  399.21  4944.5  398.41  4949.5  398.41
  4950.0  399.21  5078.8  399.21  5102.6  401.36  5112.8  402.79  5130.2  402.62
  5158.6  405.22  5176.0  405.61  5181.5  406.72  5198.9  406.95  5211.5  408.52
  5227.3  409.07  5250.3  411.25  5319.0  412.88  5419.3  413.87  5527.2  414.69
#Mann=6,-1,0
  4505.6    0.05       0  4522.0    0.08       0  4722.6     0.1       0
  4944.0    0.04       0  4950.0     0.1       0  5419.3    0.08       0
Bank Sta=4918.6,5102.6
Exp/Cntr=0.3,0.1

Type RM Length L Ch R = 1,6320,349,349,349
BEGIN DESCRIPTION:
UNT 065 in Running Cr Watershed 12.0
END DESCRIPTION:
XS GIS Cut Line= 3
      2855962.16      6998098.32      2856015.25      6997583.49
      2855727.79      6996943.87
#Sta/Elev= 30
  4410.3  411.53  4437.5  411.58  4633.7  410.94  4735.3  409.51  4805.7  407.94
  4830.0  406.60  4878.9  404.58  4923.4  400.86  4945.1  399.21  4945.6  398.41
  4950.6  398.41  4951.1  399.21  5086.1  399.21  5114.7  402.22  5161.1  404.02
  5207.4  402.08  5212.9  402.77  5230.6  401.13  5236.0  401.74  5253.7  399.88
  5259.2  400.64  5276.9  399.22  5293.4  400.86  5334.2  404.58  5357.3  405.86
  5403.6  406.90  5409.1  407.65  5455.4  409.78  5530.4  412.59  5629.1  414.07
#Mann=6,-1,0
  4410.3    0.05       0  4437.5    0.12       0  4633.7    0.16       0
  4830.0    0.05       0  4945.1   0.033       0  4951.1    0.05       0
Bank Sta=4923.4,5293.4
Exp/Cntr=0.3,0.1

Type RM Length L Ch R = 1,5971,0,0,0
BEGIN DESCRIPTION:
UNT 065 in Running Cr Watershed 11.0
END DESCRIPTION:
XS GIS Cut Line= 3
      2856127.10      6998154.74      2856318.06      6997521.11
      2856339.72      6996788.81
#Sta/Elev= 30
  4259.9  409.98  4342.5  405.82  4376.8  405.04  4404.6  406.47  4409.8  405.86
  4442.8  407.95  4537.7  409.63  4580.0  409.10  4635.6  410.13  4748.4  408.33
  4793.6  407.75  4849.9  404.46  4865.4  403.77  4884.1  400.06  4889.6  399.21
  4890.1  398.41  4895.1  398.41  4895.6  399.21  5137.9  399.21  5152.8  400.06
  5187.9  403.08  5247.9  406.56  5338.0  410.47  5408.0  409.84  5448.0  411.02
  5478.0  409.83  5548.1  409.21  5578.1  409.47  5618.1  411.48  5654.3  411.94
#Mann=7,-1,0
  4259.9    0.16       0  4342.5    0.12       0  4537.7    0.16       0
  4748.4    0.12       0  4849.9    0.05       0  4889.6   0.033       0
  4895.6    0.05       0
Bank Sta=4884.1,5152.8
Exp/Cntr=0.3,0.1

Chan Stop Cuts=-1