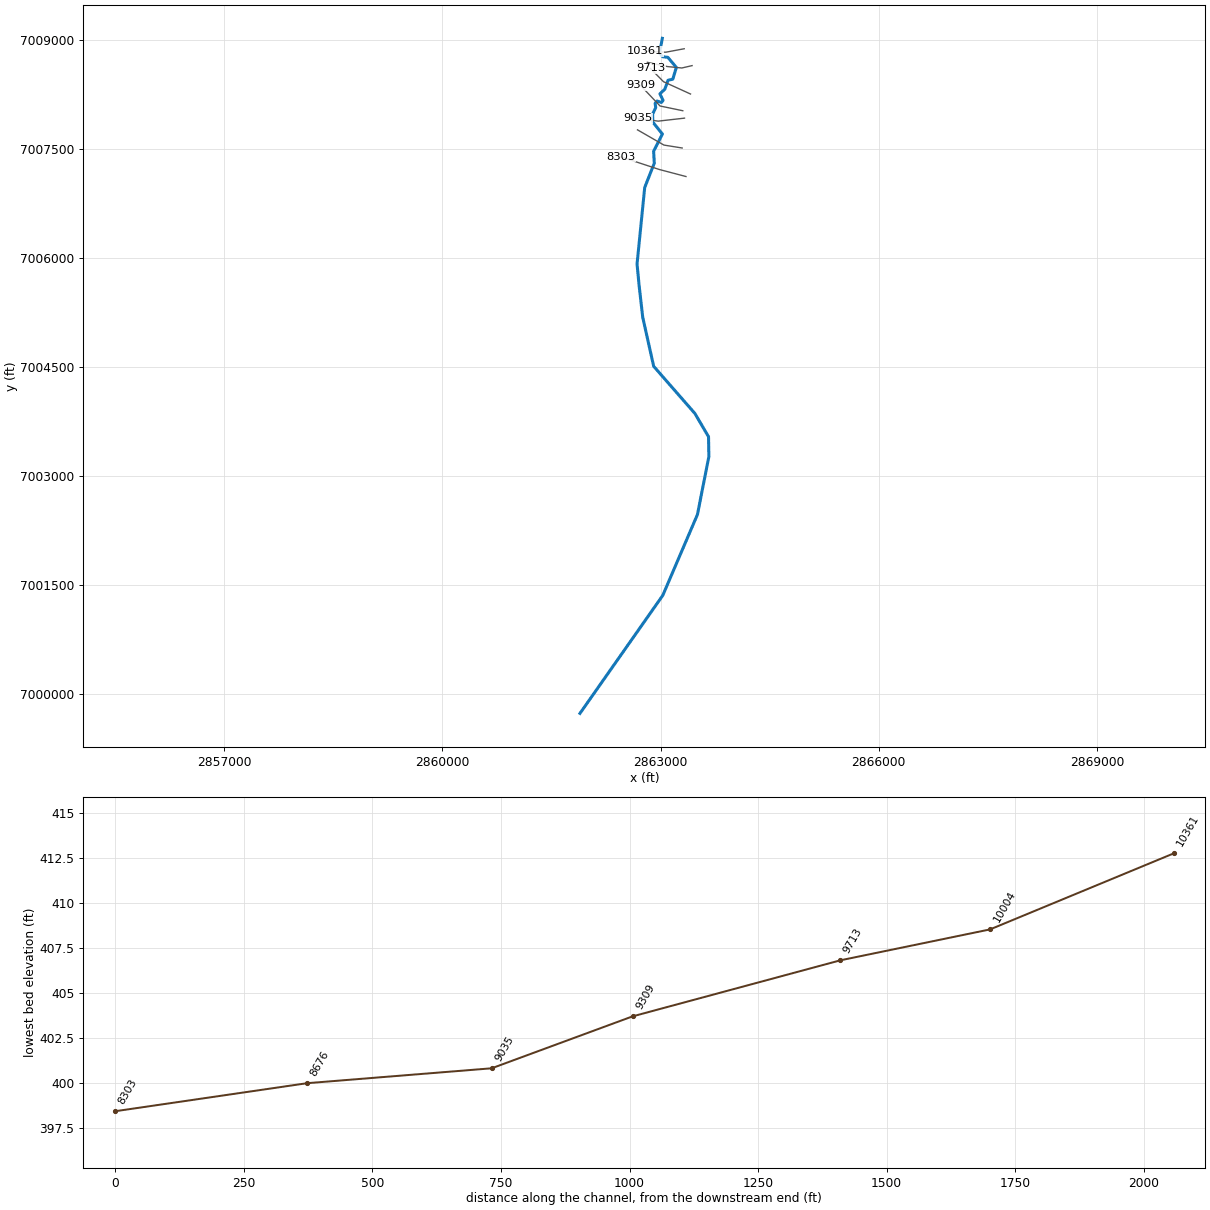
--- UNT 066 in Running Cr Watershed.prj (project) ---

Proj Title=UNT 066 in Running Cr Watershed Base Level Engineering
Current Plan=p01
Default Exp/Contr=0.3,0.1
English Units
Geom File=g01
Flow File=f01
Plan File=p01
BEGIN DESCRIPTION:
UNT 066 in Running Cr Watershed
END DESCRIPTION:

--- UNT 066 in Running Cr Watershed.p01 (plan) ---

Plan Title=Multiple Run
Short Identifier=Multiple
Geom File=g01
Flow File=f01
Subcritical Flow
K Sum by GR= 0
Std Step Tol= 0.01
Critical Tol= 0.01
Num of Std Step Trials= 20
Max Error Tol= 0.3
Flow Tol Ratio= 0.001
Split Flow NTrial= 30
Split Flow Tol= 0.02
Split Flow Ratio= 0.02
Log Output Level= 0
Friction Slope Method= 1
Unsteady Friction Slope Method= 2
Unsteady Bridges Friction Slope Method= 1
Parabolic Critical Depth
Global Vel Dist=  1 , 1 , 1
Global Log Level= 0
CheckData=True
Encroach Param= -1, 0, 0, 0
BEGIN DESCRIPTION:
Multiple Run
END DESCRIPTION:

--- UNT 066 in Running Cr Watershed.f01 (steady flow) ---

Flow Title=Multiple
Number of Profiles=7
Profile Names=10-year,25-year,50-year,1pct_min,100-year,1pct_plu,500-year
River Rch & RM= UNT 066 in Runni,Reach-1,10361
     354     456     535     312     623    1243     846
Boundary for River Rch & Prof#=UNT 066 in Runni,Reach-1,1
Up Type=0
Dn Type=3
Dn Slope=0.005
Boundary for River Rch & Prof#=UNT 066 in Runni,Reach-1,2
Up Type=0
Dn Type=3
Dn Slope=0.005
Boundary for River Rch & Prof#=UNT 066 in Runni,Reach-1,3
Up Type=0
Dn Type=3
Dn Slope=0.005
Boundary for River Rch & Prof#=UNT 066 in Runni,Reach-1,4
Up Type=0
Dn Type=3
Dn Slope=0.005
Boundary for River Rch & Prof#=UNT 066 in Runni,Reach-1,5
Up Type=0
Dn Type=3
Dn Slope=0.005
Boundary for River Rch & Prof#=UNT 066 in Runni,Reach-1,6
Up Type=0
Dn Type=3
Dn Slope=0.005
Boundary for River Rch & Prof#=UNT 066 in Runni,Reach-1,7
Up Type=0
Dn Type=3
Dn Slope=0.005

--- UNT 066 in Running Cr Watershed.g01 (geometry) ---

Geom Title=Existing Conditions

River Reach=UNT 066 in Runni,Reach-1
Reach XY= 30
      2863024.04      7009023.60      2862985.50      7008817.87
      2863028.73      7008770.47      2863100.08      7008762.14
      2863216.79      7008623.58      2863168.05      7008461.69
      2863102.10      7008446.23      2863058.83      7008324.65
      2862990.83      7008259.74      2863034.10      7008170.10
      2863011.43      7008141.25      2862951.67      7008160.82
      2862924.88      7008128.88      2862933.13      7008070.15
      2862889.85      7007980.51      2862893.97      7007870.27
      2863024.83      7007706.44      2862904.28      7007469.46
      2862913.55      7007305.64      2862781.67      7006970.78
      2862676.45      7005918.90      2862703.88      7005630.90
      2862754.17      7005187.47      2862905.02      7004510.89
      2863471.89      7003861.74      2863659.32      7003541.73
      2863663.89      7003267.45      2863506.44      7002469.55
      2863030.39      7001358.76      2861891.53      6999734.83

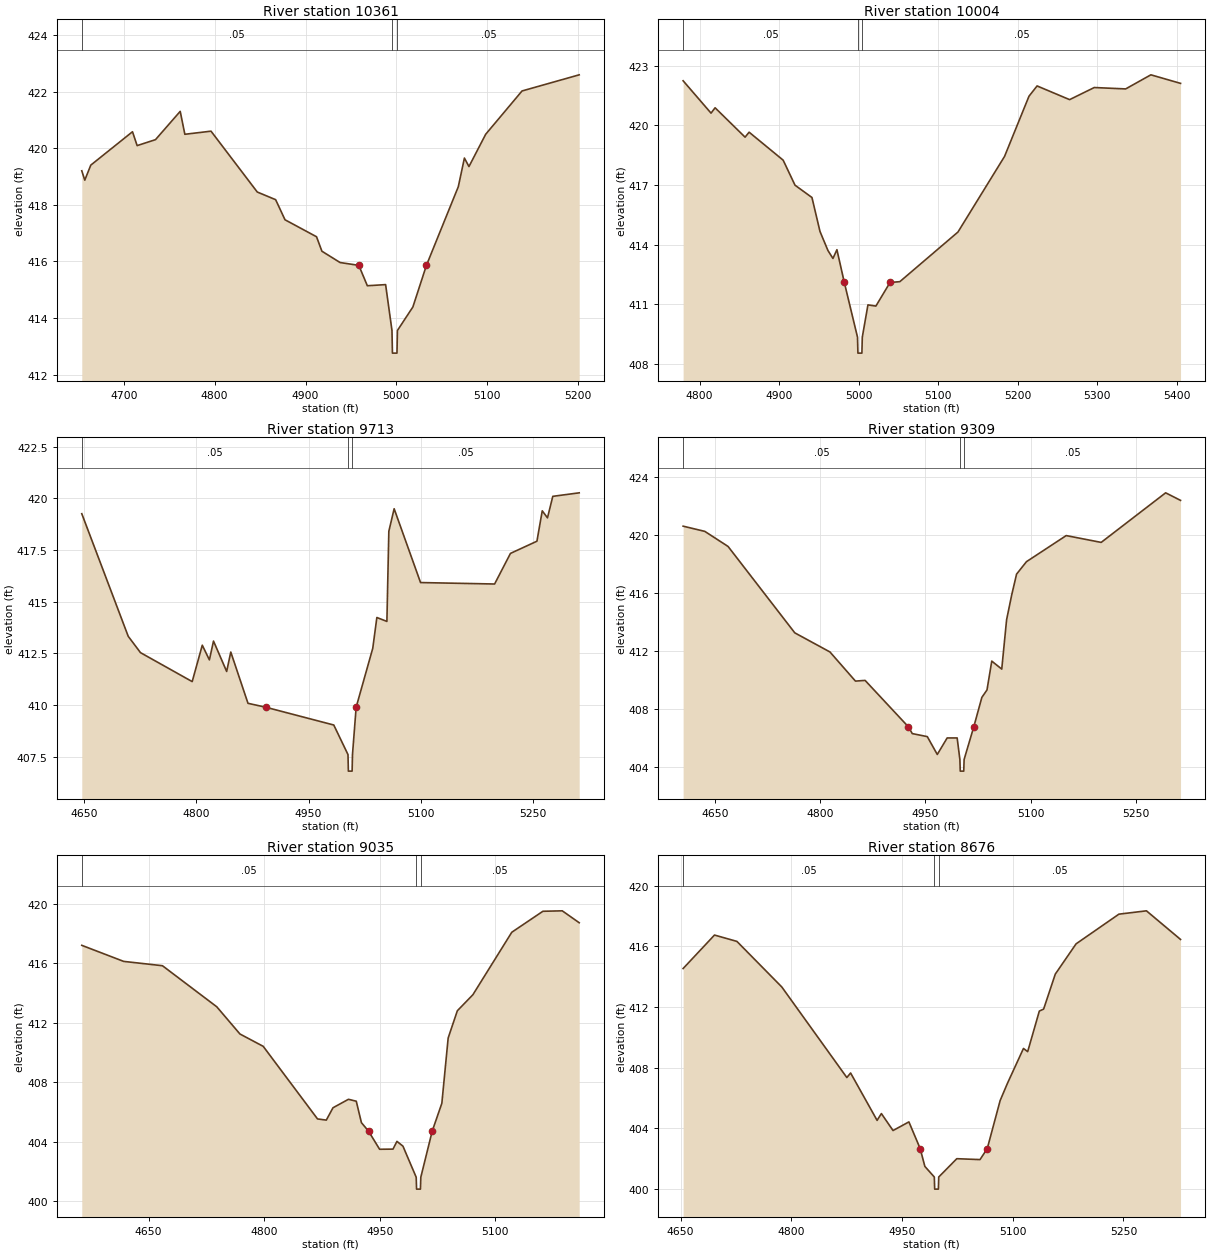
Type RM Length L Ch R = 1,10361,357,357,357
BEGIN DESCRIPTION:
UNT 066 in Running Cr Watershed 24.0
END DESCRIPTION:
XS GIS Cut Line= 3
      2863324.73      7008880.33      2863070.83      7008832.59
      2862782.17      7008845.62
#Sta/Elev= 30
  4653.8  419.20  4657.1  418.87  4663.7  419.40  4709.6  420.58  4714.7  420.09
  4734.9  420.30  4762.1  421.30  4767.2  420.49  4796.0  420.60  4846.9  418.45
  4867.1  418.18  4877.4  417.47  4912.1  416.87  4918.0  416.36  4938.0  415.96
  4958.6  415.86  4968.0  415.14  4988.1  415.18  4995.1  413.56  4995.6  412.76
  5000.6  412.76  5001.1  413.56  5018.1  414.39  5033.0  415.86  5068.1  418.64
  5074.8  419.65  5079.8  419.35  5098.2  420.49  5138.2  422.02  5201.1  422.59
#Mann=3,-1,0
  4653.8    0.05       0  4995.1    0.03       0  5001.1    0.05       0
Bank Sta=4958.6,5033
Exp/Cntr=0.3,0.1

Type RM Length L Ch R = 1,10004,291,291,291
BEGIN DESCRIPTION:
Mapping XS aca136b8
END DESCRIPTION:
XS GIS Cut Line= 4
      2863433.22      7008648.13      2863292.18      7008615.58
      2863094.70      7008635.11      2862818.47      7008693.38
#Sta/Elev= 30
  4779.4  422.25  4814.5  420.62  4819.6  420.89  4857.3  419.41  4862.4  419.66
  4905.2  418.25  4920.1  416.99  4941.4  416.37  4951.5  414.66  4961.5  413.70
  4967.8  413.30  4972.8  413.74  4982.1  412.09  4998.7  409.33  4999.2  408.53
  5004.2  408.53  5004.7  409.33  5011.8  410.96  5021.8  410.90  5039.6  412.09
  5051.9  412.13  5125.0  414.63  5183.6  418.44  5214.3  421.47  5224.5  421.99
  5265.4  421.30  5296.4  421.91  5335.9  421.84  5367.6  422.55  5404.9  422.12
#Mann=3,-1,0
  4779.4    0.05       0  4998.7    0.03       0  5004.7    0.05       0
Bank Sta=4982.1,5039.6
Exp/Cntr=0.3,0.1

Type RM Length L Ch R = 1,9713,404,404,404
BEGIN DESCRIPTION:
UNT 066 in Running Cr Watershed 23.0
END DESCRIPTION:
XS GIS Cut Line= 3
      2863411.54      7008257.51      2863040.45      7008426.78
      2862859.71      7008609.66
#Sta/Elev= 30
  4646.9  419.26  4709.0  413.33  4725.4  412.54  4794.5  411.14  4808.0  412.90
  4817.5  412.19  4823.0  413.10  4840.6  411.63  4846.1  412.57  4869.1  410.09
  4892.9  409.90  4983.8  409.04  5002.8  407.61  5003.3  406.81  5008.3  406.81
  5008.8  407.61  5013.7  409.90  5035.9  412.75  5041.4  414.24  5054.8  414.05
  5057.4  418.41  5064.5  419.50  5099.8  415.93  5198.8  415.86  5220.0  417.34
  5255.4  417.93  5262.5  419.40  5269.5  419.06  5276.6  420.10  5311.9  420.27
#Mann=3,-1,0
  4646.9    0.05       0  5002.8    0.03       0  5008.8    0.05       0
Bank Sta=4892.9,5013.7
Exp/Cntr=0.3,0.1

Type RM Length L Ch R = 1,9309,274,274,274
BEGIN DESCRIPTION:
UNT 066 in Running Cr Watershed 22.0
END DESCRIPTION:
XS GIS Cut Line= 3
      2863305.21      7008027.47      2862992.70      7008092.58
      2862725.03      7008374.96
#Sta/Elev= 30
  4605.0  420.59  4635.9  420.23  4669.0  419.19  4764.0  413.23  4814.1  411.91
  4850.4  409.90  4864.1  409.95  4925.7  406.75  4931.3  406.28  4952.7  406.07
  4966.9  404.84  4981.0  405.98  4995.2  405.98  4999.1  404.49  4999.6  403.69
  5004.6  403.69  5005.1  404.49  5018.9  406.75  5030.4  408.78  5037.7  409.29
  5044.5  411.28  5058.7  410.73  5065.6  414.13  5072.9  415.85  5079.8  417.28
  5093.9  418.14  5150.5  419.94  5200.3  419.47  5292.1  422.89  5313.3  422.37
#Mann=3,-1,0
  4605.0    0.05       0  4999.1    0.03       0  5005.1    0.05       0
Bank Sta=4925.7,5018.9
Exp/Cntr=0.3,0.1

Type RM Length L Ch R = 1,9035,359,359,359
BEGIN DESCRIPTION:
UNT 066 in Running Cr Watershed 21.0
END DESCRIPTION:
XS GIS Cut Line= 3
      2863329.03      7007925.47      2862966.66      7007884.24
      2862688.36      7007923.07
#Sta/Elev= 30
  4563.2  417.19  4617.6  416.11  4667.9  415.82  4738.4  413.06  4768.5  411.23
  4798.7  410.40  4869.2  405.52  4880.6  405.44  4889.3  406.27  4909.4  406.84
  4919.5  406.71  4926.2  405.27  4935.4  404.70  4949.8  403.48  4967.2  403.49
  4972.3  404.01  4980.1  403.69  4997.3  401.60  4997.8  400.80  5002.8  400.80
  5003.3  401.60  5018.1  404.70  5030.6  406.57  5038.8  410.96  5050.7  412.79
  5070.9  413.87  5121.4  418.07  5161.8  419.48  5186.9  419.51  5208.9  418.71
#Mann=3,-1,0
  4563.2    0.05       0  4997.3    0.03       0  5003.3    0.05       0
Bank Sta=4935.4,5018.1
Exp/Cntr=0.3,0.1

Type RM Length L Ch R = 1,8676,373,373,373
BEGIN DESCRIPTION:
UNT 066 in Running Cr Watershed 20.0
END DESCRIPTION:
XS GIS Cut Line= 3
      2863296.99      7007514.44      2863046.16      7007554.81
      2862682.40      7007764.44
#Sta/Elev= 30
  4653.5  414.54  4696.0  416.75  4726.4  416.33  4787.2  413.32  4875.3  407.34
  4880.4  407.64  4916.3  404.51  4922.1  404.96  4937.9  403.84  4959.4  404.41
  4974.7  402.64  4981.0  401.47  4993.8  400.77  4994.3  399.97  4999.3  399.97
  4999.8  400.77  5024.3  401.98  5055.7  401.92  5065.5  402.64  5083.0  405.82
  5093.0  406.97  5114.6  409.26  5120.3  409.05  5136.1  411.73  5141.9  411.86
  5157.7  414.17  5185.9  416.17  5243.9  418.13  5281.2  418.35  5327.4  416.46
#Mann=3,-1,0
  4653.5    0.05       0  4993.8    0.03       0  4999.8    0.05       0
Bank Sta=4974.7,5065.5
Exp/Cntr=0.3,0.1

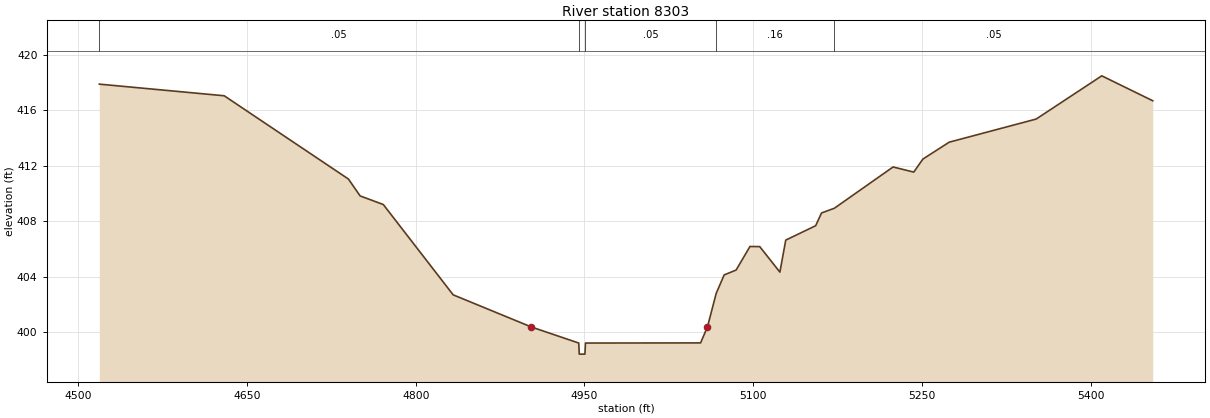
Type RM Length L Ch R = 1,8303,0,0,0
BEGIN DESCRIPTION:
UNT 066 in Running Cr Watershed 19.0
END DESCRIPTION:
XS GIS Cut Line= 3
      2863349.06      7007122.09      2862980.99      7007219.31
      2862453.20      7007392.92
#Sta/Elev= 30
  4518.8  417.90  4629.8  417.06  4740.2  411.05  4750.6  409.83  4771.2  409.21
  4833.3  402.69  4902.8  400.37  4944.9  399.21  4945.4  398.41  4950.4  398.41
  4950.9  399.21  5053.2  399.22  5059.3  400.37  5067.1  402.80  5074.2  404.13
  5084.8  404.48  5097.1  406.18  5105.8  406.17  5123.7  404.33  5128.9  406.64
  5155.5  407.68  5160.7  408.60  5172.1  408.94  5224.3  411.92  5242.7  411.55
  5250.8  412.49  5274.2  413.71  5351.5  415.38  5409.8  418.50  5455.1  416.70
#Mann=5,-1,0
  4518.8    0.05       0  4944.9   0.033       0  4950.9    0.05       0
  5067.1    0.16       0  5172.1    0.05       0
Bank Sta=4902.8,5059.3
Exp/Cntr=0.3,0.1

Chan Stop Cuts=-1