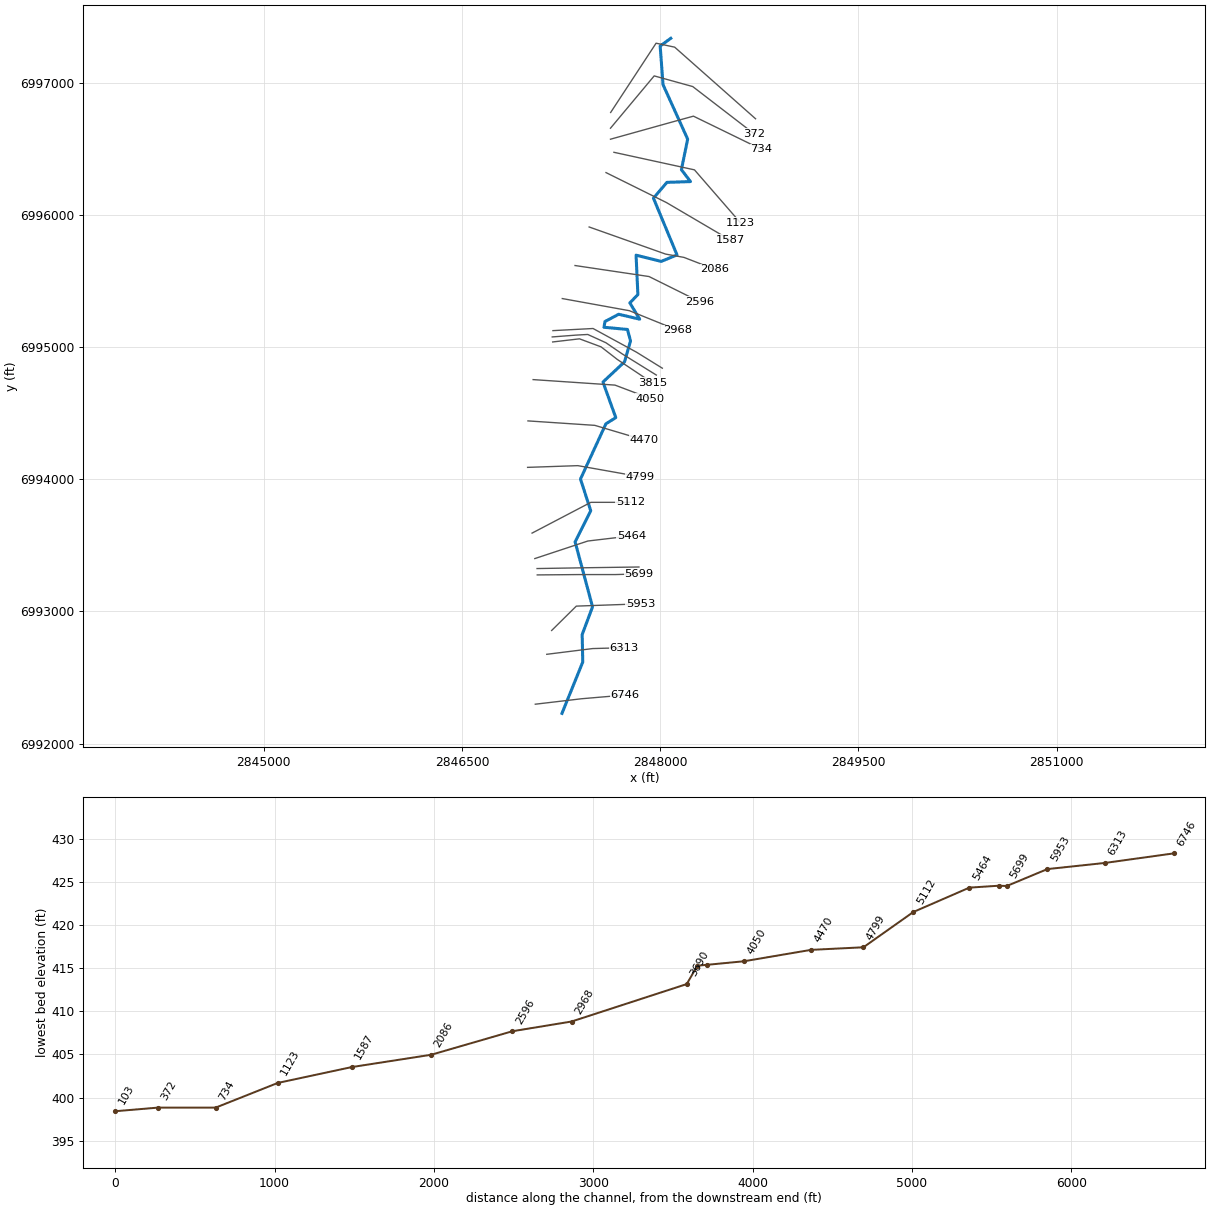
--- UNT 067 in Running Cr Watershed.prj (project) ---

Proj Title=UNT 067 in Running Cr Watershed Base Level Engineering
Current Plan=p01
Default Exp/Contr=0.3,0.1
English Units
Geom File=g01
Flow File=f01
Plan File=p01
BEGIN DESCRIPTION:
UNT 067 in Running Cr Watershed
END DESCRIPTION:

--- UNT 067 in Running Cr Watershed.p01 (plan) ---

Plan Title=Multiple Run
Short Identifier=Multiple
Geom File=g01
Flow File=f01
Subcritical Flow
K Sum by GR= 0
Std Step Tol= 0.01
Critical Tol= 0.01
Num of Std Step Trials= 20
Max Error Tol= 0.3
Flow Tol Ratio= 0.001
Split Flow NTrial= 30
Split Flow Tol= 0.02
Split Flow Ratio= 0.02
Log Output Level= 0
Friction Slope Method= 1
Unsteady Friction Slope Method= 2
Unsteady Bridges Friction Slope Method= 1
Parabolic Critical Depth
Global Vel Dist=  1 , 1 , 1
Global Log Level= 0
CheckData=True
Encroach Param= -1, 0, 0, 0
BEGIN DESCRIPTION:
Multiple Run
END DESCRIPTION:

--- UNT 067 in Running Cr Watershed.f01 (steady flow) ---

Flow Title=Multiple
Number of Profiles=7
Profile Names=10-year,25-year,50-year,1pct_min,100-year,1pct_plu,500-year
River Rch & RM= UNT 067 in Runni,Reach-1,6746
     443     583     694     411     821    1638    1149
River Rch & RM= UNT 067 in Runni,Reach-1,734
     556     741     890     532    1061    2116    1509
Boundary for River Rch & Prof#=UNT 067 in Runni,Reach-1,1
Up Type=0
Dn Type=3
Dn Slope=0.005
Boundary for River Rch & Prof#=UNT 067 in Runni,Reach-1,2
Up Type=0
Dn Type=3
Dn Slope=0.005
Boundary for River Rch & Prof#=UNT 067 in Runni,Reach-1,3
Up Type=0
Dn Type=3
Dn Slope=0.005
Boundary for River Rch & Prof#=UNT 067 in Runni,Reach-1,4
Up Type=0
Dn Type=3
Dn Slope=0.005
Boundary for River Rch & Prof#=UNT 067 in Runni,Reach-1,5
Up Type=0
Dn Type=3
Dn Slope=0.005
Boundary for River Rch & Prof#=UNT 067 in Runni,Reach-1,6
Up Type=0
Dn Type=3
Dn Slope=0.005
Boundary for River Rch & Prof#=UNT 067 in Runni,Reach-1,7
Up Type=0
Dn Type=3
Dn Slope=0.005

--- UNT 067 in Running Cr Watershed.g01 (geometry) ---

Geom Title=Existing Conditions

River Reach=UNT 067 in Runni,Reach-1
Reach XY= 30
      2847256.57      6992228.14      2847413.93      6992616.40
      2847409.49      6992824.44      2847487.93      6993034.25
      2847356.00      6993526.02      2847474.30      6993761.19
      2847396.71      6994000.97      2847589.09      6994419.37
      2847663.87      6994465.81      2847566.86      6994734.96
      2847730.11      6994888.32      2847775.23      6995046.17
      2847752.28      6995133.08      2847574.38      6995149.61
      2847582.05      6995193.17      2847685.97      6995248.08
      2847844.80      6995210.82      2847770.29      6995334.35
      2847831.08      6995397.10      2847817.35      6995695.15
      2848007.56      6995648.09      2848127.17      6995697.12
      2847948.73      6996126.55      2848050.70      6996246.16
      2848229.13      6996252.04      2848160.50      6996342.24
      2848207.56      6996573.62      2848021.28      6996985.41
      2847999.71      6997277.58      2848079.71      6997335.96

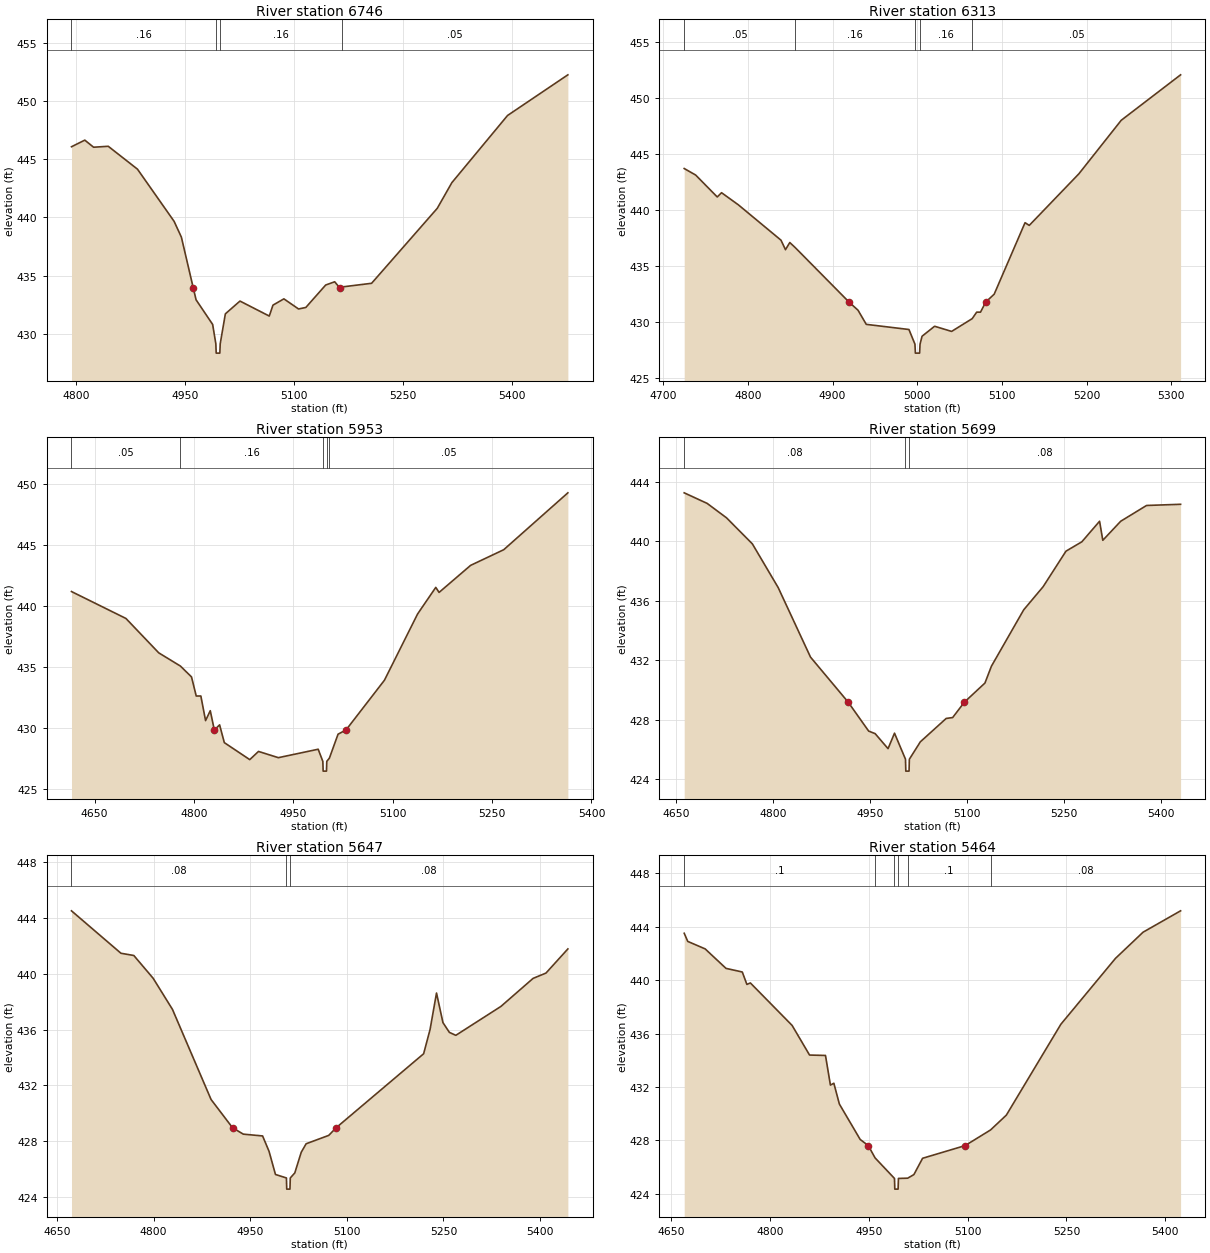
Type RM Length L Ch R = 1,6746,433,433,433
BEGIN DESCRIPTION:
UNT 067 in Running Cr Watershed 15.0
END DESCRIPTION:
XS GIS Cut Line= 3
      2847054.79      6992297.51      2847404.16      6992338.74
      2847734.07      6992366.96
#Sta/Elev= 30
  4793.7  446.08  4812.0  446.65  4824.1  446.04  4844.3  446.12  4884.5  444.15
  4934.9  439.66  4944.9  438.30  4961.2  433.94  4965.1  432.91  4987.9  430.79
  4992.3  429.12  4992.8  428.32  4997.8  428.32  4998.3  429.12  5005.4  431.70
  5025.5  432.80  5065.8  431.51  5070.9  432.45  5085.9  432.99  5106.1  432.12
  5116.1  432.25  5143.4  434.18  5155.8  434.46  5162.7  433.94  5165.2  434.01
  5206.6  434.33  5296.9  440.78  5317.0  442.99  5393.6  448.77  5476.6  452.27
#Mann=4,-1,0
  4793.7    0.16       0  4992.3    0.07       0  4998.3    0.16       0
  5165.2    0.05       0
Bank Sta=4961.2,5162.7
Exp/Cntr=0.3,0.1

Type RM Length L Ch R = 1,6313,360,360,360
BEGIN DESCRIPTION:
UNT 067 in Running Cr Watershed 14.0
END DESCRIPTION:
XS GIS Cut Line= 3
      2847141.62      6992675.12      2847488.79      6992718.52
      2847725.03      6992725.00
#Sta/Elev= 30
  4724.8  443.70  4738.3  443.12  4763.8  441.16  4768.9  441.54  4788.7  440.46
  4839.1  437.30  4844.4  436.45  4849.5  437.09  4856.0  436.63  4919.6  431.76
  4930.1  431.04  4939.8  429.78  4990.2  429.32  4997.3  428.01  4997.8  427.21
  5002.8  427.21  5003.3  428.01  5005.7  428.72  5020.5  429.61  5040.6  429.15
  5064.9  430.29  5070.2  430.87  5074.7  430.87  5080.9  431.77  5090.9  432.48
  5127.3  438.86  5132.3  438.62  5190.9  443.23  5240.9  448.01  5311.0  452.07
#Mann=5,-1,0
  4724.8    0.05       0  4856.0    0.16       0  4997.3    0.07       0
  5003.3    0.16       0  5064.9    0.05       0
Bank Sta=4919.6,5080.9
Exp/Cntr=0.3,0.1

Type RM Length L Ch R = 1,5953,254,254,254
BEGIN DESCRIPTION:
Mapping XS dab3c814
END DESCRIPTION:
XS GIS Cut Line= 3
      2847178.48      6992855.25      2847365.09      6993039.70
      2847851.70      6993057.00
#Sta/Elev= 30
  4615.1  441.18  4697.3  438.98  4746.8  436.17  4779.5  435.09  4796.3  434.20
  4803.4  432.64  4810.4  432.64  4817.5  430.63  4824.6  431.44  4830.7  429.87
  4838.7  430.28  4845.8  428.83  4884.2  427.44  4897.4  428.11  4927.4  427.60
  4987.5  428.29  4994.5  427.30  4995.0  426.50  5000.0  426.50  5000.5  427.30
  5004.4  427.56  5017.5  429.52  5029.6  429.87  5087.5  433.93  5137.6  439.35
  5165.0  441.52  5170.0  441.11  5217.6  443.32  5267.6  444.60  5364.4  449.25
#Mann=5,-1,0
  4615.1    0.05       0  4779.5    0.16       0  4994.5    0.07       0
  5000.5    0.16       0  5004.4    0.05       0
Bank Sta=4830.7,5029.6
Exp/Cntr=0.3,0.1

Type RM Length L Ch R = 1,5699,52,52,52
BEGIN DESCRIPTION:
Mapping XS 7716bb17
END DESCRIPTION:
XS GIS Cut Line= 4
      2847069.49      6993275.81      2847379.42      6993278.41
      2847660.67      6993278.41      2847837.70      6993283.62
#Sta/Elev= 30
  4662.8  443.24  4698.3  442.53  4728.3  441.56  4768.3  439.81  4808.3  436.87
  4858.3  432.20  4916.5  429.18  4948.3  427.23  4958.3  427.06  4978.3  426.05
  4988.3  427.09  5005.3  425.34  5005.8  424.54  5010.8  424.54  5011.3  425.34
  5028.3  426.51  5068.3  428.08  5078.3  428.14  5096.6  429.18  5128.3  430.46
  5138.3  431.59  5188.3  435.38  5218.3  436.93  5253.7  439.32  5278.3  439.95
  5305.7  441.33  5310.7  440.05  5338.4  441.33  5378.4  442.39  5431.1  442.47
#Mann=3,-1,0
  4662.8    0.08       0  5005.3    0.07       0  5011.3    0.08       0
Bank Sta=4916.5,5096.6
Exp/Cntr=0.3,0.1

Type RM Length L Ch R = 1,5647,183,183,183
BEGIN DESCRIPTION:
UNT 067 in Running Cr Watershed 13.0
END DESCRIPTION:
XS GIS Cut Line= 3
      2847068.21      6993323.98      2847465.35      6993330.50
      2847839.02      6993335.70
#Sta/Elev= 30
  4672.4  444.51  4749.2  441.47  4769.2  441.31  4799.2  439.68  4829.2  437.45
  4889.2  430.99  4922.5  428.97  4939.2  428.51  4969.2  428.38  4979.2  427.28
  4989.2  425.62  5006.2  425.37  5006.7  424.57  5011.7  424.57  5012.2  425.37
  5019.2  425.73  5029.2  427.21  5036.8  427.82  5071.9  428.42  5083.5  428.97
  5219.3  434.27  5229.3  436.01  5239.3  438.62  5249.3  436.50  5259.3  435.80
  5269.3  435.59  5339.3  437.66  5389.3  439.67  5409.3  440.05  5443.3  441.78
#Mann=3,-1,0
  4672.4    0.08       0  5006.2    0.07       0  5012.2    0.08       0
Bank Sta=4922.5,5083.5
Exp/Cntr=0.3,0.1

Type RM Length L Ch R = 1,5464,352,352,352
BEGIN DESCRIPTION:
UNT 067 in Running Cr Watershed 12.0
END DESCRIPTION:
XS GIS Cut Line= 3
      2847051.27      6993399.50      2847452.33      6993532.32
      2847781.57      6993571.20
#Sta/Elev= 30
  4669.4  443.51  4674.8  442.90  4701.2  442.34  4732.9  440.88  4757.6  440.61
  4764.6  439.68  4769.9  439.79  4833.3  436.61  4859.8  434.39  4884.0  434.36
  4891.5  432.14  4896.7  432.28  4905.1  430.72  4936.7  428.07  4949.0  427.61
  4959.3  426.69  4988.8  425.15  4989.3  424.35  4994.3  424.35  4994.8  425.15
  5008.9  425.17  5018.3  425.44  5031.5  426.66  5096.1  427.61  5134.7  428.78
  5158.7  429.89  5241.6  436.70  5324.5  441.63  5366.4  443.59  5423.4  445.19
#Mann=6,-1,0
  4669.4     0.1       0  4959.3    0.08       0  4988.8    0.07       0
  4994.8    0.08       0  5008.9     0.1       0  5134.7    0.08       0
Bank Sta=4949,5096.1
Exp/Cntr=0.3,0.1

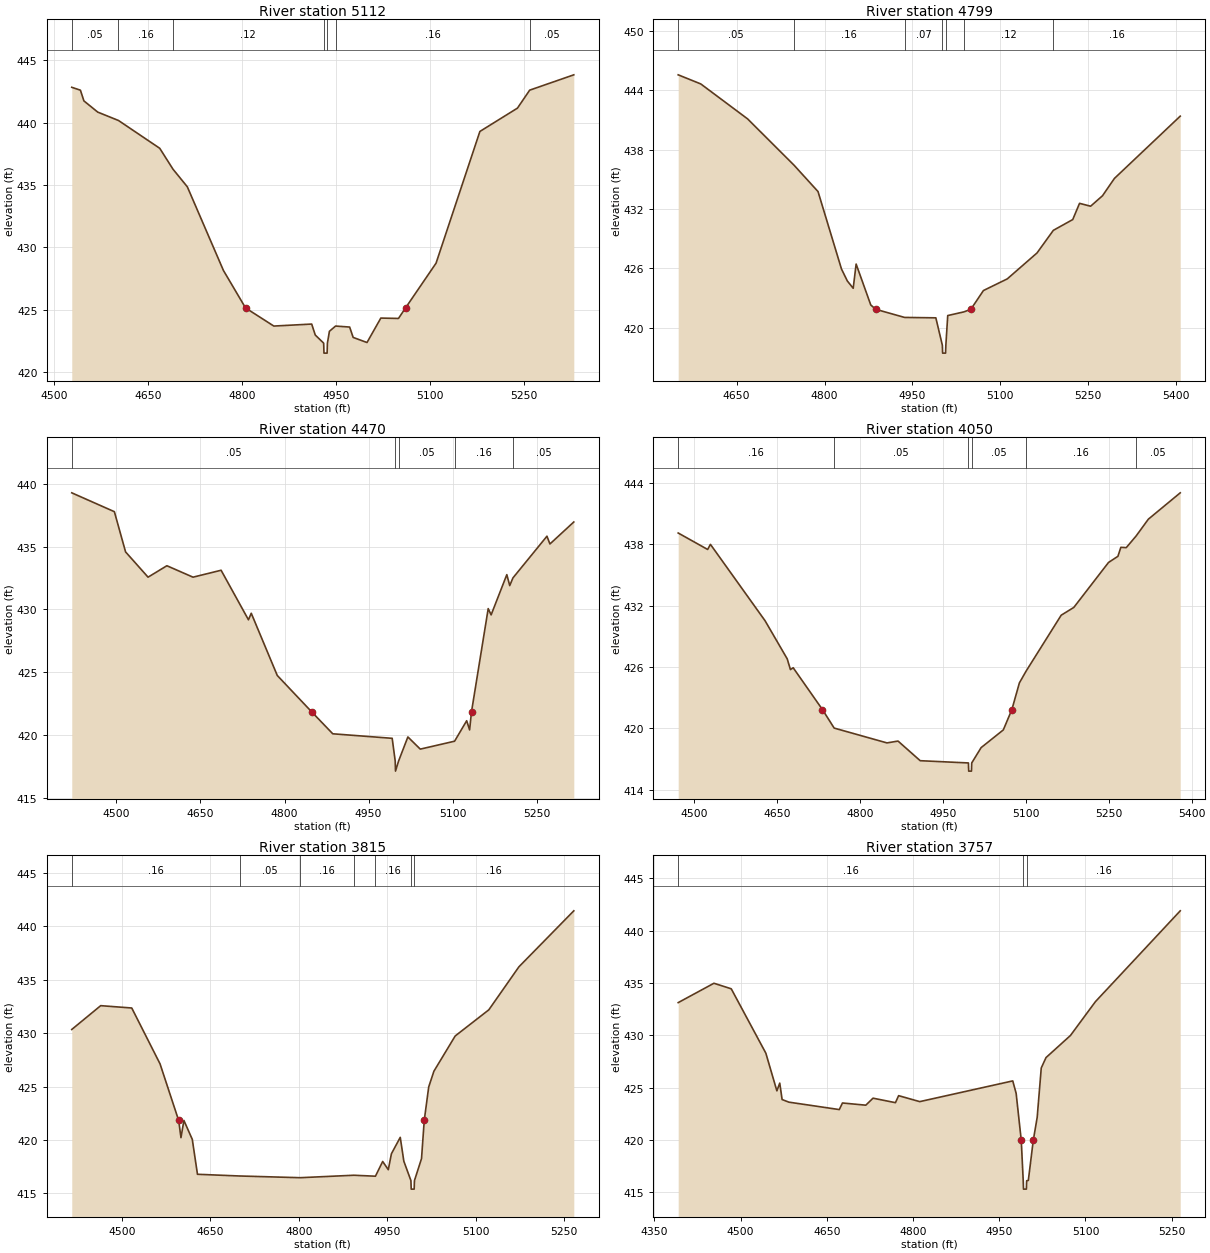
Type RM Length L Ch R = 1,5112,313,313,313
BEGIN DESCRIPTION:
UNT 067 in Running Cr Watershed 11.0
END DESCRIPTION:
XS GIS Cut Line= 3
      2847030.48      6993592.23      2847475.00      6993825.00
      2847775.02      6993825.00
#Sta/Elev= 30
  4528.2  442.83  4542.0  442.60  4547.6  441.74  4569.7  440.84  4602.8  440.17
  4668.7  437.94  4689.8  436.27  4712.8  434.85  4770.4  428.15  4805.8  425.14
  4850.9  423.69  4911.4  423.85  4917.1  422.97  4930.5  422.32  4931.0  421.52
  4936.0  421.52  4936.5  422.32  4939.7  423.27  4949.5  423.69  4972.0  423.61
  4977.6  422.78  4999.7  422.37  5021.8  424.33  5050.0  424.30  5061.2  425.14
  5110.0  428.73  5180.0  439.29  5240.0  441.16  5259.5  442.60  5330.0  443.83
#Mann=7,-1,0
  4528.2    0.05       0  4602.8    0.16       0  4689.8    0.12       0
  4930.5    0.07       0  4936.5    0.12       0  4949.5    0.16       0
  5259.5    0.05       0
Bank Sta=4805.8,5061.2
Exp/Cntr=0.3,0.1

Type RM Length L Ch R = 1,4799,329,329,329
BEGIN DESCRIPTION:
UNT 067 in Running Cr Watershed 10.0
END DESCRIPTION:
XS GIS Cut Line= 3
      2846996.56      6994089.61      2847376.81      6994102.63
      2847845.59      6994019.29
#Sta/Elev= 30
  4550.3  445.58  4588.8  444.66  4668.8  441.12  4748.1  436.43  4788.9  433.77
  4828.9  425.94  4838.9  424.73  4848.9  423.99  4853.9  426.44  4878.9  422.30
  4887.5  421.86  4936.6  421.04  4989.9  421.00  5001.0  418.23  5001.5  417.43
  5006.5  417.43  5007.0  418.23  5010.2  421.23  5037.6  421.60  5049.6  421.86
  5071.1  423.76  5111.8  424.94  5162.5  427.56  5190.4  429.85  5223.5  430.94
  5235.1  432.58  5254.0  432.29  5274.3  433.35  5294.6  435.10  5406.9  441.40
#Mann=7,-1,0
  4550.3    0.05       0  4748.1    0.16       0  4936.6    0.07       0
  5001.0    0.07       0  5007.0    0.07       0  5037.6    0.12       0
  5190.4    0.16       0
Bank Sta=4887.5,5049.6
Exp/Cntr=0.3,0.1

Type RM Length L Ch R = 1,4470,420,420,420
BEGIN DESCRIPTION:
UNT 067 in Running Cr Watershed 9.0
END DESCRIPTION:
XS GIS Cut Line= 3
      2846999.17      6994441.17      2847505.02      6994407.50
      2847877.58      6994296.88
#Sta/Elev= 30
  4420.5  439.27  4496.5  437.77  4516.5  434.57  4556.6  432.56  4590.2  433.47
  4636.8  432.56  4686.9  433.11  4735.7  429.17  4740.7  429.69  4787.1  424.74
  4848.4  421.85  4886.1  420.10  4992.1  419.74  4997.5  417.93  4998.0  417.13
  5003.5  417.93  5020.1  419.85  5042.2  418.88  5103.4  419.51  5125.0  421.14
  5130.2  420.41  5133.6  421.85  5163.4  430.06  5168.6  429.56  5196.6  432.76
  5201.8  431.89  5207.5  432.50  5268.2  435.82  5273.5  435.20  5316.1  436.95
#Mann=5,-1,0
  4420.5    0.05       0  4997.5   0.033       0  5003.5    0.05       0
  5103.4    0.16       0  5207.5    0.05       0
Bank Sta=4848.4,5133.6
Exp/Cntr=0.3,0.1

Type RM Length L Ch R = 1,4050,235,235,235
BEGIN DESCRIPTION:
UNT 067 in Running Cr Watershed 8.0
END DESCRIPTION:
XS GIS Cut Line= 3
      2847038.29      6994753.67      2847658.06      6994712.01
      2847926.31      6994610.44
#Sta/Elev= 30
  4471.4  439.10  4524.7  437.49  4529.7  437.99  4628.5  430.52  4668.6  426.79
  4674.4  425.74  4679.4  425.92  4732.3  421.83  4753.5  420.02  4849.0  418.57
  4869.0  418.75  4909.1  416.83  4996.3  416.61  4996.8  415.81  5001.8  415.81
  5002.3  416.61  5019.3  418.11  5059.4  419.84  5074.9  421.83  5088.5  424.44
  5100.5  425.58  5164.1  431.06  5186.9  431.82  5249.7  436.22  5266.7  436.82
  5272.0  437.70  5281.8  437.67  5299.5  438.80  5321.7  440.45  5379.4  443.03
#Mann=6,-1,0
  4471.4    0.16       0  4753.5    0.05       0  4996.3   0.033       0
  5002.3    0.05       0  5100.5    0.16       0  5299.5    0.05       0
Bank Sta=4732.3,5074.9
Exp/Cntr=0.3,0.1

Type RM Length L Ch R = 1,3815,58,58,58
BEGIN DESCRIPTION:
Mapping XS 2de2f01b
END DESCRIPTION:
XS GIS Cut Line= 5
      2847186.23      6995038.54      2847389.33      6995062.19
      2847552.52      6995001.43      2847675.78      6994905.94
      2847939.85      6994729.90
#Sta/Elev= 30
  4414.9  430.34  4464.0  432.57  4516.7  432.35  4564.7  427.12  4596.3  421.82
  4600.2  420.21  4605.2  421.82  4619.4  420.05  4628.2  416.78  4699.7  416.62
  4802.6  416.46  4893.4  416.69  4930.2  416.60  4942.5  417.98  4952.0  417.21
  4957.3  418.70  4972.3  420.24  4978.4  418.00  4990.4  416.19  4990.9  415.39
  4995.9  415.39  4996.4  416.19  5008.4  418.25  5013.0  421.82  5020.6  424.96
  5029.4  426.43  5065.5  429.73  5122.6  432.18  5173.7  436.21  5266.8  441.45
#Mann=7,-1,0
  4414.9    0.16       0  4699.7    0.05       0  4802.6    0.16       0
  4893.4    0.05       0  4930.2    0.16       0  4990.4    0.07       0
  4996.4    0.16       0
Bank Sta=4596.3,5013
Exp/Cntr=0.3,0.1

Type RM Length L Ch R = 1,3757,67,67,67
BEGIN DESCRIPTION:
Mapping XS db51aa82
END DESCRIPTION:
XS GIS Cut Line= 6
      2847182.94      6995076.52      2847366.32      6995090.62
      2847451.83      6995095.18      2847588.98      6995032.68
      2847710.51      6994949.35      2847970.47      6994788.17
#Sta/Elev= 30
  4391.4  433.12  4453.6  434.97  4483.7  434.44  4543.9  428.29  4563.1  424.69
  4568.1  425.43  4572.2  423.86  4584.0  423.61  4671.7  422.90  4677.2  423.53
  4717.8  423.32  4730.4  423.99  4769.4  423.56  4774.9  424.23  4811.7  423.66
  4973.5  425.64  4979.4  424.45  4988.3  419.96  4991.7  416.10  4992.2  415.30
  4997.2  415.30  4997.7  416.10  5000.6  416.13  5009.2  419.96  5016.0  422.15
  5023.1  426.88  5031.4  427.87  5073.9  429.98  5117.3  433.21  5264.9  441.89
#Mann=3,-1,0
  4391.4    0.16       0  4991.7    0.07       0  4997.7    0.16       0
Bank Sta=4988.3,5009.2
Exp/Cntr=0.3,0.1

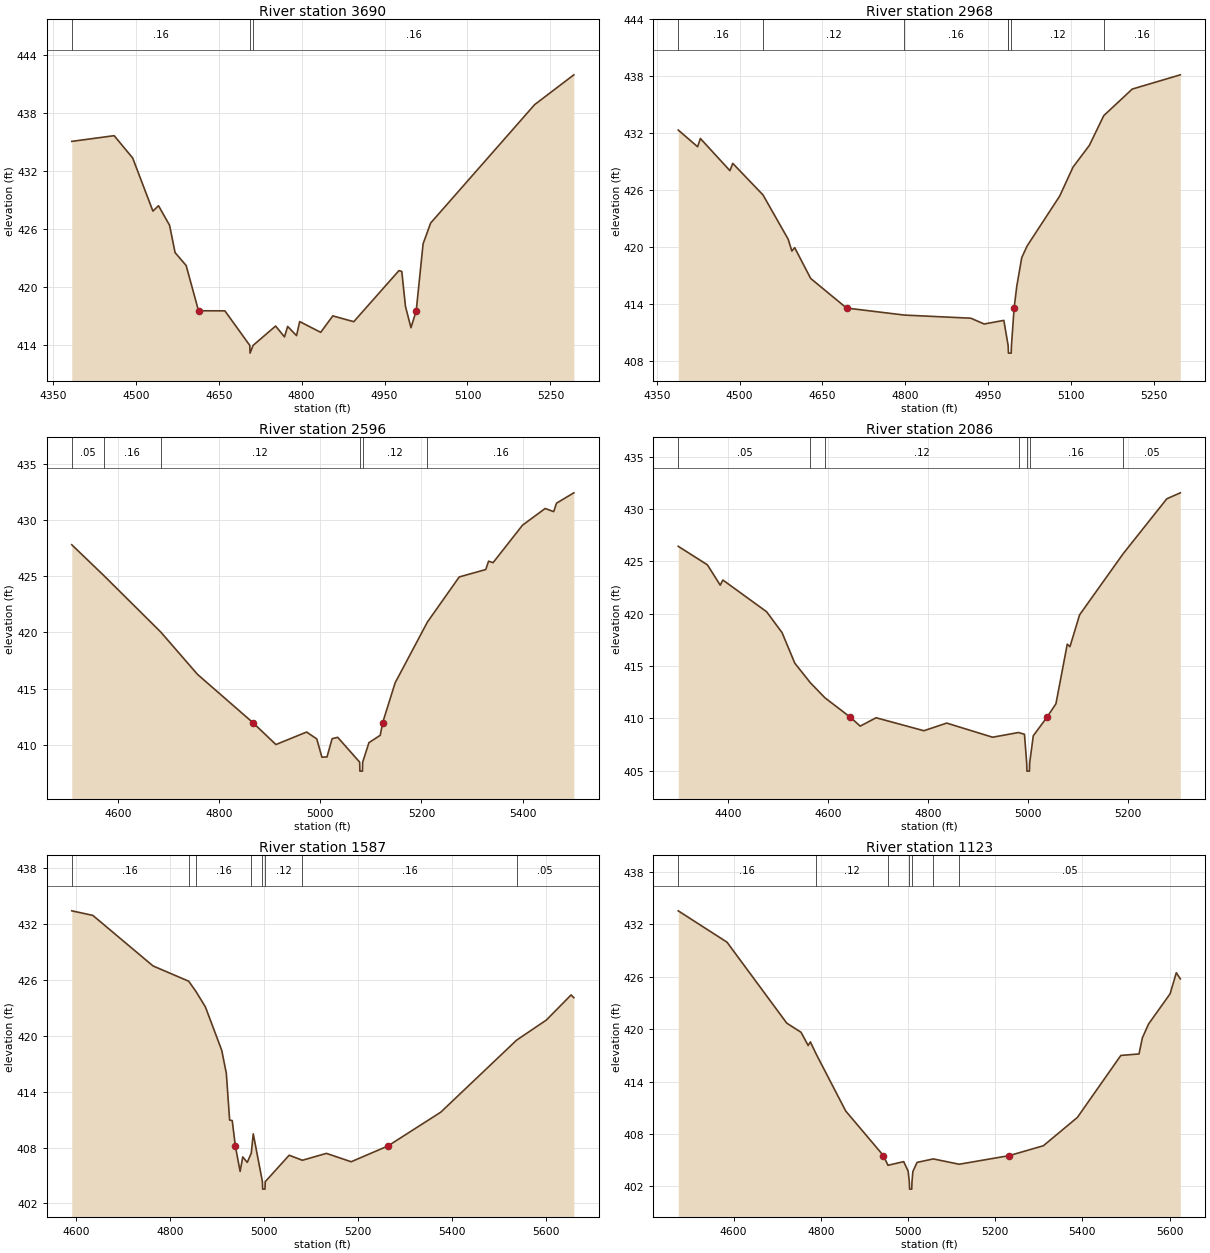
Type RM Length L Ch R = 1,3690,722,722,722
BEGIN DESCRIPTION:
UNT 067 in Running Cr Watershed 7.0
END DESCRIPTION:
XS GIS Cut Line= 4
      2847188.36      6995124.26      2847491.76      6995140.32
      2847819.88      6994961.50      2848016.00      6994840.01
#Sta/Elev= 30
  4384.2  435.05  4460.9  435.64  4494.4  433.33  4531.0  427.84  4541.1  428.40
  4561.1  426.38  4571.1  423.55  4591.1  422.22  4613.5  417.54  4661.2  417.53
  4706.2  413.96  4706.7  413.16  4712.2  413.96  4752.9  415.96  4769.0  414.84
  4774.7  415.92  4790.8  414.97  4796.5  416.42  4834.5  415.31  4856.4  417.01
  4894.3  416.41  4976.0  421.69  4981.2  421.60  4987.8  418.00  4997.8  415.79
  5007.3  417.54  5019.7  424.46  5033.4  426.61  5221.5  438.85  5292.4  441.93
#Mann=3,-1,0
  4384.2    0.16       0  4706.2    0.07       0  4712.2    0.16       0
Bank Sta=4613.5,5007.3
Exp/Cntr=0.3,0.1

Type RM Length L Ch R = 1,2968,372,372,372
BEGIN DESCRIPTION:
UNT 067 in Running Cr Watershed 6.0
END DESCRIPTION:
XS GIS Cut Line= 3
      2847259.07      6995366.89      2847766.93      6995275.00
      2848131.11      6995127.56
#Sta/Elev= 30
  4389.0  432.33  4424.1  430.57  4429.1  431.44  4482.6  428.05  4487.7  428.82
  4542.5  425.49  4588.1  420.82  4594.7  419.58  4599.8  419.94  4628.8  416.69
  4693.8  413.57  4798.5  412.83  4918.8  412.50  4942.9  411.89  4978.5  412.27
  4985.3  409.96  4986.3  409.62  4986.8  408.82  4991.8  408.82  4992.3  409.62
  4997.1  413.57  5001.9  415.86  5010.9  418.88  5020.7  420.12  5079.7  425.38
  5103.8  428.43  5133.3  430.71  5159.4  433.85  5211.0  436.65  5298.0  438.15
#Mann=7,-1,0
  4389.0    0.16       0  4542.5    0.12       0  4798.5    0.16       0
  4985.3    0.12       0  4986.3    0.07       0  4992.3    0.12       0
  5159.4    0.16       0
Bank Sta=4693.8,4997.1
Exp/Cntr=0.3,0.1

Type RM Length L Ch R = 1,2596,510,510,510
BEGIN DESCRIPTION:
UNT 067 in Running Cr Watershed 5.0
END DESCRIPTION:
XS GIS Cut Line= 3
      2847355.50      6995616.88      2847915.37      6995533.55
      2848298.14      6995343.47
#Sta/Elev= 30
  4508.1  427.79  4571.2  425.07  4684.2  420.04  4756.9  416.28  4866.4  412.00
  4912.0  410.05  4972.7  411.16  4992.9  410.55  5003.0  408.93  5013.1  408.95
  5023.2  410.57  5034.3  410.69  5077.7  408.49  5078.2  407.69  5083.2  407.69
  5083.7  408.49  5096.1  410.22  5118.4  410.87  5123.3  412.00  5147.9  415.53
  5211.7  420.92  5274.7  424.93  5327.2  425.59  5332.8  426.33  5341.7  426.20
  5400.0  429.53  5444.8  431.01  5461.6  430.73  5467.2  431.48  5501.5  432.40
#Mann=6,-1,0
  4508.1    0.05       0  4571.2    0.16       0  4684.2    0.12       0
  5077.7    0.07       0  5083.7    0.12       0  5211.7    0.16       0
Bank Sta=4866.4,5123.3
Exp/Cntr=0.3,0.1

Type RM Length L Ch R = 1,2086,499,499,499
BEGIN DESCRIPTION:
UNT 067 in Running Cr Watershed 4.0
END DESCRIPTION:
XS GIS Cut Line= 4
      2847462.29      6995908.53      2848040.88      6995703.43
      2848179.62      6995678.39      2848411.35      6995588.78
#Sta/Elev= 30
  4300.7  426.44  4359.0  424.67  4384.6  422.73  4389.9  423.22  4477.3  420.19
  4508.1  418.20  4533.7  415.27  4564.8  413.40  4594.0  411.96  4644.6  410.11
  4664.3  409.26  4696.1  410.06  4791.6  408.82  4837.2  409.55  4928.9  408.20
  4980.7  408.65  4992.6  408.48  4997.0  405.76  4997.5  404.96  5002.5  404.96
  5003.0  405.76  5010.2  408.34  5037.6  410.11  5055.5  411.40  5078.1  417.09
  5083.5  416.85  5102.7  419.89  5189.6  425.72  5277.0  430.98  5304.0  431.55
#Mann=7,-1,0
  4300.7    0.05       0  4564.8    0.16       0  4594.0    0.12       0
  4980.7    0.16       0  4997.0    0.07       0  5003.0    0.16       0
  5189.6    0.05       0
Bank Sta=4644.6,5037.6
Exp/Cntr=0.3,0.1

Type RM Length L Ch R = 1,1587,464,464,464
BEGIN DESCRIPTION:
UNT 067 in Running Cr Watershed 3.0
END DESCRIPTION:
XS GIS Cut Line= 3
      2847589.85      6996320.00      2848046.59      6996093.67
      2848529.61      6995809.79
#Sta/Elev= 30
  4590.1  433.42  4635.0  432.93  4763.3  427.50  4839.3  425.86  4854.5  424.78
  4874.9  423.10  4909.7  418.44  4919.5  415.97  4926.5  410.95  4932.1  410.89
  4938.7  408.16  4948.9  405.43  4954.5  406.99  4964.1  406.40  4972.6  407.39
  4976.9  409.47  4996.4  404.33  4996.9  403.53  5001.9  403.53  5002.4  404.33
  5053.4  407.17  5081.6  406.63  5132.8  407.37  5185.5  406.47  5263.7  408.16
  5376.4  411.79  5538.1  419.53  5601.5  421.69  5654.3  424.39  5660.1  424.09
#Mann=8,-1,0
  4590.1    0.16       0  4839.3    0.05       0  4854.5    0.16       0
  4972.6    0.12       0  4996.4    0.07       0  5002.4    0.12       0
  5081.6    0.16       0  5538.1    0.05       0
Bank Sta=4938.7,5263.7
Exp/Cntr=0.3,0.1

Type RM Length L Ch R = 1,1123,389,389,389
BEGIN DESCRIPTION:
UNT 067 in Running Cr Watershed 2.0
END DESCRIPTION:
XS GIS Cut Line= 3
      2847649.75      6996473.65      2848259.12      6996340.84
      2848605.47      6995942.40
#Sta/Elev= 30
  4472.9  433.56  4584.8  429.97  4721.8  420.70  4754.6  419.65  4770.9  418.14
  4776.0  418.55  4789.6  417.13  4857.0  410.64  4943.5  405.53  4954.0  404.42
  4990.0  404.84  5000.2  403.76  5003.0  402.49  5003.5  401.69  5008.5  401.69
  5009.0  402.49  5011.1  403.71  5020.7  404.75  5057.9  405.15  5117.3  404.54
  5232.4  405.53  5310.5  406.66  5388.4  409.90  5488.1  417.00  5529.8  417.17
  5537.4  419.00  5551.7  420.60  5601.1  424.06  5615.3  426.47  5624.5  425.77
#Mann=7,-1,0
  4472.9    0.16       0  4789.6    0.12       0  4954.0    0.16       0
  5003.0    0.07       0  5009.0    0.16       0  5057.9    0.12       0
  5117.3    0.05       0
Bank Sta=4943.5,5232.4
Exp/Cntr=0.3,0.1

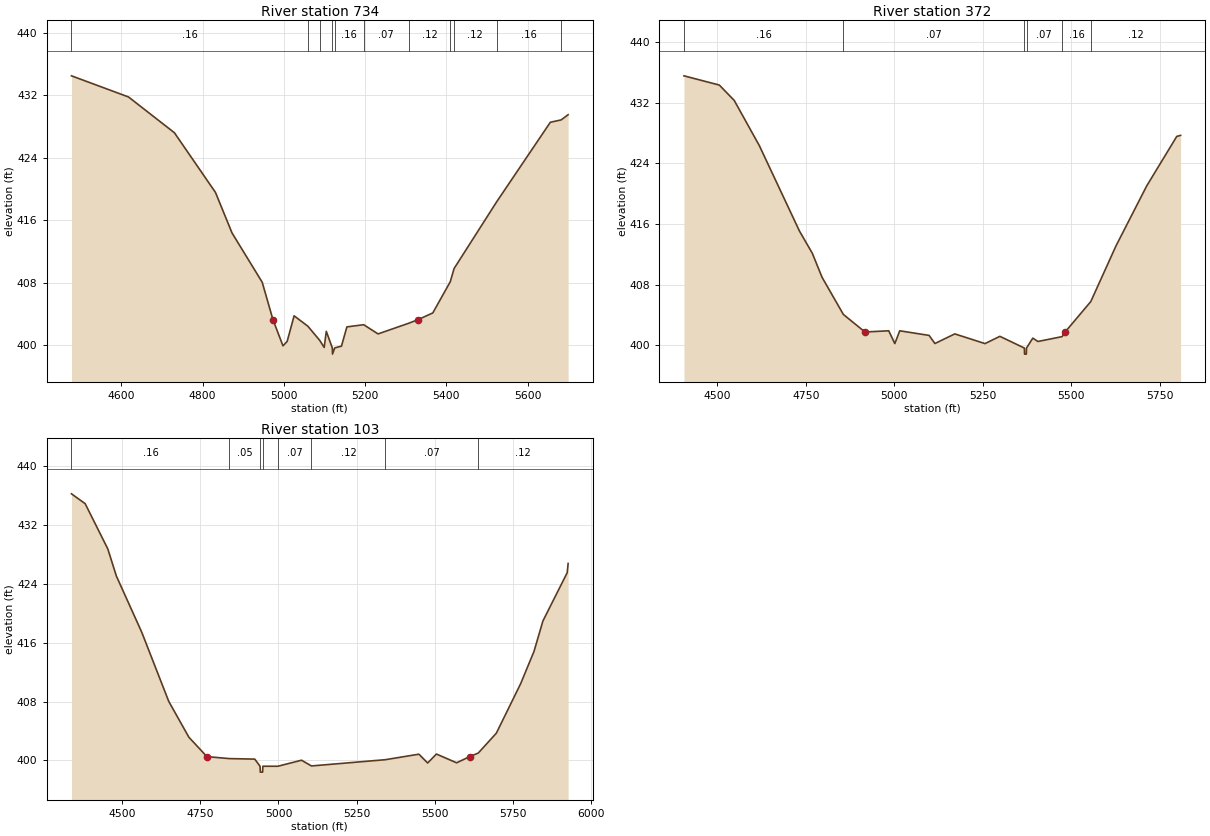
Type RM Length L Ch R = 1,734,362,362,362
BEGIN DESCRIPTION:
Mapping XS 9329a370
END DESCRIPTION:
XS GIS Cut Line= 4
      2847623.74      6996572.62      2848071.62      6996697.61
      2848251.31      6996747.09      2848764.36      6996497.07
#Sta/Elev= 30
  4477.5  434.49  4617.8  431.78  4730.7  427.20  4831.8  419.55  4872.6  414.35
  4946.8  408.04  4973.3  403.24  4997.9  399.89  5008.2  400.46  5025.3  403.74
  5059.1  402.41  5088.4  400.59  5099.3  399.69  5104.5  401.75  5119.3  399.63
  5119.8  398.83  5125.3  399.63  5141.8  399.85  5155.2  402.32  5196.4  402.60
  5231.9  401.42  5307.5  402.79  5330.0  403.24  5366.6  404.11  5409.5  408.10
  5419.0  409.80  5523.4  418.32  5655.8  428.54  5682.4  428.84  5699.6  429.51
#Mann=11,-1,0
  4477.5    0.16       0  5059.1    0.12       0  5088.4    0.16       0
  5119.3    0.07       0  5125.3    0.16       0  5196.4    0.07       0
  5307.5    0.12       0  5409.5    0.16       0  5419.0    0.12       0
  5523.4    0.16       0  5682.4    0.05       0
Bank Sta=4973.3,5330
Exp/Cntr=0.3,0.1

Type RM Length L Ch R = 1,372,269,269,269
BEGIN DESCRIPTION:
Mapping XS a232cc65
END DESCRIPTION:
XS GIS Cut Line= 4
      2847623.69      6996655.93      2847954.43      6997051.78
      2848246.10      6996971.05      2848709.63      6996614.28
#Sta/Elev= 30
  4405.5  435.57  4505.5  434.35  4547.6  432.32  4618.7  426.34  4731.9  415.08
  4768.3  412.14  4795.7  408.98  4856.0  404.07  4917.1  401.75  4984.2  401.91
  5001.4  400.22  5015.3  401.91  5098.3  401.30  5114.7  400.23  5170.9  401.50
  5256.3  400.22  5298.3  401.18  5367.5  399.63  5368.0  398.83  5373.0  398.83
  5373.5  399.63  5391.3  400.94  5405.8  400.50  5474.1  401.14  5482.6  401.75
  5555.2  405.77  5626.4  413.12  5713.0  421.02  5798.1  427.57  5808.9  427.71
#Mann=6,-1,0
  4405.5    0.16       0  4856.0    0.07       0  5367.5    0.07       0
  5373.5    0.07       0  5474.1    0.16       0  5555.2    0.12       0
Bank Sta=4917.1,5482.6
Exp/Cntr=0.3,0.1

Type RM Length L Ch R = 1,103,0,0,0
BEGIN DESCRIPTION:
UNT 067 in Running Cr Watershed 1.0
END DESCRIPTION:
XS GIS Cut Line= 4
      2847624.99      6996774.98      2847968.75      6997299.17
      2848109.38      6997269.22      2848721.36      6996727.41
#Sta/Elev= 30
  4338.3  436.26  4382.0  434.92  4454.4  428.77  4481.8  425.08  4562.9  417.44
  4649.2  408.04  4713.6  403.16  4771.3  400.52  4843.1  400.25  4924.3  400.18
  4941.2  399.21  4942.1  398.41  4949.4  398.41  4950.2  399.21  4998.3  399.21
  5073.8  400.03  5105.6  399.25  5341.8  400.10  5449.2  400.85  5477.1  399.65
  5505.2  400.87  5569.6  399.68  5611.8  400.52  5639.1  401.01  5696.8  403.71
  5774.6  410.45  5817.2  414.83  5845.7  418.97  5923.4  425.54  5926.3  426.78
#Mann=8,-1,0
  4338.3    0.16       0  4843.1    0.05       0  4941.2    0.07       0
  4950.2    0.05       0  4998.3    0.07       0  5105.6    0.12       0
  5341.8    0.07       0  5639.1    0.12       0
Bank Sta=4771.3,5611.8
Exp/Cntr=0.3,0.1

Chan Stop Cuts=-1