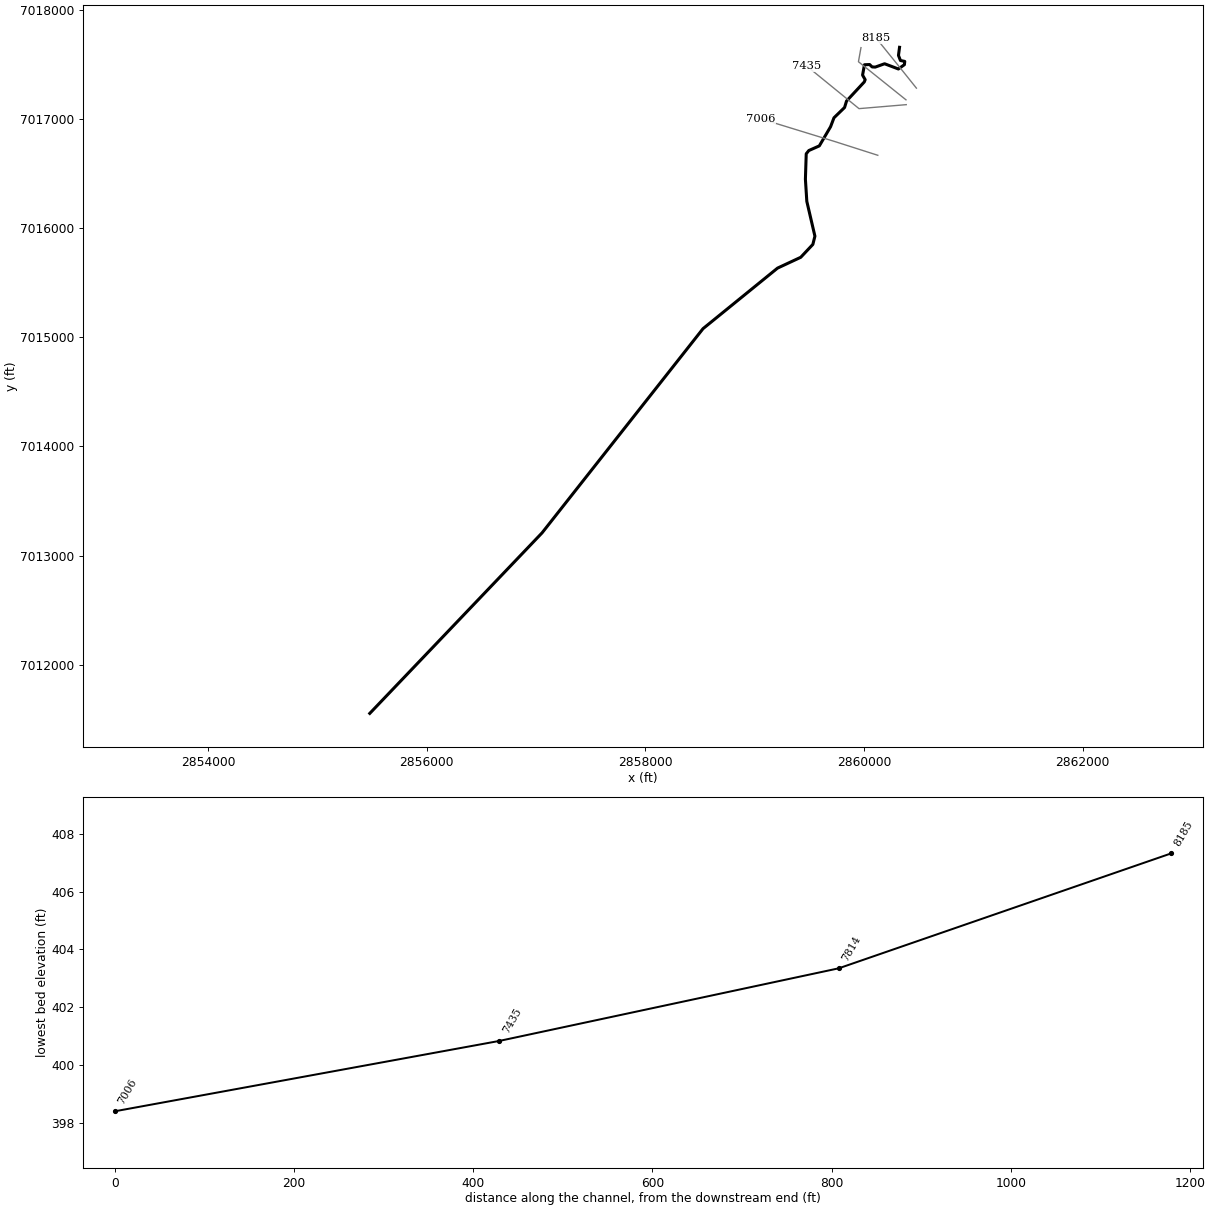
--- UNT 068 in Running Cr Watershed.prj (project) ---

Proj Title=UNT 068 in Running Cr Watershed Base Level Engineering
Current Plan=p01
Default Exp/Contr=0.3,0.1
English Units
Geom File=g01
Flow File=f01
Plan File=p01
BEGIN DESCRIPTION:
UNT 068 in Running Cr Watershed
END DESCRIPTION:

--- UNT 068 in Running Cr Watershed.p01 (plan) ---

Plan Title=Multiple Run
Short Identifier=Multiple
Geom File=g01
Flow File=f01
Subcritical Flow
K Sum by GR= 0
Std Step Tol= 0.01
Critical Tol= 0.01
Num of Std Step Trials= 20
Max Error Tol= 0.3
Flow Tol Ratio= 0.001
Split Flow NTrial= 30
Split Flow Tol= 0.02
Split Flow Ratio= 0.02
Log Output Level= 0
Friction Slope Method= 1
Unsteady Friction Slope Method= 2
Unsteady Bridges Friction Slope Method= 1
Parabolic Critical Depth
Global Vel Dist=  1 , 1 , 1
Global Log Level= 0
CheckData=True
Encroach Param= -1, 0, 0, 0
BEGIN DESCRIPTION:
Multiple Run
END DESCRIPTION:

--- UNT 068 in Running Cr Watershed.f01 (steady flow) ---

Flow Title=Multiple
Number of Profiles=7
Profile Names=10-year,25-year,50-year,1pct_min,100-year,1pct_plu,500-year
River Rch & RM= UNT 068 in Runni,Reach-1,8185
     480     633     757     450     897    1791    1264
Boundary for River Rch & Prof#=UNT 068 in Runni,Reach-1,1
Up Type=0
Dn Type=3
Dn Slope=0.005
Boundary for River Rch & Prof#=UNT 068 in Runni,Reach-1,2
Up Type=0
Dn Type=3
Dn Slope=0.005
Boundary for River Rch & Prof#=UNT 068 in Runni,Reach-1,3
Up Type=0
Dn Type=3
Dn Slope=0.005
Boundary for River Rch & Prof#=UNT 068 in Runni,Reach-1,4
Up Type=0
Dn Type=3
Dn Slope=0.005
Boundary for River Rch & Prof#=UNT 068 in Runni,Reach-1,5
Up Type=0
Dn Type=3
Dn Slope=0.005
Boundary for River Rch & Prof#=UNT 068 in Runni,Reach-1,6
Up Type=0
Dn Type=3
Dn Slope=0.005
Boundary for River Rch & Prof#=UNT 068 in Runni,Reach-1,7
Up Type=0
Dn Type=3
Dn Slope=0.005

--- UNT 068 in Running Cr Watershed.g01 (geometry) ---

Geom Title=Existing Conditions

River Reach=UNT 068 in Runni,Reach-1
Reach XY= 30
      2860325.99      7017654.73      2860316.27      7017580.42
      2860334.32      7017533.89      2860373.91      7017525.56
      2860370.43      7017495.70      2860315.57      7017456.12
      2860189.18      7017504.03      2860103.77      7017473.48
      2860075.00      7017475.00      2860052.38      7017496.92
      2860004.94      7017494.94      2859987.86      7017400.00
      2860011.54      7017358.22      2860003.18      7017337.33
      2859841.25      7017162.98      2859822.97      7017103.39
      2859726.15      7017009.28      2859695.00      7016927.36
      2859592.09      7016752.00      2859495.95      7016709.35
      2859472.25      7016679.56      2859464.81      7016447.33
      2859477.67      7016244.22      2859551.79      7015925.34
      2859532.92      7015849.87      2859422.07      7015731.95
      2859209.81      7015632.89      2858528.21      7015078.64
      2857055.48      7013208.90      2855479.19      7011555.82

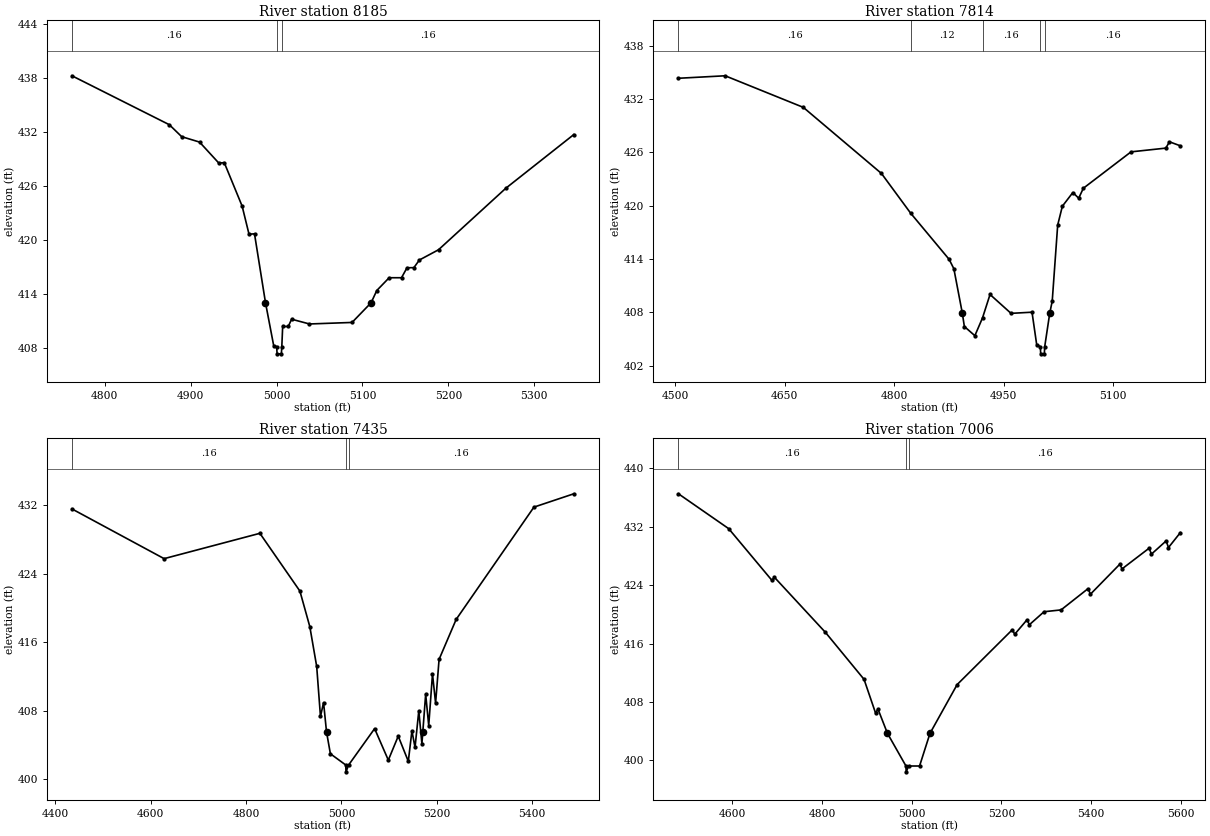
Type RM Length L Ch R = 1,8185,371,371,371
BEGIN DESCRIPTION:
UNT 068 in Running Cr Watershed 20.0
END DESCRIPTION:
XS GIS Cut Line= 3
      2860480.33      7017280.84      2860325.00      7017475.00
      2860114.05      7017736.34
#Sta/Elev= 30
  4761.7  438.23  4875.1  432.79  4889.5  431.46  4910.3  430.86  4932.7  428.53
  4939.1  428.57  4959.9  423.74  4967.9  420.62  4974.3  420.66  4987.1  413.00
  4996.7  408.20  5000.1  408.12  5000.6  407.32  5005.6  407.32  5006.1  408.12
  5007.1  410.36  5013.6  410.36  5017.5  411.17  5038.3  410.64  5087.9  410.81
  5110.1  413.00  5116.7  414.36  5131.1  415.78  5145.5  415.78  5151.9  416.89
  5159.9  416.90  5166.3  417.75  5188.6  418.89  5267.0  425.73  5346.2  431.70
#Mann=3,-1,0
  4761.7    0.16       0  5000.1    0.07       0  5006.1    0.16       0
Bank Sta=4987.1,5110.1
Exp/Cntr=0.3,0.1

Type RM Length L Ch R = 1,7814,379,379,379
BEGIN DESCRIPTION:
UNT 068 in Running Cr Watershed 19.0
END DESCRIPTION:
XS GIS Cut Line= 3
      2860384.91      7017173.81      2859950.02      7017522.76
      2859973.19      7017651.51
#Sta/Elev= 30
  4504.1  434.32  4568.2  434.60  4675.4  431.05  4782.6  423.62  4822.7  419.15
  4875.4  413.97  4881.9  412.91  4893.5  407.92  4896.3  406.42  4910.7  405.39
  4921.2  407.39  4931.5  410.02  4960.3  407.90  4989.1  408.03  4995.5  404.38
  5000.5  404.15  5001.0  403.35  5006.0  403.35  5006.5  404.15  5013.4  407.92
  5016.8  409.27  5024.3  417.82  5030.7  419.94  5045.1  421.48  5053.1  420.84
  5059.5  421.96  5124.9  426.05  5172.6  426.47  5177.6  427.18  5192.5  426.73
#Mann=5,-1,0
  4504.1    0.16       0  4822.7    0.12       0  4921.2    0.16       0
  5000.5    0.07       0  5006.5    0.16       0
Bank Sta=4893.5,5013.4
Exp/Cntr=0.3,0.1

Type RM Length L Ch R = 1,7435,429,429,429
BEGIN DESCRIPTION:
UNT 068 in Running Cr Watershed 18.0
END DESCRIPTION:
XS GIS Cut Line= 3
      2860387.49      7017129.53      2859955.23      7017093.07
      2859476.07      7017483.69
#Sta/Elev= 30
  4435.1  431.56  4628.3  425.75  4829.0  428.71  4912.9  421.96  4933.7  417.80
  4948.1  413.15  4956.0  407.31  4962.5  408.93  4968.7  405.50  4976.8  402.95
  5009.0  401.64  5009.5  400.84  5015.0  401.64  5069.5  405.89  5098.2  402.21
  5119.0  405.01  5140.1  402.07  5147.7  405.63  5154.2  403.69  5162.1  407.98
  5168.6  404.12  5170.5  405.50  5176.5  409.92  5182.9  406.25  5190.8  412.27
  5197.3  408.87  5204.6  413.98  5240.4  418.65  5403.4  431.77  5487.1  433.33
#Mann=3,-1,0
  4435.1    0.16       0  5009.0    0.07       0  5015.0    0.16       0
Bank Sta=4968.7,5170.5
Exp/Cntr=0.3,0.1

Type RM Length L Ch R = 1,7006,0,0,0
BEGIN DESCRIPTION:
UNT 068 in Running Cr Watershed 17.0
END DESCRIPTION:
XS GIS Cut Line= 3
      2860127.13      7016665.98      2859736.48      7016790.99
      2859059.66      7016999.24
#Sta/Elev= 30
  4480.3  436.53  4592.3  431.75  4688.8  424.65  4694.1  425.09  4808.0  417.52
  4893.9  411.09  4919.6  406.46  4924.9  407.02  4946.1  403.68  4987.3  399.21
  4987.8  398.41  4993.3  399.21  5017.6  399.21  5040.8  403.68  5101.3  410.37
  5224.4  417.90  5229.6  417.27  5257.1  419.26  5262.3  418.58  5295.0  420.36
  5332.9  420.61  5393.1  423.53  5398.3  422.76  5463.7  426.87  5468.9  426.24
  5529.1  429.07  5534.3  428.26  5567.0  430.07  5572.2  429.16  5598.6  431.20
#Mann=3,-1,0
  4480.3    0.16       0  4987.3    0.07       0  4993.3    0.16       0
Bank Sta=4946.1,5040.8
Exp/Cntr=0.3,0.1

Chan Stop Cuts=-1