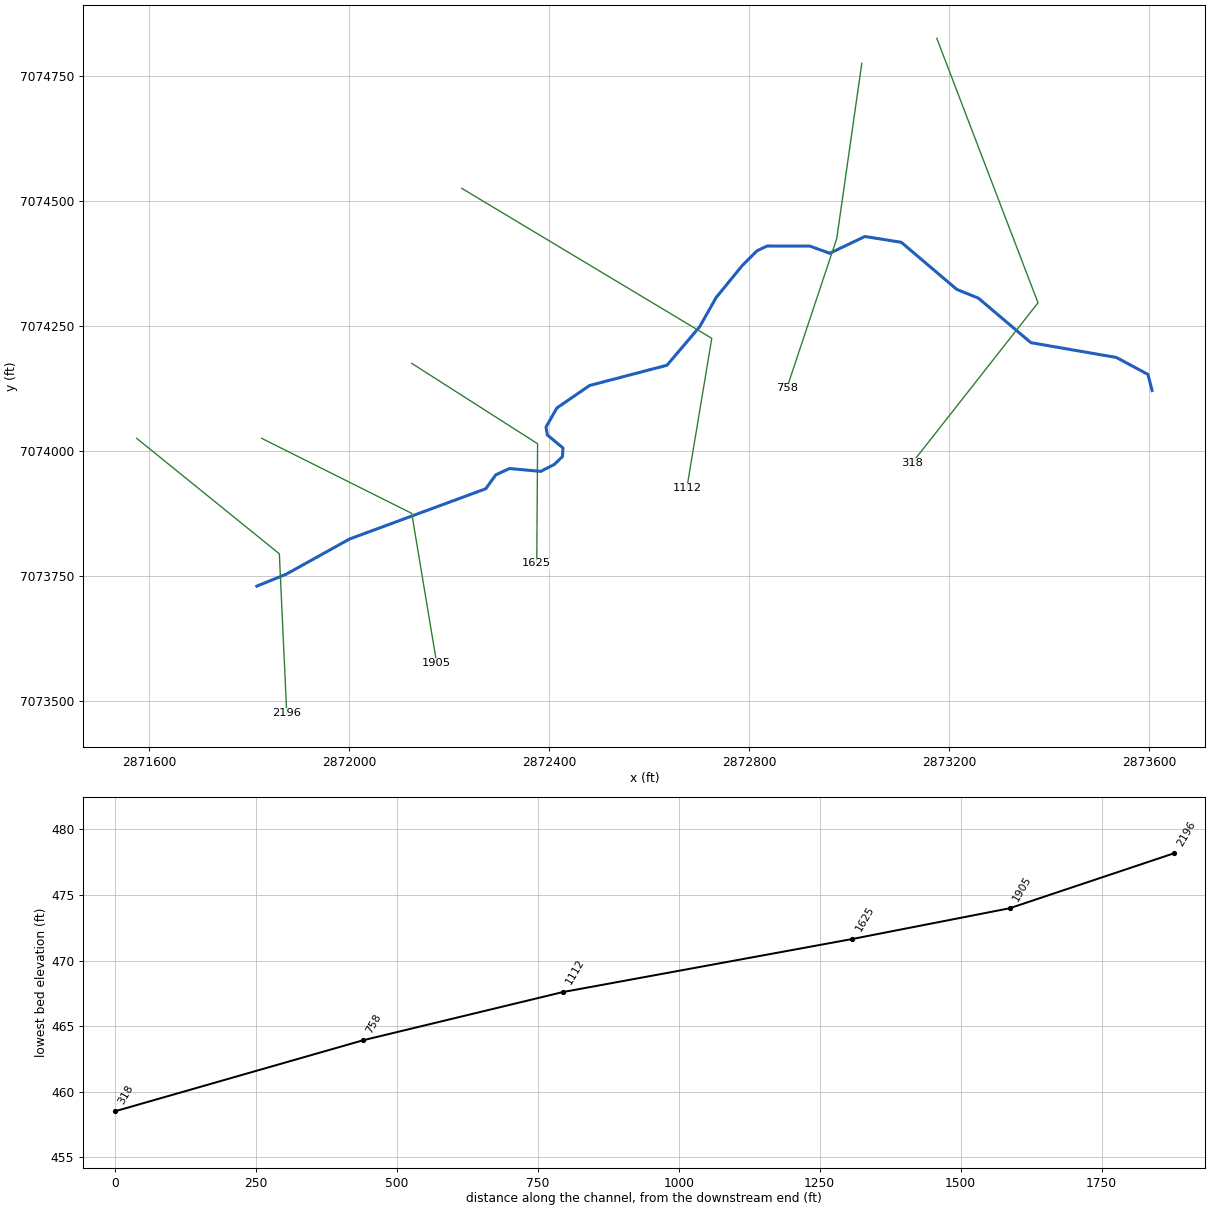
--- UNT 069 in Running Cr Watershed.prj (project) ---

Proj Title=UNT 069 in Running Cr Watershed Base Level Engineering
Current Plan=p01
Default Exp/Contr=0.3,0.1
English Units
Geom File=g01
Flow File=f01
Plan File=p01
BEGIN DESCRIPTION:
UNT 069 in Running Cr Watershed
END DESCRIPTION:

--- UNT 069 in Running Cr Watershed.p01 (plan) ---

Plan Title=Multiple Run
Short Identifier=Multiple
Geom File=g01
Flow File=f01
Subcritical Flow
K Sum by GR= 0
Std Step Tol= 0.01
Critical Tol= 0.01
Num of Std Step Trials= 20
Max Error Tol= 0.3
Flow Tol Ratio= 0.001
Split Flow NTrial= 30
Split Flow Tol= 0.02
Split Flow Ratio= 0.02
Log Output Level= 0
Friction Slope Method= 1
Unsteady Friction Slope Method= 2
Unsteady Bridges Friction Slope Method= 1
Parabolic Critical Depth
Global Vel Dist=  1 , 1 , 1
Global Log Level= 0
CheckData=True
Encroach Param= -1, 0, 0, 0
BEGIN DESCRIPTION:
Multiple Run
END DESCRIPTION:

--- UNT 069 in Running Cr Watershed.f01 (steady flow) ---

Flow Title=Multiple
Number of Profiles=7
Profile Names=10-year,25-year,50-year,1pct_min,100-year,1pct_plu,500-year
River Rch & RM= UNT 069 in Runni,Reach-1,2196
     277     350     406     235     469     936     621
Boundary for River Rch & Prof#=UNT 069 in Runni,Reach-1,1
Up Type=0
Dn Type=3
Dn Slope=0.005
Boundary for River Rch & Prof#=UNT 069 in Runni,Reach-1,2
Up Type=0
Dn Type=3
Dn Slope=0.005
Boundary for River Rch & Prof#=UNT 069 in Runni,Reach-1,3
Up Type=0
Dn Type=3
Dn Slope=0.005
Boundary for River Rch & Prof#=UNT 069 in Runni,Reach-1,4
Up Type=0
Dn Type=3
Dn Slope=0.005
Boundary for River Rch & Prof#=UNT 069 in Runni,Reach-1,5
Up Type=0
Dn Type=3
Dn Slope=0.005
Boundary for River Rch & Prof#=UNT 069 in Runni,Reach-1,6
Up Type=0
Dn Type=3
Dn Slope=0.005
Boundary for River Rch & Prof#=UNT 069 in Runni,Reach-1,7
Up Type=0
Dn Type=3
Dn Slope=0.005

--- UNT 069 in Running Cr Watershed.g01 (geometry) ---

Geom Title=Existing Conditions

River Reach=UNT 069 in Runni,Reach-1
Reach XY= 30
      2871815.19      7073729.46      2871874.04      7073753.41
      2872000.60      7073823.73      2872273.00      7073924.25
      2872293.07      7073952.04      2872320.51      7073964.69
      2872383.07      7073958.97      2872409.98      7073972.86
      2872426.47      7073988.48      2872427.34      7074005.84
      2872396.09      7074031.89      2872393.49      7074047.51
      2872415.19      7074085.71      2872480.59      7074130.71
      2872635.44      7074171.26      2872700.64      7074248.02
      2872733.80      7074306.74      2872786.11      7074370.81
      2872815.69      7074400.29      2872835.59      7074409.66
      2872920.93      7074409.57      2872960.86      7074395.17
      2873031.33      7074428.72      2873104.01      7074417.10
      2873215.00      7074322.89      2873258.18      7074305.42
      2873363.22      7074216.36      2873534.02      7074186.81
      2873597.17      7074153.01      2873605.59      7074120.71

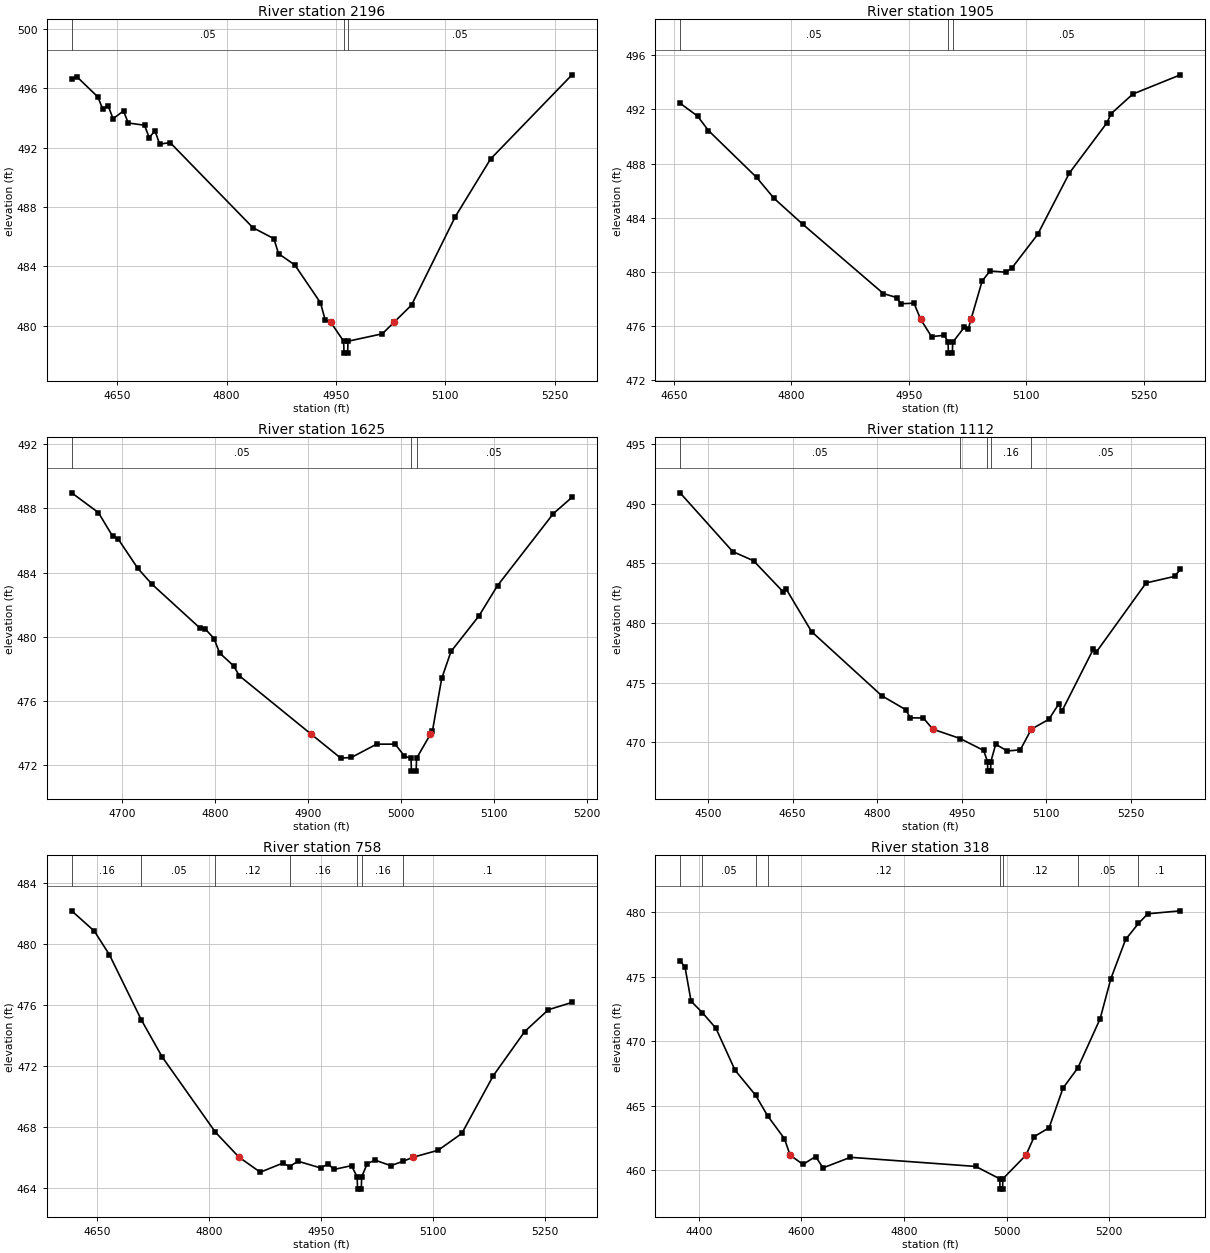
Type RM Length L Ch R = 1,2196,291,291,291
BEGIN DESCRIPTION:
UNT 069 in Running Cr Watershed 6.0
END DESCRIPTION:
XS GIS Cut Line= 3
      2871575.01      7074024.99      2871860.25      7073794.17
      2871875.00      7073475.05
#Sta/Elev= 30
  4587.5  496.63  4594.7  496.76  4623.4  495.40  4629.9  494.61  4637.8  494.77
  4644.3  493.94  4658.6  494.46  4665.1  493.65  4687.4  493.50  4693.8  492.67
  4701.8  493.12  4708.2  492.23  4722.6  492.33  4836.1  486.61  4864.9  485.87
  4871.3  484.86  4893.6  484.10  4928.8  481.56  4935.3  480.40  4943.0  480.24
  4960.6  478.97  4961.1  478.17  4966.1  478.17  4966.6  478.97  5013.7  479.47
  5029.6  480.24  5053.7  481.40  5113.8  487.35  5162.2  491.23  5273.9  496.89
#Mann=3,-1,0
  4587.5    0.05       0  4960.6    0.03       0  4966.6    0.05       0
Bank Sta=4943,5029.6
Exp/Cntr=0.3,0.1

Type RM Length L Ch R = 1,1905,280,280,280
BEGIN DESCRIPTION:
UNT 069 in Running Cr Watershed 5.0
END DESCRIPTION:
XS GIS Cut Line= 3
      2871825.04      7074024.98      2872125.00      7073875.00
      2872175.00      7073575.00
#Sta/Elev= 30
  4657.6  492.46  4679.9  491.51  4693.9  490.44  4755.4  486.98  4777.7  485.43
  4814.1  483.53  4917.5  478.39  4934.3  478.10  4939.9  477.64  4956.6  477.68
  4965.2  476.48  4979.0  475.21  4995.5  475.31  5000.1  474.79  5000.6  473.99
  5005.6  473.99  5006.1  474.79  5020.8  475.90  5025.9  475.76  5029.4  476.48
  5043.7  479.32  5053.8  480.06  5074.1  479.97  5081.7  480.28  5114.6  482.76
  5155.2  487.30  5203.3  491.02  5208.4  491.68  5236.3  493.14  5297.1  494.56
#Mann=3,-1,0
  4657.6    0.05       0  5000.1    0.03       0  5006.1    0.05       0
Bank Sta=4965.2,5029.4
Exp/Cntr=0.3,0.1

Type RM Length L Ch R = 1,1625,513,513,513
BEGIN DESCRIPTION:
UNT 069 in Running Cr Watershed 4.0
END DESCRIPTION:
XS GIS Cut Line= 3
      2872125.03      7074174.98      2872376.66      7074014.27
      2872375.00      7073774.95
#Sta/Elev= 30
  4645.8  488.97  4674.5  487.74  4689.8  486.27  4695.7  486.10  4717.0  484.26
  4732.1  483.28  4783.7  480.55  4789.6  480.48  4798.9  479.89  4804.8  479.00
  4820.0  478.19  4826.0  477.58  4903.3  473.94  4935.1  472.45  4946.5  472.49
  4973.6  473.32  4993.6  473.32  5003.6  472.57  5010.6  472.44  5011.1  471.64
  5016.1  471.64  5016.6  472.44  5031.5  473.94  5033.6  474.12  5043.6  477.41
  5053.6  479.09  5083.6  481.30  5103.6  483.19  5163.7  487.68  5183.7  488.69
#Mann=3,-1,0
  4645.8    0.05       0  5010.6    0.03       0  5016.6    0.05       0
Bank Sta=4903.3,5031.5
Exp/Cntr=0.3,0.1

Type RM Length L Ch R = 1,1112,354,354,354
BEGIN DESCRIPTION:
UNT 069 in Running Cr Watershed 3.0
END DESCRIPTION:
XS GIS Cut Line= 3
      2872225.02      7074524.99      2872725.00      7074225.00
      2872675.00      7073925.01
#Sta/Elev= 30
  4450.6  490.92  4543.9  486.00  4580.8  485.23  4633.3  482.63  4639.1  482.83
  4683.8  479.29  4808.2  473.92  4851.0  472.74  4858.7  472.07  4882.1  472.05
  4898.6  471.12  4947.3  470.33  4989.0  469.33  4995.7  468.40  4996.2  467.60
  5001.2  467.60  5001.7  468.40  5010.3  469.85  5030.8  469.29  5053.9  469.38
  5072.6  471.04  5073.6  471.12  5104.6  471.94  5122.4  473.25  5127.4  472.60
  5183.2  477.80  5188.3  477.55  5277.0  483.37  5327.7  483.92  5337.8  484.53
#Mann=5,-1,0
  4450.6    0.05       0  4947.3    0.16       0  4995.7    0.07       0
  5001.7    0.16       0  5072.6    0.05       0
Bank Sta=4898.6,5073.6
Exp/Cntr=0.3,0.1

Type RM Length L Ch R = 1,758,440,440,440
BEGIN DESCRIPTION:
UNT 069 in Running Cr Watershed 2.0
END DESCRIPTION:
XS GIS Cut Line= 3
      2873025.00      7074774.99      2872975.00      7074425.00
      2872874.99      7074124.97
#Sta/Elev= 30
  4616.5  482.19  4646.8  480.86  4667.0  479.31  4709.9  475.02  4737.7  472.60
  4809.0  467.66  4840.4  466.03  4869.0  465.04  4899.3  465.64  4908.1  465.41
  4919.5  465.76  4949.8  465.32  4959.9  465.59  4967.5  465.22  4991.1  465.47
  4998.7  464.73  4999.2  463.93  5004.2  463.93  5004.7  464.73  5012.2  465.61
  5022.7  465.83  5043.8  465.47  5060.2  465.76  5074.1  466.03  5107.1  466.48
  5138.7  467.58  5180.9  471.37  5223.0  474.27  5254.6  475.70  5286.3  476.18
#Mann=7,-1,0
  4616.5    0.16       0  4709.9    0.05       0  4809.0    0.12       0
  4908.1    0.16       0  4998.7    0.07       0  5004.7    0.16       0
  5060.2     0.1       0
Bank Sta=4840.4,5074.1
Exp/Cntr=0.3,0.1

Type RM Length L Ch R = 1,318,0,0,0
BEGIN DESCRIPTION:
UNT 069 in Running Cr Watershed 1.0
END DESCRIPTION:
XS GIS Cut Line= 3
      2873175.01      7074824.99      2873377.37      7074296.12
      2873124.99      7073974.99
#Sta/Elev= 30
  4363.7  476.26  4373.4  475.74  4385.1  473.11  4407.0  472.22  4433.5  471.01
  4470.8  467.75  4510.8  465.81  4534.6  464.19  4567.1  462.43  4578.0  461.16
  4603.1  460.44  4627.8  461.05  4642.1  460.17  4695.6  460.99  4939.8  460.28
  4986.5  459.32  4987.0  458.52  4992.0  458.52  4992.5  459.32  5037.6  461.16
  5053.7  462.60  5082.6  463.28  5109.8  466.37  5138.5  467.92  5182.0  471.74
  5202.8  474.84  5231.7  477.90  5256.7  479.14  5274.8  479.89  5338.4  480.12
#Mann=8,-1,0
  4363.7    0.16       0  4407.0    0.05       0  4510.8    0.16       0
  4534.6    0.12       0  4986.5    0.07       0  4992.5    0.12       0
  5138.5    0.05       0  5256.7     0.1       0
Bank Sta=4578,5037.6
Exp/Cntr=0.3,0.1

Chan Stop Cuts=-1