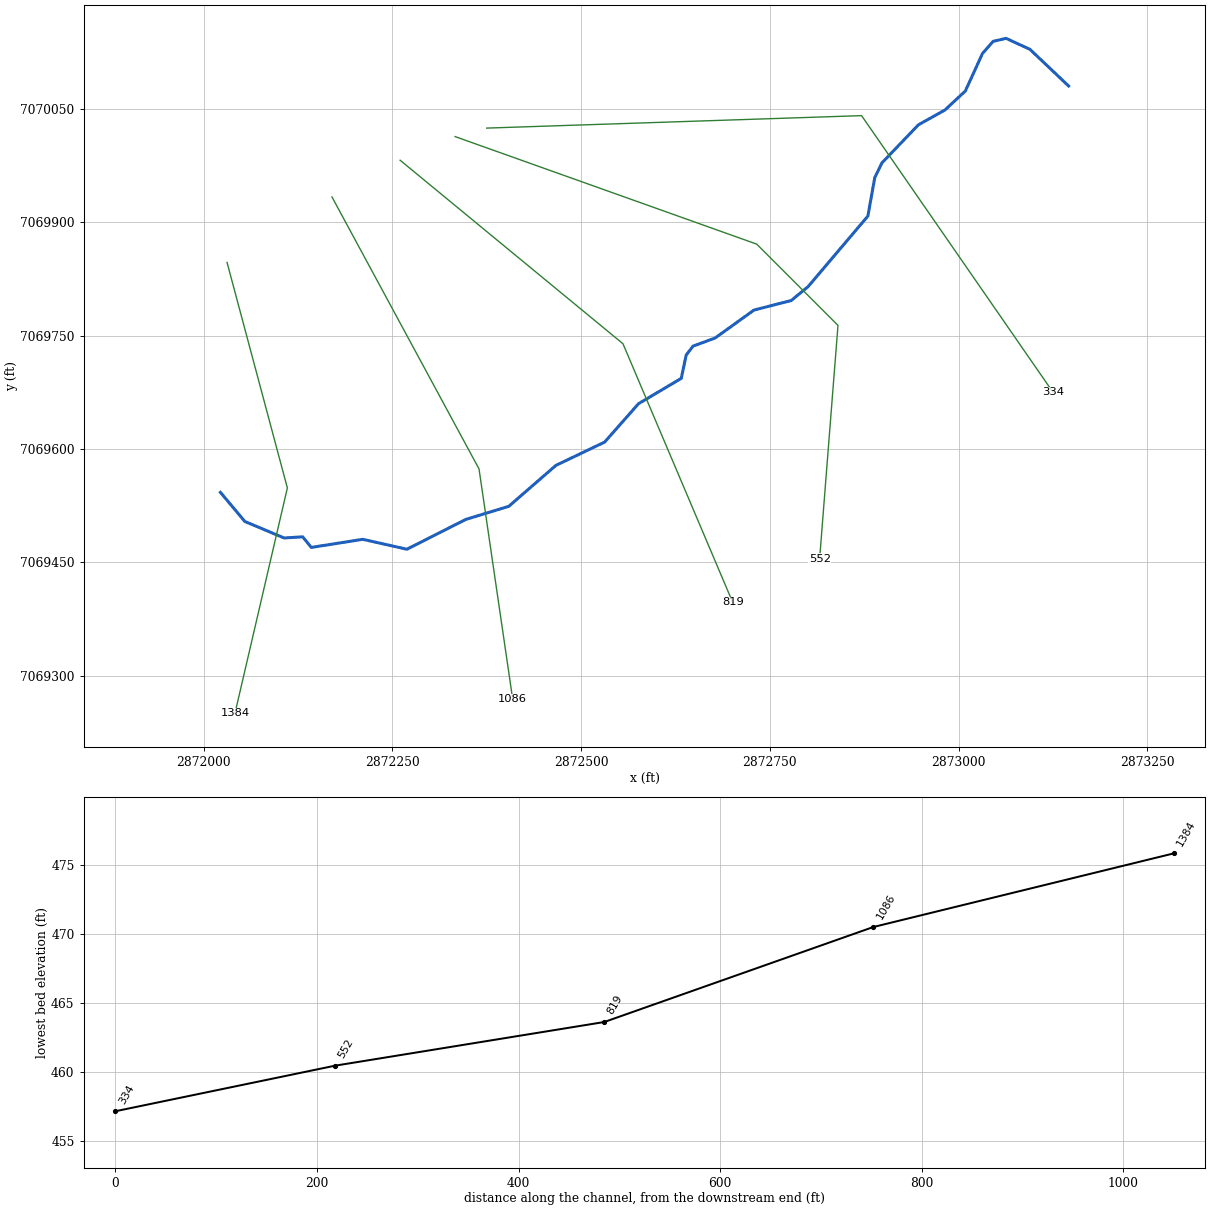
--- UNT 070 in Running Cr Watershed.prj (project) ---

Proj Title=UNT 070 in Running Cr Watershed Base Level Engineering
Current Plan=p01
Default Exp/Contr=0.3,0.1
English Units
Geom File=g01
Flow File=f01
Plan File=p01
BEGIN DESCRIPTION:
UNT 070 in Running Cr Watershed
END DESCRIPTION:

--- UNT 070 in Running Cr Watershed.p01 (plan) ---

Plan Title=Multiple Run
Short Identifier=Multiple
Geom File=g01
Flow File=f01
Subcritical Flow
K Sum by GR= 0
Std Step Tol= 0.01
Critical Tol= 0.01
Num of Std Step Trials= 20
Max Error Tol= 0.3
Flow Tol Ratio= 0.001
Split Flow NTrial= 30
Split Flow Tol= 0.02
Split Flow Ratio= 0.02
Log Output Level= 0
Friction Slope Method= 1
Unsteady Friction Slope Method= 2
Unsteady Bridges Friction Slope Method= 1
Parabolic Critical Depth
Global Vel Dist=  1 , 1 , 1
Global Log Level= 0
CheckData=True
Encroach Param= -1, 0, 0, 0
BEGIN DESCRIPTION:
Multiple Run
END DESCRIPTION:

--- UNT 070 in Running Cr Watershed.f01 (steady flow) ---

Flow Title=Multiple
Number of Profiles=7
Profile Names=10-year,25-year,50-year,1pct_min,100-year,1pct_plu,500-year
River Rch & RM= UNT 070 in Runni,Reach-1,1384
     224     279     321     184     368     733     478
Boundary for River Rch & Prof#=UNT 070 in Runni,Reach-1,1
Up Type=0
Dn Type=3
Dn Slope=0.005
Boundary for River Rch & Prof#=UNT 070 in Runni,Reach-1,2
Up Type=0
Dn Type=3
Dn Slope=0.005
Boundary for River Rch & Prof#=UNT 070 in Runni,Reach-1,3
Up Type=0
Dn Type=3
Dn Slope=0.005
Boundary for River Rch & Prof#=UNT 070 in Runni,Reach-1,4
Up Type=0
Dn Type=3
Dn Slope=0.005
Boundary for River Rch & Prof#=UNT 070 in Runni,Reach-1,5
Up Type=0
Dn Type=3
Dn Slope=0.005
Boundary for River Rch & Prof#=UNT 070 in Runni,Reach-1,6
Up Type=0
Dn Type=3
Dn Slope=0.005
Boundary for River Rch & Prof#=UNT 070 in Runni,Reach-1,7
Up Type=0
Dn Type=3
Dn Slope=0.005

--- UNT 070 in Running Cr Watershed.g01 (geometry) ---

Geom Title=Existing Conditions

River Reach=UNT 070 in Runni,Reach-1
Reach XY= 30
      2872022.35      7069542.61      2872054.64      7069504.07
      2872106.72      7069482.19      2872131.20      7069483.75
      2872142.66      7069469.69      2872210.78      7069480.43
      2872269.31      7069467.30      2872347.19      7069506.75
      2872404.18      7069524.11      2872466.60      7069578.34
      2872531.14      7069609.19      2872575.98      7069660.01
      2872632.60      7069693.57      2872639.11      7069724.39
      2872648.16      7069736.28      2872677.35      7069746.95
      2872728.91      7069784.01      2872778.17      7069796.64
      2872800.54      7069815.04      2872879.72      7069908.45
      2872888.85      7069959.42      2872898.41      7069978.99
      2872946.68      7070029.38      2872981.72      7070048.90
      2873008.79      7070074.09      2873031.47      7070123.75
      2873045.52      7070139.81      2873062.66      7070143.87
      2873094.34      7070129.30      2873145.59      7070080.71

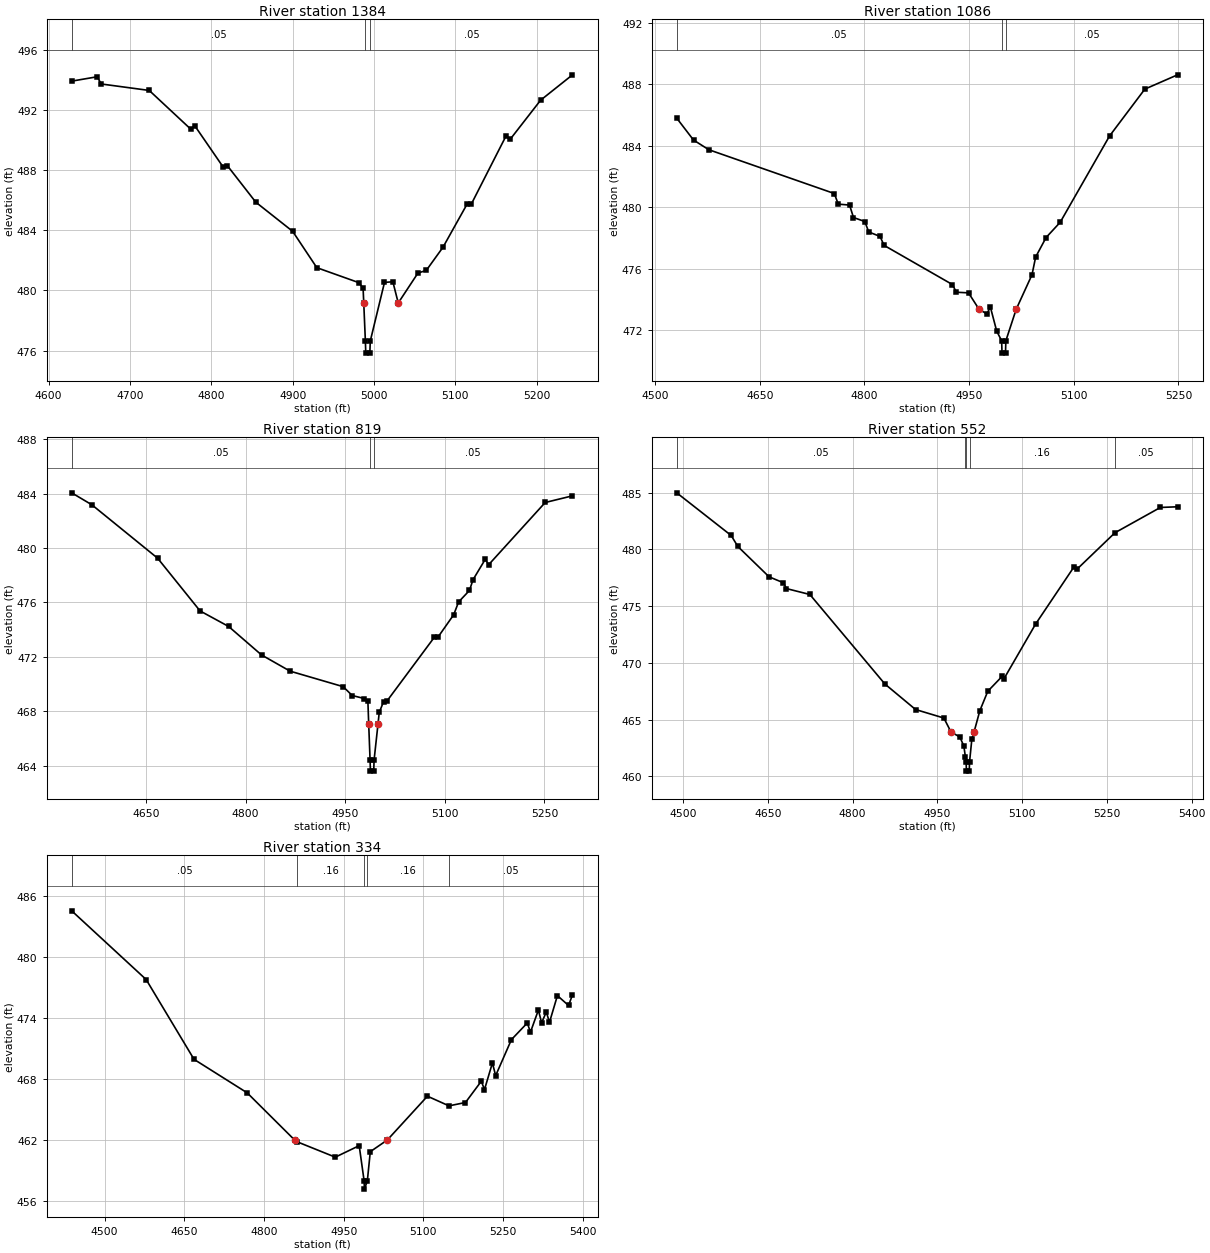
Type RM Length L Ch R = 1,1384,298,298,298
BEGIN DESCRIPTION:
UNT 070 in Running Cr Watershed 3.0
END DESCRIPTION:
XS GIS Cut Line= 3
      2872031.10      7069847.07      2872110.97      7069548.44
      2872041.55      7069249.93
#Sta/Elev= 30
  4628.3  493.94  4659.5  494.23  4664.7  493.75  4723.6  493.32  4774.5  490.75
  4779.7  490.96  4814.6  488.21  4819.8  488.30  4854.6  485.88  4899.9  483.94
  4929.6  481.52  4981.4  480.52  4986.5  480.15  4987.3  479.17  4989.3  476.63
  4989.8  475.83  4994.8  475.83  4995.3  476.63  5012.8  480.54  5023.1  480.58
  5029.7  479.17  5053.9  481.16  5064.2  481.34  5084.7  482.88  5114.3  485.75
  5119.5  485.75  5162.1  490.28  5167.2  490.06  5204.7  492.67  5243.9  494.36
#Mann=3,-1,0
  4628.3    0.05       0  4989.3    0.03       0  4995.3    0.05       0
Bank Sta=4987.3,5029.7
Exp/Cntr=0.3,0.1

Type RM Length L Ch R = 1,1086,267,267,267
BEGIN DESCRIPTION:
UNT 070 in Running Cr Watershed 2.0
END DESCRIPTION:
XS GIS Cut Line= 3
      2872170.02      7069933.82      2872364.78      7069573.66
      2872409.38      7069268.55
#Sta/Elev= 30
  4531.0  485.78  4555.0  484.36  4576.9  483.73  4756.8  480.88  4762.5  480.19
  4778.7  480.13  4784.3  479.32  4800.5  479.06  4806.2  478.38  4822.4  478.09
  4828.1  477.51  4926.1  474.96  4931.8  474.46  4949.2  474.42  4964.3  473.35
  4975.5  473.05  4980.5  473.50  4989.6  471.93  4996.7  471.30  4997.2  470.50
  5002.2  470.50  5002.7  471.30  5017.5  473.35  5040.2  475.60  5045.4  476.75
  5060.4  478.02  5080.6  479.01  5151.3  484.62  5201.9  487.67  5248.8  488.60
#Mann=3,-1,0
  4531.0    0.05       0  4996.7    0.03       0  5002.7    0.05       0
Bank Sta=4964.3,5017.5
Exp/Cntr=0.3,0.1

Type RM Length L Ch R = 1,819,267,267,267
BEGIN DESCRIPTION:
Mapping XS b83dac44
END DESCRIPTION:
XS GIS Cut Line= 3
      2872260.31      7069982.44      2872555.41      7069739.42
      2872700.62      7069397.14
#Sta/Elev= 30
  4538.2  484.05  4568.6  483.17  4667.6  479.25  4731.5  475.38  4774.5  474.24
  4824.0  472.15  4867.0  470.96  4947.0  469.82  4960.6  469.17  4978.8  468.95
  4984.2  468.74  4985.4  467.11  4987.5  464.42  4988.0  463.62  4993.0  463.62
  4993.5  464.42  4999.5  467.11  5001.3  467.93  5007.9  468.73  5013.3  468.79
  5084.3  473.45  5089.8  473.46  5113.4  475.10  5120.8  476.04  5137.1  476.88
  5142.5  477.67  5160.8  479.16  5166.2  478.78  5251.2  483.34  5292.3  483.83
#Mann=3,-1,0
  4538.2    0.05       0  4987.5    0.03       0  4993.5    0.05       0
Bank Sta=4985.4,4999.5
Exp/Cntr=0.3,0.1

Type RM Length L Ch R = 1,552,218,218,218
BEGIN DESCRIPTION:
Mapping XS 45eca1a2
END DESCRIPTION:
XS GIS Cut Line= 4
      2872333.15      7070013.74      2872732.50      7069871.36
      2872840.14      7069763.72      2872815.83      7069454.67
#Sta/Elev= 30
  4488.9  484.99  4585.2  481.23  4597.0  480.26  4652.2  477.59  4677.7  477.06
  4683.0  476.55  4724.4  476.03  4857.2  468.14  4911.5  465.89  4961.6  465.14
  4974.2  463.91  4989.8  463.47  4996.9  462.68  4999.7  461.71  5001.0  461.26
  5001.5  460.46  5006.5  460.46  5007.0  461.26  5011.1  463.28  5015.0  463.91
  5025.2  465.78  5039.3  467.50  5065.0  468.83  5067.8  468.59  5124.0  473.43
  5191.8  478.46  5196.8  478.24  5264.3  481.47  5344.7  483.70  5375.1  483.76
#Mann=5,-1,0
  4488.9    0.05       0  4999.7    0.16       0  5001.0    0.07       0
  5007.0    0.16       0  5264.3    0.05       0
Bank Sta=4974.2,5015
Exp/Cntr=0.3,0.1

Type RM Length L Ch R = 1,334,0,0,0
BEGIN DESCRIPTION:
UNT 070 in Running Cr Watershed 1.0
END DESCRIPTION:
XS GIS Cut Line= 3
      2872374.96      7070025.00      2872871.39      7070041.50
      2873125.00      7069675.00
#Sta/Elev= 30
  4438.2  484.50  4578.3  477.75  4668.4  469.91  4768.4  466.62  4857.6  461.99
  4862.4  461.81  4934.2  460.30  4979.2  461.43  4988.5  457.96  4989.0  457.16
  4994.5  457.96  5000.1  460.84  5032.2  461.99  5107.6  466.29  5148.2  465.34
  5179.2  465.67  5209.0  467.76  5215.0  466.94  5229.9  469.56  5236.0  468.31
  5265.7  471.85  5295.5  473.48  5301.5  472.58  5316.4  474.75  5322.5  473.51
  5331.3  474.56  5337.3  473.55  5352.2  476.17  5373.2  475.20  5380.6  476.26
#Mann=5,-1,0
  4438.2    0.05       0  4862.4    0.16       0  4988.5    0.07       0
  4994.5    0.16       0  5148.2    0.05       0
Bank Sta=4857.6,5032.2
Exp/Cntr=0.3,0.1

Chan Stop Cuts=-1