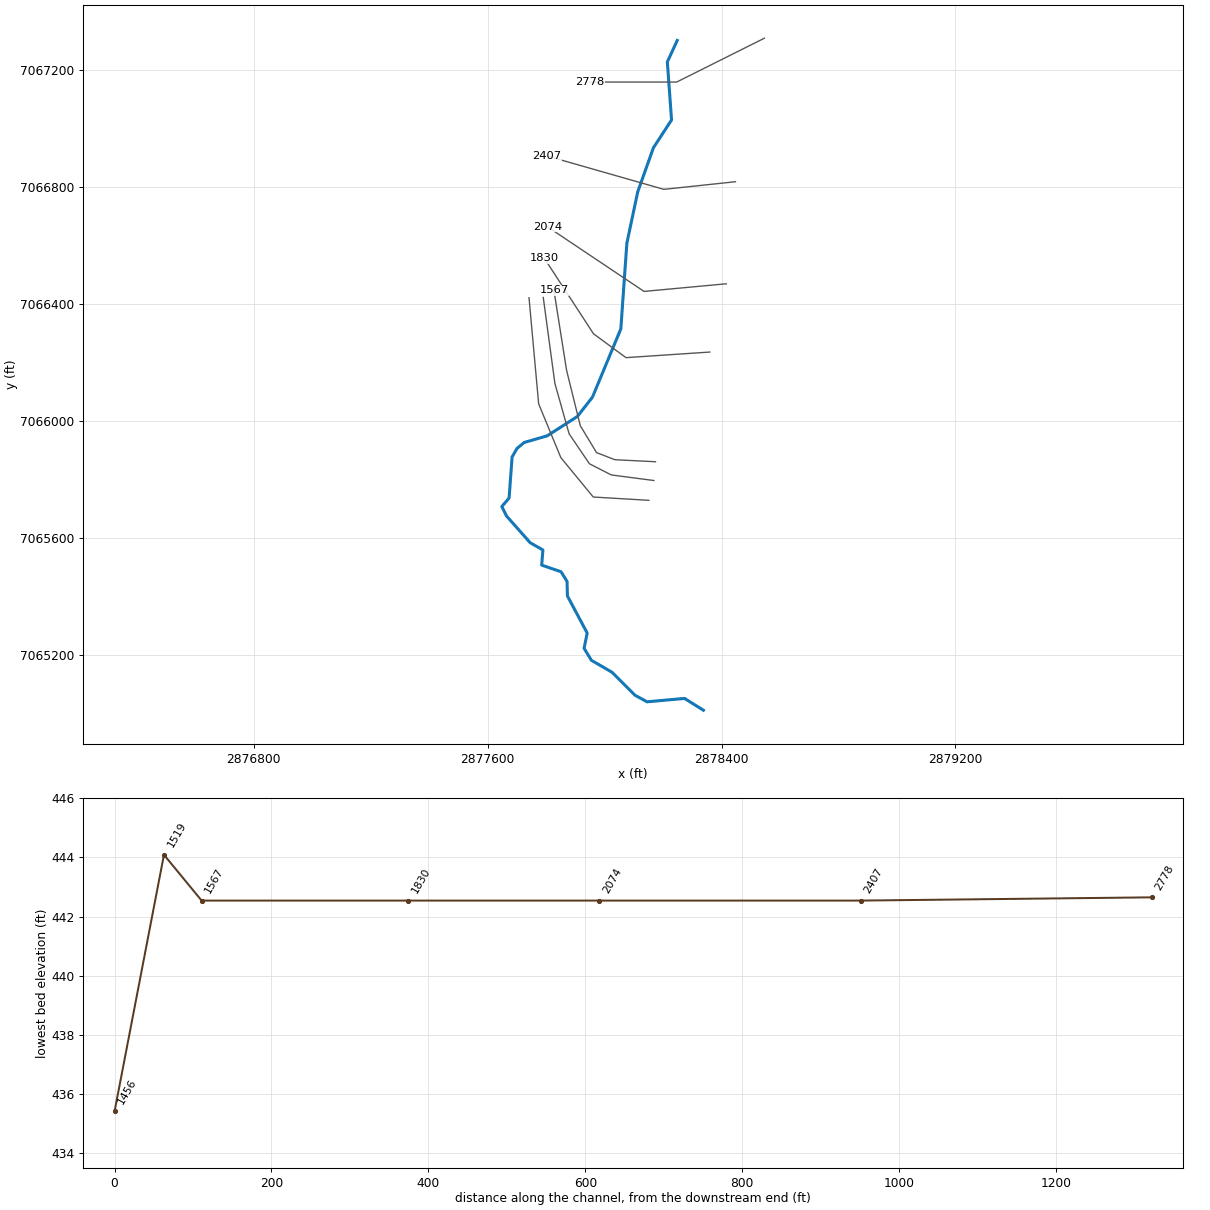
--- UNT 071 in Running Cr Watershed.prj (project) ---

Proj Title=UNT 071 in Running Cr Watershed Base Level Engineering
Current Plan=p01
Default Exp/Contr=0.3,0.1
English Units
Geom File=g01
Flow File=f01
Plan File=p01
BEGIN DESCRIPTION:
UNT 071 in Running Cr Watershed
END DESCRIPTION:

--- UNT 071 in Running Cr Watershed.p01 (plan) ---

Plan Title=Multiple Run
Short Identifier=Multiple
Geom File=g01
Flow File=f01
Subcritical Flow
K Sum by GR= 0
Std Step Tol= 0.01
Critical Tol= 0.01
Num of Std Step Trials= 20
Max Error Tol= 0.3
Flow Tol Ratio= 0.001
Split Flow NTrial= 30
Split Flow Tol= 0.02
Split Flow Ratio= 0.02
Log Output Level= 0
Friction Slope Method= 1
Unsteady Friction Slope Method= 2
Unsteady Bridges Friction Slope Method= 1
Parabolic Critical Depth
Global Vel Dist=  1 , 1 , 1
Global Log Level= 0
CheckData=True
Encroach Param= -1, 0, 0, 0
BEGIN DESCRIPTION:
Multiple Run
END DESCRIPTION:

--- UNT 071 in Running Cr Watershed.f01 (steady flow) ---

Flow Title=Multiple
Number of Profiles=7
Profile Names=10-year,25-year,50-year,1pct_min,100-year,1pct_plu,500-year
River Rch & RM= UNT 071 in Runni,Reach-1,2778
     281     351     404     231     461     919     597
Boundary for River Rch & Prof#=UNT 071 in Runni,Reach-1,1
Up Type=0
Dn Type=3
Dn Slope=0.005
Boundary for River Rch & Prof#=UNT 071 in Runni,Reach-1,2
Up Type=0
Dn Type=3
Dn Slope=0.005
Boundary for River Rch & Prof#=UNT 071 in Runni,Reach-1,3
Up Type=0
Dn Type=3
Dn Slope=0.005
Boundary for River Rch & Prof#=UNT 071 in Runni,Reach-1,4
Up Type=0
Dn Type=3
Dn Slope=0.005
Boundary for River Rch & Prof#=UNT 071 in Runni,Reach-1,5
Up Type=0
Dn Type=3
Dn Slope=0.005
Boundary for River Rch & Prof#=UNT 071 in Runni,Reach-1,6
Up Type=0
Dn Type=3
Dn Slope=0.005
Boundary for River Rch & Prof#=UNT 071 in Runni,Reach-1,7
Up Type=0
Dn Type=3
Dn Slope=0.005

--- UNT 071 in Running Cr Watershed.g01 (geometry) ---

Geom Title=Existing Conditions

River Reach=UNT 071 in Runni,Reach-1
Reach XY= 30
      2878248.55      7067299.48      2878214.76      7067226.10
      2878229.22      7067027.84      2878167.26      7066932.84
      2878113.57      7066782.08      2878076.39      7066606.53
      2878055.74      7066313.27      2877958.68      7066079.90
      2877907.05      7066013.82      2877803.79      7065947.73
      2877725.31      7065925.01      2877700.53      7065904.36
      2877684.00      7065875.45      2877673.68      7065735.01
      2877648.90      7065706.10      2877665.42      7065673.06
      2877745.96      7065582.19      2877789.33      7065557.40
      2877785.20      7065505.77      2877851.29      7065483.06
      2877871.94      7065450.01      2877873.08      7065400.43
      2877940.76      7065273.53      2877930.15      7065221.26
      2877955.00      7065180.42      2878025.54      7065139.46
      2878104.34      7065060.69      2878145.45      7065038.37
      2878273.56      7065049.92      2878338.14      7065009.59

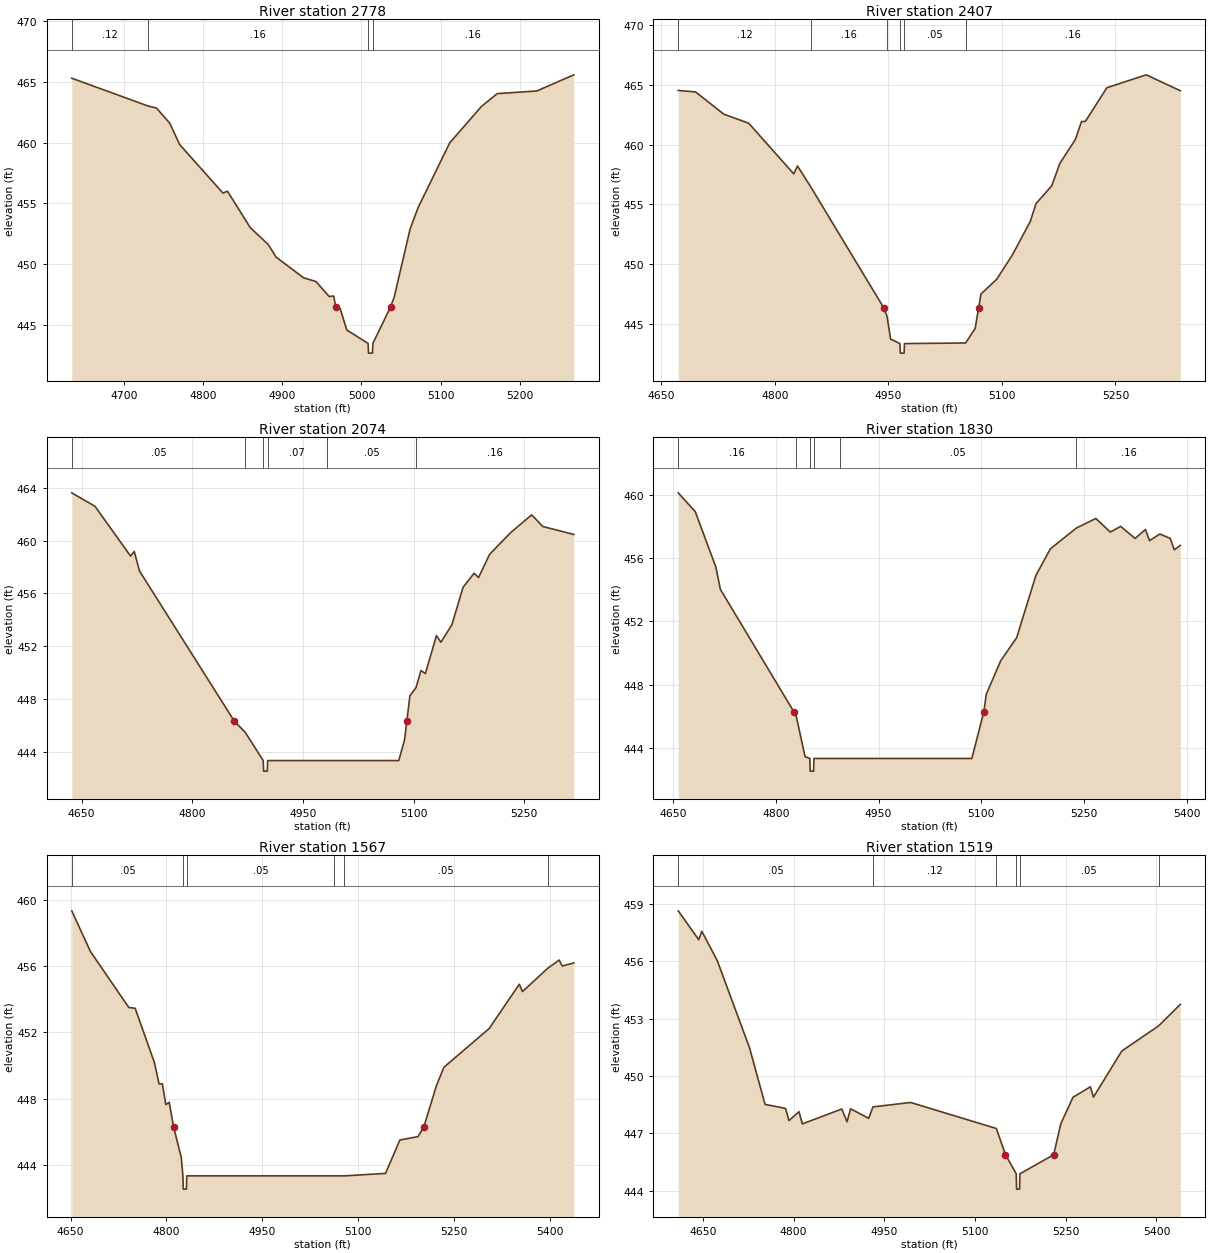
Type RM Length L Ch R = 1,2778,371,371,371
BEGIN DESCRIPTION:
UNT 071 in Running Cr Watershed 2.0
END DESCRIPTION:
XS GIS Cut Line= 3
      2878546.70      7067307.38      2878246.70      7067157.38
      2877948.31      7067157.38
#Sta/Elev= 30
  4634.3  465.31  4730.6  463.02  4741.3  462.85  4758.1  461.59  4770.4  459.85
  4825.2  455.84  4830.8  456.00  4859.8  452.98  4882.2  451.61  4892.3  450.56
  4926.9  448.86  4942.6  448.55  4959.3  447.31  4964.9  447.36  4967.6  446.45
  4973.1  446.33  4981.4  444.56  5008.4  443.45  5008.9  442.65  5013.9  442.65
  5014.4  443.45  5036.7  446.45  5041.4  447.29  5061.4  452.88  5071.4  454.63
  5111.4  459.98  5151.4  462.98  5171.4  464.04  5221.4  464.26  5268.1  465.59
#Mann=4,-1,0
  4634.3    0.12       0  4730.6    0.16       0  5008.4    0.07       0
  5014.4    0.16       0
Bank Sta=4967.6,5036.7
Exp/Cntr=0.3,0.1

Type RM Length L Ch R = 1,2407,333,333,333
BEGIN DESCRIPTION:
Mapping XS 19a54bef
END DESCRIPTION:
XS GIS Cut Line= 3
      2878447.63      7066816.58      2878202.80      7066790.54
      2877801.76      7066905.12
#Sta/Elev= 30
  4672.4  464.54  4695.2  464.42  4732.5  462.56  4765.6  461.79  4825.0  457.55
  4830.0  458.21  4847.7  456.44  4943.9  446.34  4948.3  445.62  4952.9  443.72
  4965.3  443.34  4965.8  442.54  4970.8  442.54  4971.3  443.34  5052.1  443.39
  5064.7  444.61  5069.3  446.34  5072.3  447.49  5093.1  448.72  5113.9  450.77
  5137.5  453.57  5145.1  455.07  5165.9  456.56  5176.5  458.42  5197.1  460.44
  5205.1  461.93  5210.3  461.95  5238.7  464.77  5290.7  465.85  5335.7  464.52
#Mann=6,-1,0
  4672.4    0.12       0  4847.7    0.16       0  4948.3    0.05       0
  4965.3   0.033       0  4971.3    0.05       0  5052.1    0.16       0
Bank Sta=4943.9,5069.3
Exp/Cntr=0.3,0.1

Type RM Length L Ch R = 1,2074,244,244,244
BEGIN DESCRIPTION:
Mapping XS fe86887b
END DESCRIPTION:
XS GIS Cut Line= 3
      2878416.38      7066467.63      2878135.09      7066441.58
      2877804.36      7066663.00
#Sta/Elev= 30
  4636.7  463.62  4668.2  462.60  4716.4  458.83  4721.4  459.18  4728.5  457.70
  4857.2  446.31  4871.7  445.49  4896.2  443.34  4896.7  442.54  4901.7  442.54
  4902.2  443.34  4982.3  443.34  5079.9  443.34  5087.8  444.92  5090.8  446.31
  5095.0  448.25  5103.4  448.88  5110.0  450.16  5116.0  449.93  5131.0  452.81
  5137.0  452.30  5152.0  453.64  5167.0  456.46  5182.0  457.53  5188.0  457.20
  5203.0  458.96  5232.2  460.64  5260.1  461.95  5275.1  461.07  5317.2  460.47
#Mann=6,-1,0
  4636.7    0.05       0  4871.7    0.07       0  4896.2   0.033       0
  4902.2    0.07       0  4982.3    0.05       0  5103.4    0.16       0
Bank Sta=4857.2,5090.8
Exp/Cntr=0.3,0.1

Type RM Length L Ch R = 1,1830,263,263,263
BEGIN DESCRIPTION:
Mapping XS 70ee7aa8
END DESCRIPTION:
XS GIS Cut Line= 4
      2878359.88      7066234.21      2878073.43      7066215.11
      2877962.31      7066296.71      2877793.92      7066555.38
#Sta/Elev= 30
  4657.3  460.12  4682.2  458.93  4712.3  455.43  4718.9  454.02  4826.1  446.30
  4830.0  445.96  4842.6  443.45  4849.6  443.34  4850.1  442.54  4855.1  442.54
  4855.6  443.34  4893.5  443.34  5086.3  443.34  5103.9  446.30  5107.4  447.40
  5128.5  449.51  5151.8  450.97  5179.9  454.90  5201.0  456.58  5239.2  457.90
  5267.5  458.50  5288.6  457.64  5303.7  458.00  5324.8  457.24  5339.9  457.80
  5345.9  457.10  5361.0  457.52  5376.2  457.24  5382.1  456.52  5390.9  456.80
#Mann=6,-1,0
  4657.3    0.16       0  4830.0    0.07       0  4849.6   0.033       0
  4855.6    0.07       0  4893.5    0.05       0  5239.2    0.16       0
Bank Sta=4826.1,5103.9
Exp/Cntr=0.3,0.1

Type RM Length L Ch R = 1,1567,48,48,48
BEGIN DESCRIPTION:
Mapping XS e71b5053
END DESCRIPTION:
XS GIS Cut Line= 6
      2878174.15      7065859.21      2878035.23      7065866.15
      2877972.73      7065890.46      2877917.18      7065982.47
      2877870.30      7066171.71      2877826.90      7066446.00
#Sta/Elev= 30
  4651.7  459.33  4680.9  456.88  4741.0  453.50  4751.0  453.45  4781.0  450.19
  4788.4  448.89  4793.6  448.89  4798.9  447.64  4804.3  447.78  4811.2  446.29
  4823.2  444.44  4825.8  443.34  4826.3  442.54  4831.3  442.54  4831.8  443.34
  5062.4  443.34  5078.7  443.34  5143.1  443.49  5165.5  445.50  5194.0  445.71
  5203.0  446.29  5222.8  448.78  5234.5  449.89  5305.4  452.23  5352.6  454.90
  5357.6  454.46  5397.0  455.86  5414.9  456.36  5420.0  456.00  5438.0  456.19
#Mann=6,-1,0
  4651.7    0.05       0  4825.8   0.033       0  4831.8    0.05       0
  5062.4    0.12       0  5078.7    0.05       0  5397.0    0.16       0
Bank Sta=4811.2,5203
Exp/Cntr=0.3,0.1

Type RM Length L Ch R = 1,1519,63,63,63
BEGIN DESCRIPTION:
Mapping XS b60208f5
END DESCRIPTION:
XS GIS Cut Line= 6
      2878168.91      7065794.97      2878023.08      7065814.07
      2877948.43      7065852.26      2877878.98      7065954.69
      2877830.37      7066126.57      2877790.55      7066420.89
#Sta/Elev= 30
  4609.1  458.64  4643.0  457.13  4648.1  457.57  4673.6  456.04  4726.9  451.49
  4752.7  448.52  4786.6  448.31  4792.2  447.67  4808.8  448.14  4814.4  447.50
  4879.6  448.28  4888.2  447.61  4894.2  448.29  4924.1  447.79  4931.1  448.39
  4993.4  448.62  5135.2  447.26  5150.3  445.89  5168.1  444.89  5168.6  444.09
  5173.6  444.09  5174.1  444.89  5230.0  445.89  5241.7  447.50  5261.9  448.89
  5290.7  449.44  5295.8  448.90  5342.6  451.31  5403.7  452.63  5439.4  453.75
#Mann=6,-1,0
  4609.1    0.05       0  4931.1    0.12       0  5135.2    0.05       0
  5168.1    0.07       0  5174.1    0.05       0  5403.7    0.16       0
Bank Sta=5150.3,5230
Exp/Cntr=0.3,0.1

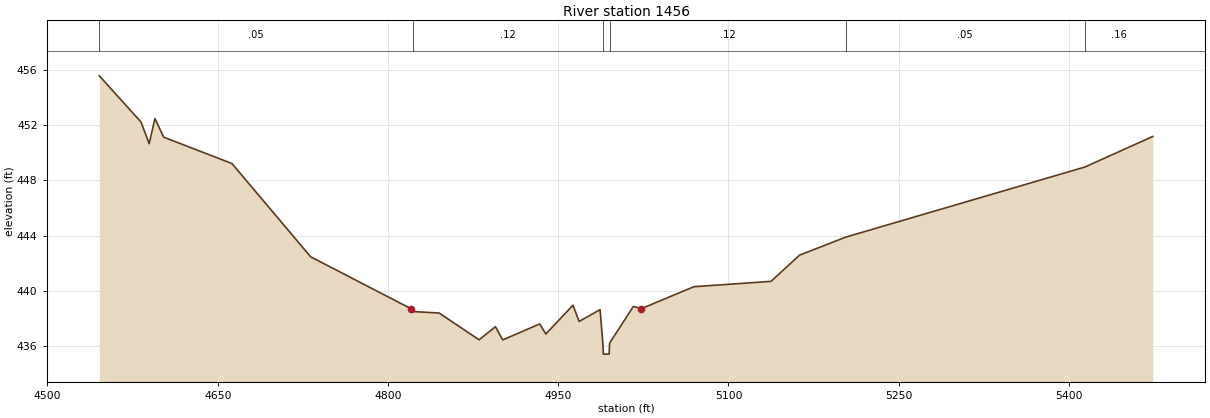
Type RM Length L Ch R = 1,1456,0,0,0
BEGIN DESCRIPTION:
UNT 071 in Running Cr Watershed 1.0
END DESCRIPTION:
XS GIS Cut Line= 5
      2878151.59      7065727.26      2877961.45      7065738.55
      2877850.77      7065873.10      2877774.81      7066057.12
      2877741.83      7066419.94
#Sta/Elev= 30
  4545.7  455.59  4582.4  452.24  4589.6  450.67  4594.7  452.49  4602.4  451.14
  4662.5  449.23  4731.9  442.46  4820.2  438.70  4822.3  438.49  4845.1  438.38
  4880.3  436.44  4894.7  437.39  4901.1  436.43  4933.7  437.59  4939.1  436.86
  4963.0  438.95  4968.4  437.77  4986.9  438.63  4989.3  436.20  4989.8  435.40
  4994.8  435.40  4995.3  436.20  5016.2  438.86  5023.3  438.70  5069.5  440.29
  5137.5  440.68  5162.6  442.58  5203.4  443.89  5413.9  448.97  5473.8  451.19
#Mann=6,-1,0
  4545.7    0.05       0  4822.3    0.12       0  4989.3    0.07       0
  4995.3    0.12       0  5203.4    0.05       0  5413.9    0.16       0
Bank Sta=4820.2,5023.3
Exp/Cntr=0.3,0.1

Chan Stop Cuts=-1