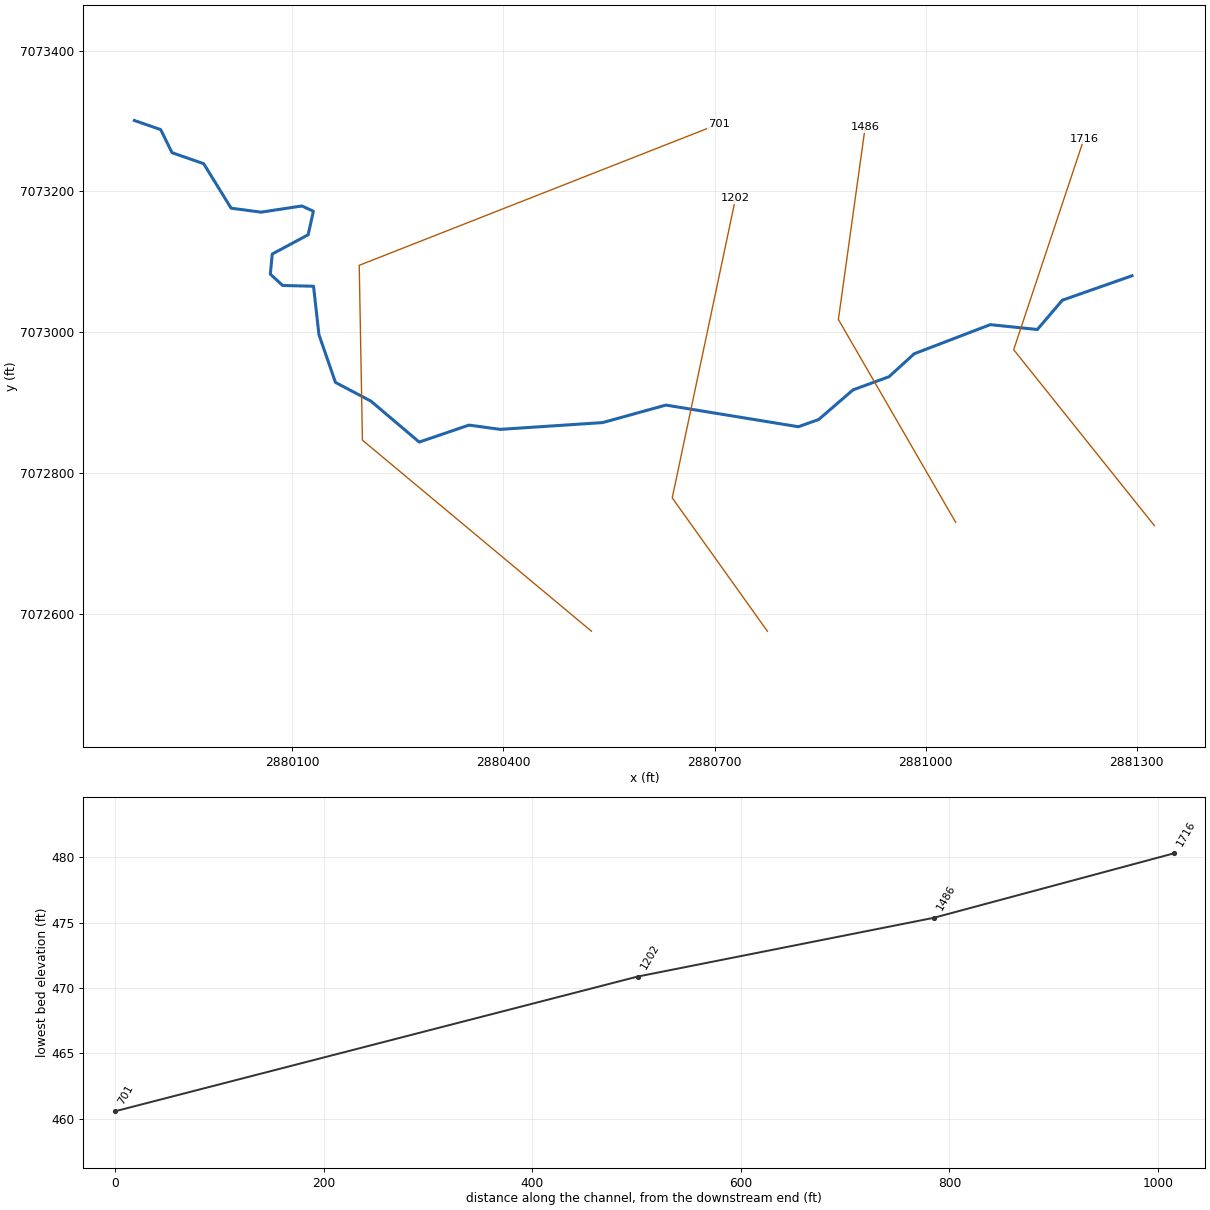
--- UNT 072 in Running Cr Watershed.prj (project) ---

Proj Title=UNT 072 in Running Cr Watershed Base Level Engineering
Current Plan=p01
Default Exp/Contr=0.3,0.1
English Units
Geom File=g01
Flow File=f01
Plan File=p01
BEGIN DESCRIPTION:
UNT 072 in Running Cr Watershed
END DESCRIPTION:

--- UNT 072 in Running Cr Watershed.p01 (plan) ---

Plan Title=Multiple Run
Short Identifier=Multiple
Geom File=g01
Flow File=f01
Subcritical Flow
K Sum by GR= 0
Std Step Tol= 0.01
Critical Tol= 0.01
Num of Std Step Trials= 20
Max Error Tol= 0.3
Flow Tol Ratio= 0.001
Split Flow NTrial= 30
Split Flow Tol= 0.02
Split Flow Ratio= 0.02
Log Output Level= 0
Friction Slope Method= 1
Unsteady Friction Slope Method= 2
Unsteady Bridges Friction Slope Method= 1
Parabolic Critical Depth
Global Vel Dist=  1 , 1 , 1
Global Log Level= 0
CheckData=True
Encroach Param= -1, 0, 0, 0
BEGIN DESCRIPTION:
Multiple Run
END DESCRIPTION:

--- UNT 072 in Running Cr Watershed.f01 (steady flow) ---

Flow Title=Multiple
Number of Profiles=7
Profile Names=10-year,25-year,50-year,1pct_min,100-year,1pct_plu,500-year
River Rch & RM= UNT 072 in Runni,Reach-1,1716
     227     283     325     186     372     742     485
Boundary for River Rch & Prof#=UNT 072 in Runni,Reach-1,1
Up Type=0
Dn Type=3
Dn Slope=0.005
Boundary for River Rch & Prof#=UNT 072 in Runni,Reach-1,2
Up Type=0
Dn Type=3
Dn Slope=0.005
Boundary for River Rch & Prof#=UNT 072 in Runni,Reach-1,3
Up Type=0
Dn Type=3
Dn Slope=0.005
Boundary for River Rch & Prof#=UNT 072 in Runni,Reach-1,4
Up Type=0
Dn Type=3
Dn Slope=0.005
Boundary for River Rch & Prof#=UNT 072 in Runni,Reach-1,5
Up Type=0
Dn Type=3
Dn Slope=0.005
Boundary for River Rch & Prof#=UNT 072 in Runni,Reach-1,6
Up Type=0
Dn Type=3
Dn Slope=0.005
Boundary for River Rch & Prof#=UNT 072 in Runni,Reach-1,7
Up Type=0
Dn Type=3
Dn Slope=0.005

--- UNT 072 in Running Cr Watershed.g01 (geometry) ---

Geom Title=Existing Conditions

River Reach=UNT 072 in Runni,Reach-1
Reach XY= 30
      2881293.18      7073080.08      2881194.22      7073045.36
      2881158.63      7073003.69      2881091.79      7073010.63
      2880983.71      7072969.24      2880947.78      7072936.56
      2880896.75      7072917.94      2880847.96      7072875.85
      2880819.03      7072865.53      2880630.79      7072896.31
      2880540.87      7072871.43      2880395.49      7072861.80
      2880351.00      7072867.87      2880280.31      7072843.75
      2880211.69      7072901.89      2880161.29      7072928.50
      2880137.78      7072996.47      2880130.12      7073065.18
      2880086.26      7073066.26      2880068.73      7073082.36
      2880071.45      7073110.96      2880122.43      7073138.29
      2880129.90      7073171.79      2880113.53      7073179.24
      2880055.52      7073170.46      2880013.00      7073176.10
      2879973.99      7073239.34      2879929.06      7073254.95
      2879912.91      7073287.78      2879875.59      7073300.71

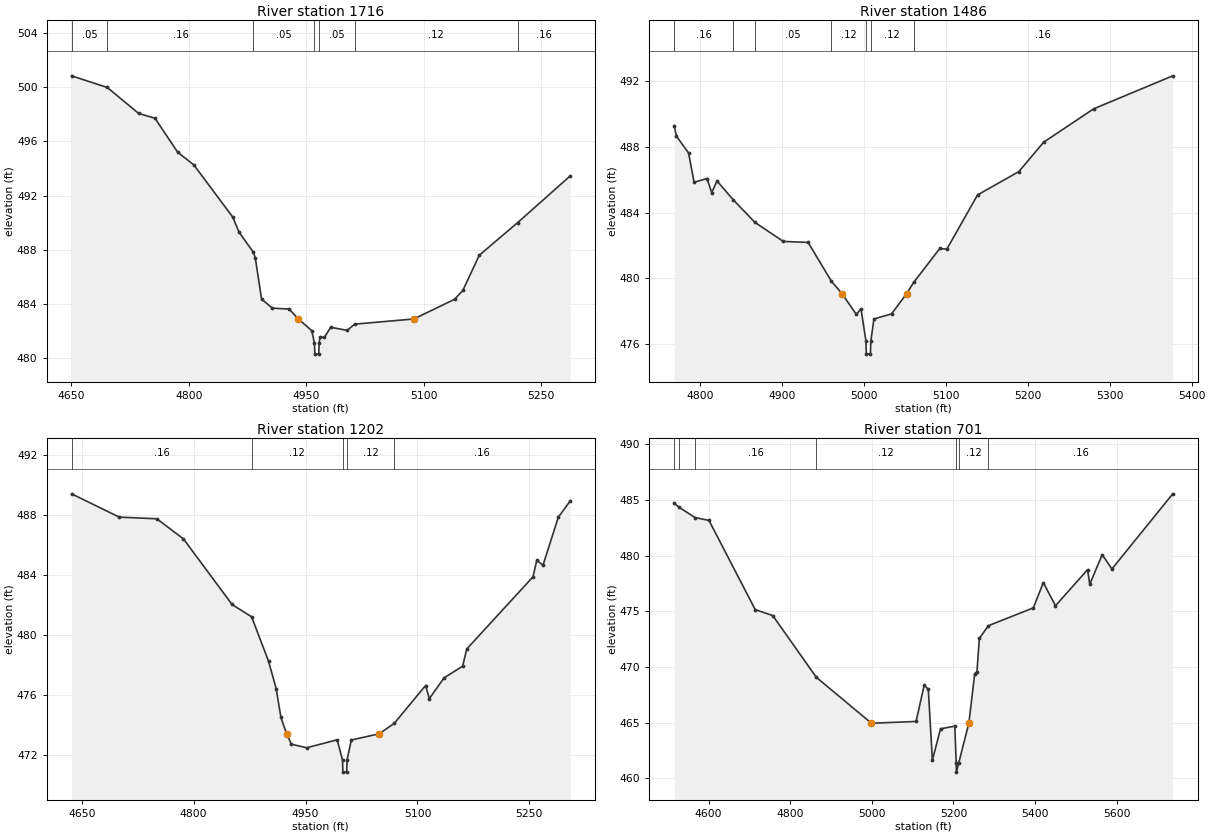
Type RM Length L Ch R = 1,1716,230,230,230
BEGIN DESCRIPTION:
UNT 072 in Running Cr Watershed 3.0
END DESCRIPTION:
XS GIS Cut Line= 3
      2881325.00      7072725.00      2881125.00      7072975.00
      2881225.00      7073275.01
#Sta/Elev= 30
  4650.4  500.82  4696.0  499.96  4736.0  498.05  4756.9  497.69  4785.7  495.20
  4806.5  494.25  4856.1  490.41  4864.1  489.31  4882.6  487.80  4884.9  487.40
  4892.9  484.37  4906.5  483.70  4928.1  483.63  4939.9  482.90  4957.0  482.04
  4960.4  481.11  4960.9  480.31  4965.9  480.31  4966.4  481.11  4967.4  481.55
  4973.2  481.55  4981.1  482.29  5002.2  482.06  5011.8  482.52  5087.2  482.90
  5139.2  484.35  5149.8  485.00  5170.8  487.60  5219.6  489.99  5286.8  493.44
#Mann=7,-1,0
  4650.4    0.05       0  4696.0    0.16       0  4882.6    0.05       0
  4960.4    0.04       0  4966.4    0.05       0  5011.8    0.12       0
  5219.6    0.16       0
Bank Sta=4939.9,5087.2
Exp/Cntr=0.3,0.1

Type RM Length L Ch R = 1,1486,284,284,284
BEGIN DESCRIPTION:
Mapping XS f148c887
END DESCRIPTION:
XS GIS Cut Line= 3
      2881042.59      7072729.72      2880875.93      7073017.91
      2880913.96      7073291.07
#Sta/Elev= 30
  4768.2  489.29  4770.9  488.65  4785.8  487.62  4792.5  485.84  4808.2  486.07
  4814.0  485.21  4820.5  485.92  4840.0  484.79  4866.8  483.40  4901.4  482.24
  4931.7  482.18  4960.0  479.83  4972.9  479.07  4990.6  477.80  4996.3  478.14
  5002.3  476.18  5002.8  475.38  5007.8  475.38  5008.3  476.18  5012.1  477.52
  5033.6  477.83  5052.1  479.07  5060.5  479.74  5092.5  481.81  5101.1  481.77
  5138.6  485.07  5189.0  486.49  5219.3  488.28  5280.3  490.31  5376.9  492.32
#Mann=7,-1,0
  4768.2    0.16       0  4840.0    0.08       0  4866.8    0.05       0
  4960.0    0.12       0  5002.3    0.07       0  5008.3    0.12       0
  5060.5    0.16       0
Bank Sta=4972.9,5052.1
Exp/Cntr=0.3,0.1

Type RM Length L Ch R = 1,1202,501,501,501
BEGIN DESCRIPTION:
UNT 072 in Running Cr Watershed 2.0
END DESCRIPTION:
XS GIS Cut Line= 3
      2880775.01      7072574.98      2880639.82      7072764.44
      2880729.89      7073190.58
#Sta/Elev= 30
  4636.4  489.39  4700.3  487.84  4750.7  487.73  4786.4  486.39  4851.5  482.03
  4877.7  481.21  4900.4  478.26  4910.6  476.44  4917.0  474.52  4924.6  473.43
  4931.0  472.74  4951.5  472.50  4992.4  473.03  4999.6  471.68  5000.1  470.88
  5005.1  470.88  5005.6  471.68  5011.4  473.02  5048.9  473.43  5069.0  474.13
  5110.9  476.64  5116.0  475.77  5135.5  477.14  5160.6  477.93  5166.1  479.07
  5254.9  483.87  5260.0  484.97  5268.3  484.64  5288.8  487.83  5304.7  488.91
#Mann=5,-1,0
  4636.4    0.16       0  4877.7    0.12       0  4999.6    0.07       0
  5005.6    0.12       0  5069.0    0.16       0
Bank Sta=4924.6,5048.9
Exp/Cntr=0.3,0.1

Type RM Length L Ch R = 1,701,0,0,0
BEGIN DESCRIPTION:
UNT 072 in Running Cr Watershed 1.0
END DESCRIPTION:
XS GIS Cut Line= 4
      2880525.04      7072574.97      2880199.59      7072846.45
      2880195.04      7073094.90      2880705.78      7073295.69
#Sta/Elev= 30
  4515.9  484.73  4527.4  484.37  4566.8  483.43  4601.2  483.17  4714.4  475.16
  4757.4  474.63  4863.9  469.09  4999.1  464.96  5108.3  465.12  5128.3  468.38
  5138.3  468.01  5148.3  461.65  5168.3  464.46  5203.2  464.70  5206.7  461.37
  5207.2  460.57  5212.7  461.37  5237.6  464.96  5252.0  469.41  5257.4  469.57
  5263.4  472.58  5285.6  473.72  5395.6  475.32  5420.0  477.59  5449.8  475.51
  5528.4  478.75  5533.8  477.44  5564.2  480.10  5588.0  478.81  5737.0  485.56
#Mann=7,-1,0
  4515.9    0.16       0  4527.4    0.12       0  4566.8    0.16       0
  4863.9    0.12       0  5206.7    0.07       0  5212.7    0.12       0
  5285.6    0.16       0
Bank Sta=4999.1,5237.6
Exp/Cntr=0.3,0.1

Chan Stop Cuts=-1