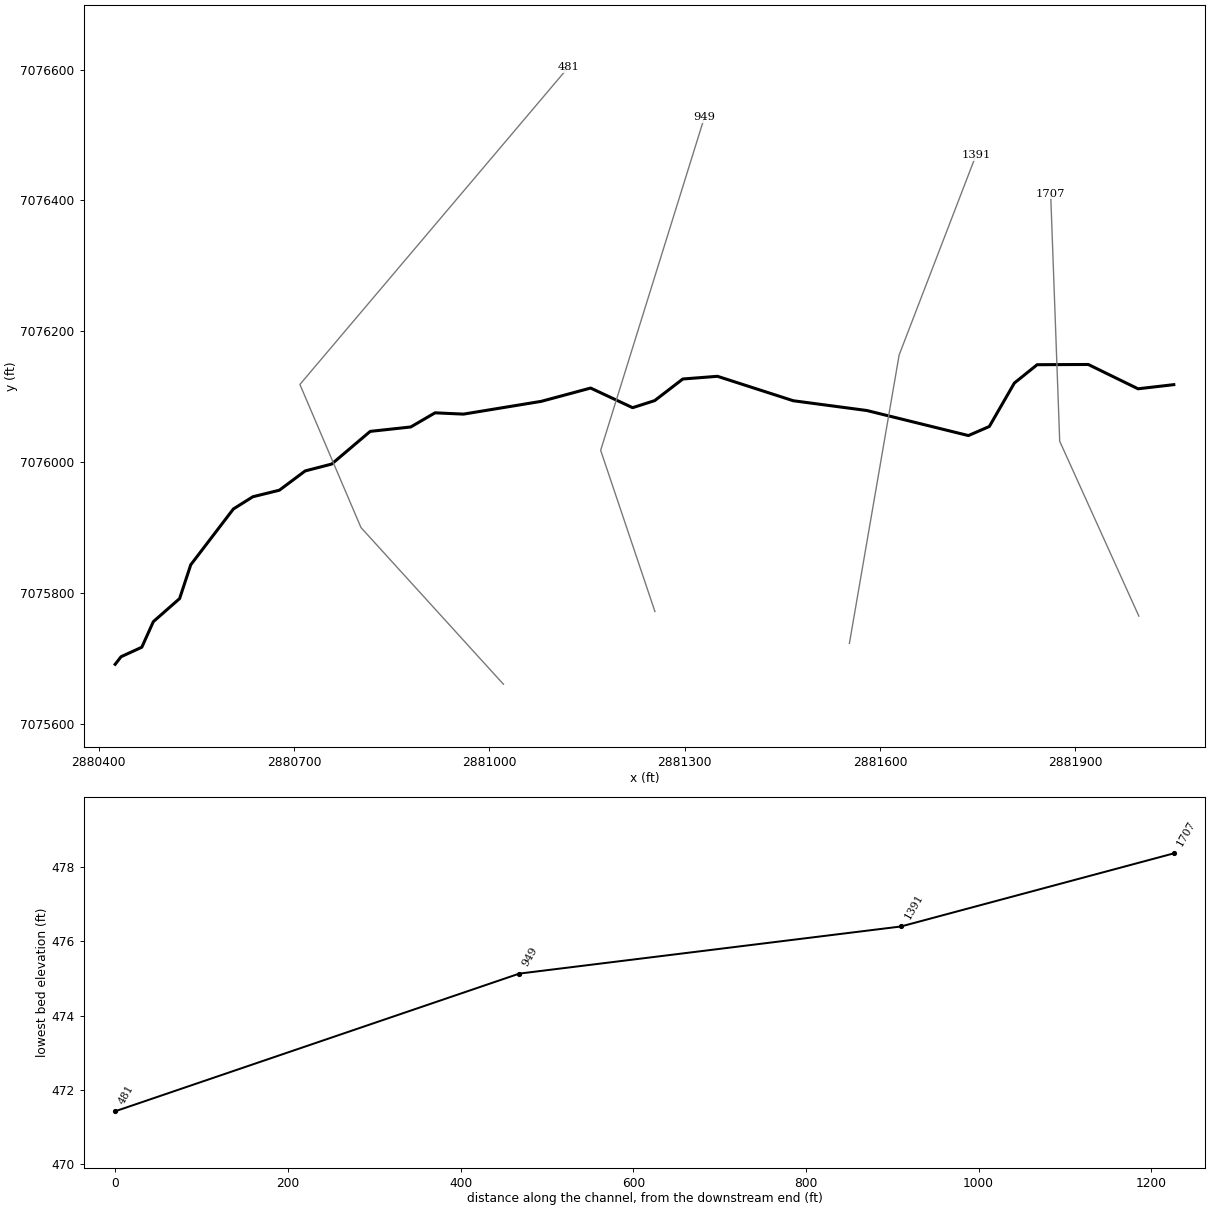
--- UNT 073 in Running Cr Watershed.prj (project) ---

Proj Title=UNT 073 in Running Cr Watershed Base Level Engineering
Current Plan=p01
Default Exp/Contr=0.3,0.1
English Units
Geom File=g01
Flow File=f01
Plan File=p01
BEGIN DESCRIPTION:
UNT 073 in Running Cr Watershed
END DESCRIPTION:

--- UNT 073 in Running Cr Watershed.p01 (plan) ---

Plan Title=Multiple Run
Short Identifier=Multiple
Geom File=g01
Flow File=f01
Subcritical Flow
K Sum by GR= 0
Std Step Tol= 0.01
Critical Tol= 0.01
Num of Std Step Trials= 20
Max Error Tol= 0.3
Flow Tol Ratio= 0.001
Split Flow NTrial= 30
Split Flow Tol= 0.02
Split Flow Ratio= 0.02
Log Output Level= 0
Friction Slope Method= 1
Unsteady Friction Slope Method= 2
Unsteady Bridges Friction Slope Method= 1
Parabolic Critical Depth
Global Vel Dist=  1 , 1 , 1
Global Log Level= 0
CheckData=True
Encroach Param= -1, 0, 0, 0
BEGIN DESCRIPTION:
Multiple Run
END DESCRIPTION:

--- UNT 073 in Running Cr Watershed.f01 (steady flow) ---

Flow Title=Multiple
Number of Profiles=7
Profile Names=10-year,25-year,50-year,1pct_min,100-year,1pct_plu,500-year
River Rch & RM= UNT 073 in Runni,Reach-1,1707
     433     564     668     394     785    1567    1079
Boundary for River Rch & Prof#=UNT 073 in Runni,Reach-1,1
Up Type=0
Dn Type=3
Dn Slope=0.005
Boundary for River Rch & Prof#=UNT 073 in Runni,Reach-1,2
Up Type=0
Dn Type=3
Dn Slope=0.005
Boundary for River Rch & Prof#=UNT 073 in Runni,Reach-1,3
Up Type=0
Dn Type=3
Dn Slope=0.005
Boundary for River Rch & Prof#=UNT 073 in Runni,Reach-1,4
Up Type=0
Dn Type=3
Dn Slope=0.005
Boundary for River Rch & Prof#=UNT 073 in Runni,Reach-1,5
Up Type=0
Dn Type=3
Dn Slope=0.005
Boundary for River Rch & Prof#=UNT 073 in Runni,Reach-1,6
Up Type=0
Dn Type=3
Dn Slope=0.005
Boundary for River Rch & Prof#=UNT 073 in Runni,Reach-1,7
Up Type=0
Dn Type=3
Dn Slope=0.005

--- UNT 073 in Running Cr Watershed.g01 (geometry) ---

Geom Title=Existing Conditions

River Reach=UNT 073 in Runni,Reach-1
Reach XY= 30
      2882051.10      7076118.31      2881996.20      7076111.97
      2881919.82      7076149.14      2881841.30      7076148.81
      2881806.29      7076120.77      2881767.87      7076054.34
      2881735.72      7076040.47      2881579.79      7076078.77
      2881466.83      7076093.70      2881350.45      7076131.07
      2881297.20      7076126.95      2881254.01      7076093.90
      2881220.12      7076083.09      2881155.67      7076113.09
      2881079.82      7076092.77      2880960.40      7076073.25
      2880916.77      7076075.24      2880879.50      7076053.61
      2880817.20      7076046.86      2880758.02      7075996.88
      2880717.37      7075986.40      2880677.70      7075956.91
      2880637.02      7075946.92      2880607.14      7075928.27
      2880541.64      7075842.89      2880524.52      7075791.21
      2880484.22      7075756.01      2880466.48      7075716.85
      2880434.63      7075702.34      2880425.59      7075690.71

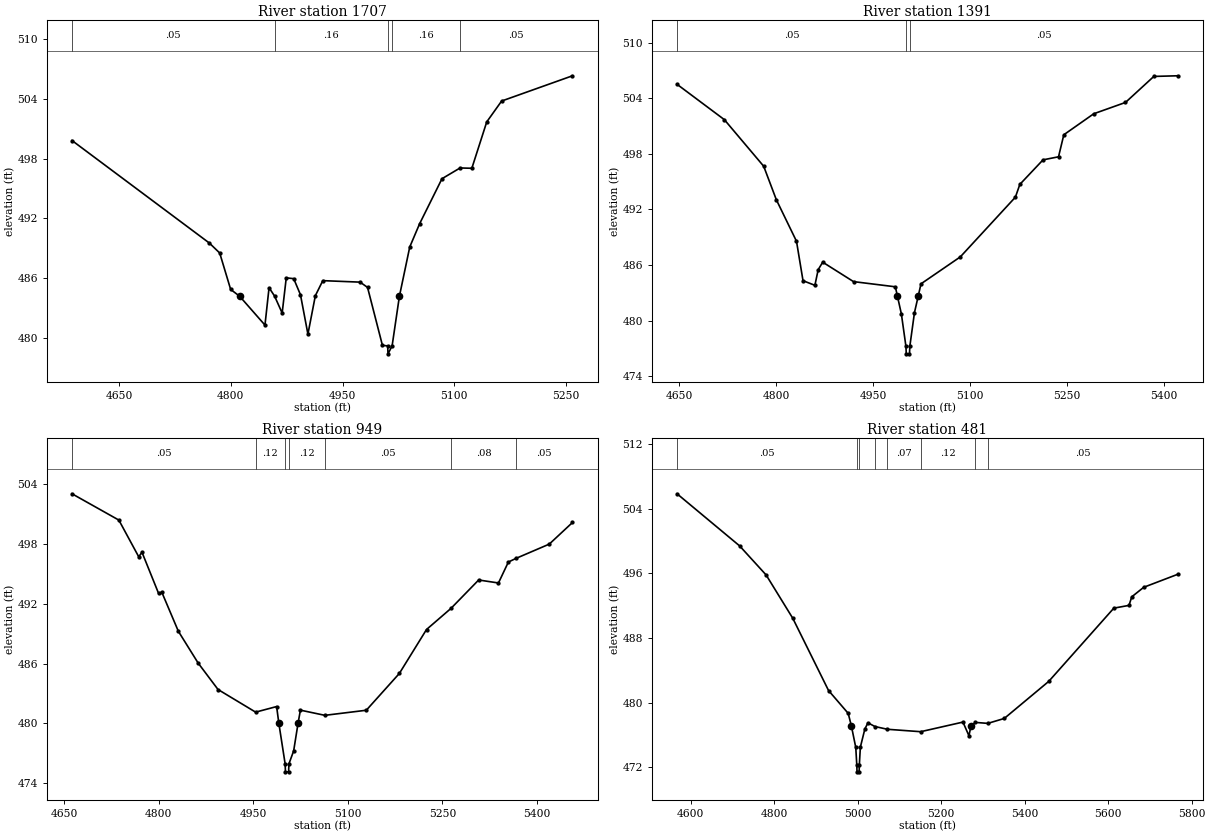
Type RM Length L Ch R = 1,1707,316,316,316
BEGIN DESCRIPTION:
UNT 073 in Running Cr Watershed 3.0
END DESCRIPTION:
XS GIS Cut Line= 3
      2881997.46      7075764.42      2881875.93      7076031.80
      2881862.04      7076410.14
#Sta/Elev= 30
  4586.6  499.82  4771.1  489.51  4785.0  488.51  4799.7  484.85  4811.8  484.16
  4845.8  481.26  4851.3  485.02  4858.7  484.18  4868.9  482.47  4874.4  486.01
  4884.4  485.93  4893.5  484.31  4903.5  480.35  4913.5  484.22  4923.5  485.73
  4973.6  485.58  4983.6  485.05  5003.6  479.22  5010.6  479.17  5011.1  478.37
  5016.6  479.17  5026.4  484.16  5040.3  489.12  5053.6  491.46  5083.6  495.98
  5107.9  497.06  5123.7  497.03  5143.7  501.69  5163.7  503.79  5258.9  506.33
#Mann=5,-1,0
  4586.6    0.05       0  4858.7    0.16       0  5010.6    0.07       0
  5016.6    0.16       0  5107.9    0.05       0
Bank Sta=4811.8,5026.4
Exp/Cntr=0.3,0.1

Type RM Length L Ch R = 1,1391,442,442,442
BEGIN DESCRIPTION:
UNT 073 in Running Cr Watershed 2.0
END DESCRIPTION:
XS GIS Cut Line= 3
      2881553.01      7075722.74      2881629.40      7076163.74
      2881747.44      7076469.26
#Sta/Elev= 30
  4646.3  505.51  4719.6  501.69  4780.5  496.66  4800.1  493.04  4831.3  488.56
  4841.4  484.30  4859.8  483.80  4864.9  485.49  4871.9  486.30  4919.6  484.20
  4984.4  483.64  4987.6  482.63  4993.7  480.72  5000.8  477.20  5001.3  476.40
  5006.3  476.40  5006.8  477.20  5014.0  480.85  5019.8  482.63  5024.1  483.96
  5085.0  486.87  5170.3  493.32  5177.2  494.70  5213.1  497.35  5237.1  497.68
  5245.3  500.06  5291.7  502.33  5340.8  503.55  5384.7  506.36  5421.4  506.43
#Mann=3,-1,0
  4646.3    0.05       0  5000.8    0.03       0  5006.8    0.05       0
Bank Sta=4987.6,5019.8
Exp/Cntr=0.3,0.1

Type RM Length L Ch R = 1,949,468,468,468
BEGIN DESCRIPTION:
Mapping XS 20b0a609
END DESCRIPTION:
XS GIS Cut Line= 3
      2881254.40      7075771.38      2881171.07      7076017.91
      2881330.38      7076527.03
#Sta/Elev= 30
  4662.7  503.03  4737.0  500.39  4768.5  496.71  4773.7  497.16  4799.9  493.05
  4805.2  493.14  4831.4  489.23  4862.8  486.04  4894.3  483.39  4953.9  481.12
  4987.2  481.68  4990.7  480.01  5000.7  475.93  5001.2  475.13  5006.2  475.13
  5006.7  475.93  5014.2  477.23  5021.2  480.01  5024.9  481.32  5063.7  480.80
  5129.4  481.31  5181.8  485.00  5224.9  489.41  5263.7  491.53  5307.6  494.38
  5339.0  494.08  5354.7  496.18  5366.9  496.55  5419.6  497.98  5456.4  500.15
#Mann=7,-1,0
  4662.7    0.05       0  4953.9    0.12       0  5000.7    0.07       0
  5006.7    0.12       0  5063.7    0.05       0  5263.7    0.08       0
  5366.9    0.05       0
Bank Sta=4990.7,5021.2
Exp/Cntr=0.3,0.1

Type RM Length L Ch R = 1,481,0,0,0
BEGIN DESCRIPTION:
UNT 073 in Running Cr Watershed 1.0
END DESCRIPTION:
XS GIS Cut Line= 4
      2881021.77      7075660.26      2880803.01      7075899.85
      2880709.26      7076118.60      2881121.21      7076603.25
#Sta/Elev= 30
  4567.7  505.85  4717.5  499.40  4781.0  495.80  4844.9  490.43  4930.5  481.49
  4977.6  478.66  4985.2  477.10  4995.7  474.44  4998.2  472.22  4998.7  471.42
  5003.7  471.42  5004.2  472.22  5006.7  474.48  5017.4  476.71  5024.8  477.49
  5041.7  477.03  5071.4  476.69  5151.1  476.39  5252.4  477.58  5266.7  475.89
  5271.6  477.10  5282.1  477.54  5311.9  477.42  5351.3  478.03  5457.8  482.62
  5613.7  491.69  5650.0  492.03  5656.6  493.09  5685.2  494.27  5766.2  495.87
#Mann=8,-1,0
  4567.7    0.05       0  4998.2    0.03       0  5004.2    0.05       0
  5041.7    0.12       0  5071.4    0.07       0  5151.1    0.12       0
  5282.1    0.07       0  5311.9    0.05       0
Bank Sta=4985.2,5271.6
Exp/Cntr=0.3,0.1

Chan Stop Cuts=-1