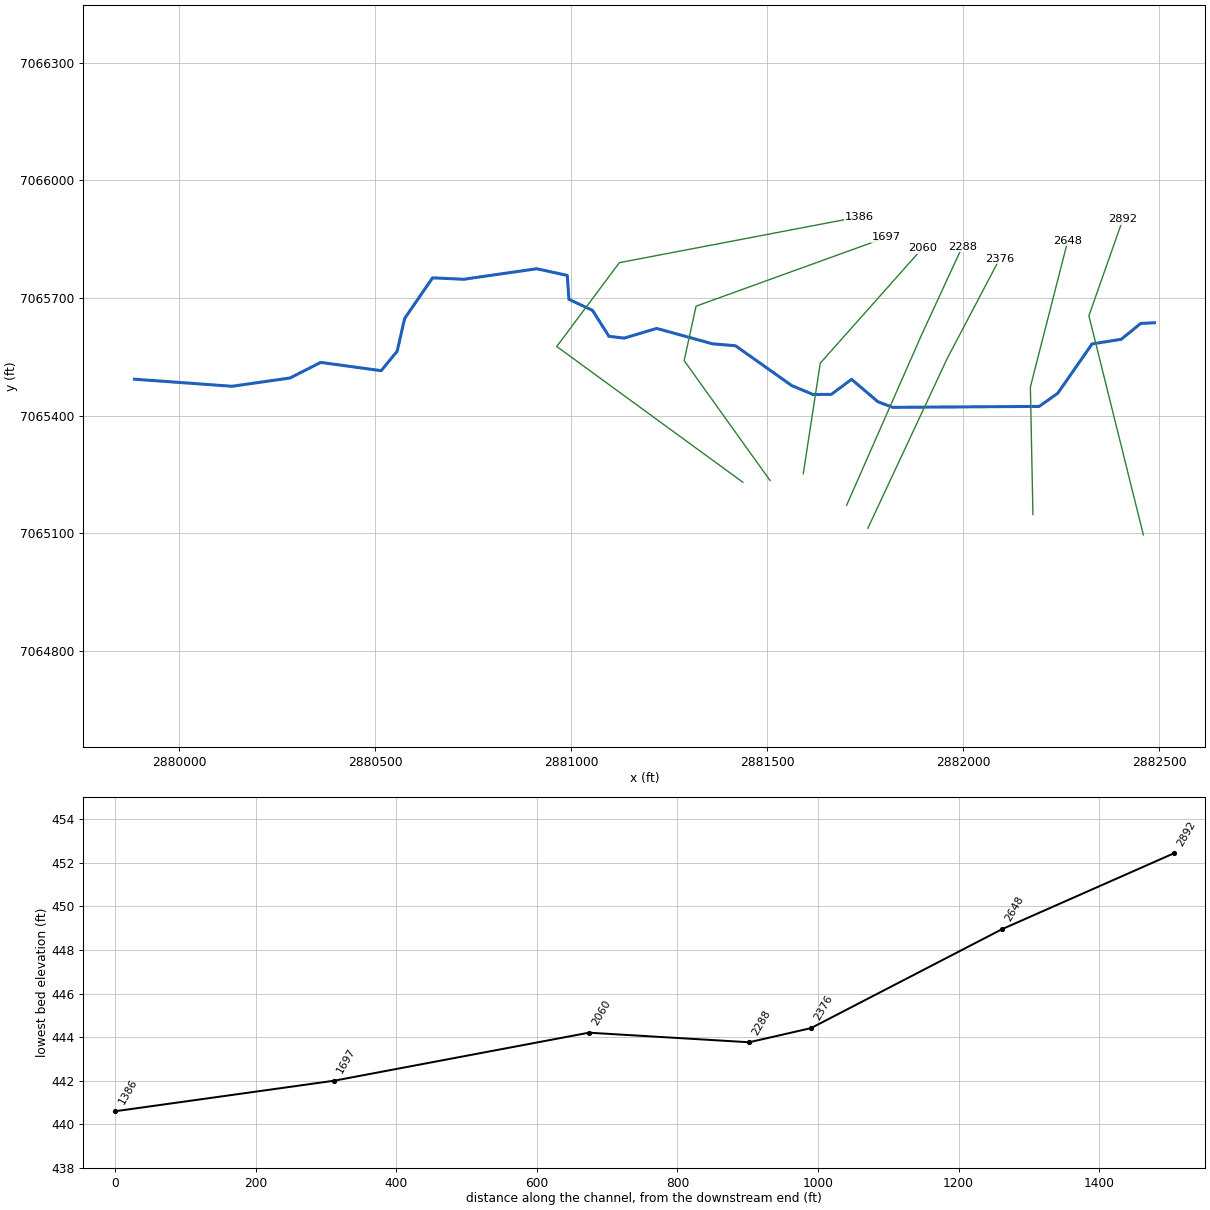
--- UNT 074 in Running Cr Watershed.prj (project) ---

Proj Title=UNT 074 in Running Cr Watershed Base Level Engineering
Current Plan=p01
Default Exp/Contr=0.3,0.1
English Units
Geom File=g01
Flow File=f01
Plan File=p01
BEGIN DESCRIPTION:
UNT 074 in Running Cr Watershed
END DESCRIPTION:

--- UNT 074 in Running Cr Watershed.p01 (plan) ---

Plan Title=Multiple Run
Short Identifier=Multiple
Geom File=g01
Flow File=f01
Subcritical Flow
K Sum by GR= 0
Std Step Tol= 0.01
Critical Tol= 0.01
Num of Std Step Trials= 20
Max Error Tol= 0.3
Flow Tol Ratio= 0.001
Split Flow NTrial= 30
Split Flow Tol= 0.02
Split Flow Ratio= 0.02
Log Output Level= 0
Friction Slope Method= 1
Unsteady Friction Slope Method= 2
Unsteady Bridges Friction Slope Method= 1
Parabolic Critical Depth
Global Vel Dist=  1 , 1 , 1
Global Log Level= 0
CheckData=True
Encroach Param= -1, 0, 0, 0
BEGIN DESCRIPTION:
Multiple Run
END DESCRIPTION:

--- UNT 074 in Running Cr Watershed.f01 (steady flow) ---

Flow Title=Multiple
Number of Profiles=7
Profile Names=10-year,25-year,50-year,1pct_min,100-year,1pct_plu,500-year
River Rch & RM= UNT 074 in Runni,Reach-1,2892
     400     519     612     359     717    1431     979
Boundary for River Rch & Prof#=UNT 074 in Runni,Reach-1,1
Up Type=0
Dn Type=3
Dn Slope=0.005
Boundary for River Rch & Prof#=UNT 074 in Runni,Reach-1,2
Up Type=0
Dn Type=3
Dn Slope=0.005
Boundary for River Rch & Prof#=UNT 074 in Runni,Reach-1,3
Up Type=0
Dn Type=3
Dn Slope=0.005
Boundary for River Rch & Prof#=UNT 074 in Runni,Reach-1,4
Up Type=0
Dn Type=3
Dn Slope=0.005
Boundary for River Rch & Prof#=UNT 074 in Runni,Reach-1,5
Up Type=0
Dn Type=3
Dn Slope=0.005
Boundary for River Rch & Prof#=UNT 074 in Runni,Reach-1,6
Up Type=0
Dn Type=3
Dn Slope=0.005
Boundary for River Rch & Prof#=UNT 074 in Runni,Reach-1,7
Up Type=0
Dn Type=3
Dn Slope=0.005

--- UNT 074 in Running Cr Watershed.g01 (geometry) ---

Geom Title=Existing Conditions

River Reach=UNT 074 in Runni,Reach-1
Reach XY= 30
      2882488.35      7065636.86      2882453.32      7065635.14
      2882403.92      7065594.79      2882329.26      7065582.81
      2882241.92      7065457.21      2882194.53      7065423.47
      2881820.72      7065421.07      2881782.74      7065435.52
      2881715.62      7065492.62      2881664.17      7065454.20
      2881617.27      7065453.96      2881563.31      7065476.51
      2881419.56      7065578.27      2881361.52      7065583.03
      2881218.63      7065622.45      2881135.55      7065597.67
      2881096.84      7065602.32      2881055.04      7065668.38
      2880994.66      7065696.76      2880990.53      7065757.66
      2880912.60      7065774.69      2880726.30      7065747.85
      2880646.83      7065751.46      2880575.61      7065647.73
      2880556.52      7065564.13      2880515.75      7065514.59
      2880361.44      7065535.75      2880283.52      7065496.01
      2880135.41      7065474.85      2879886.30      7065492.89

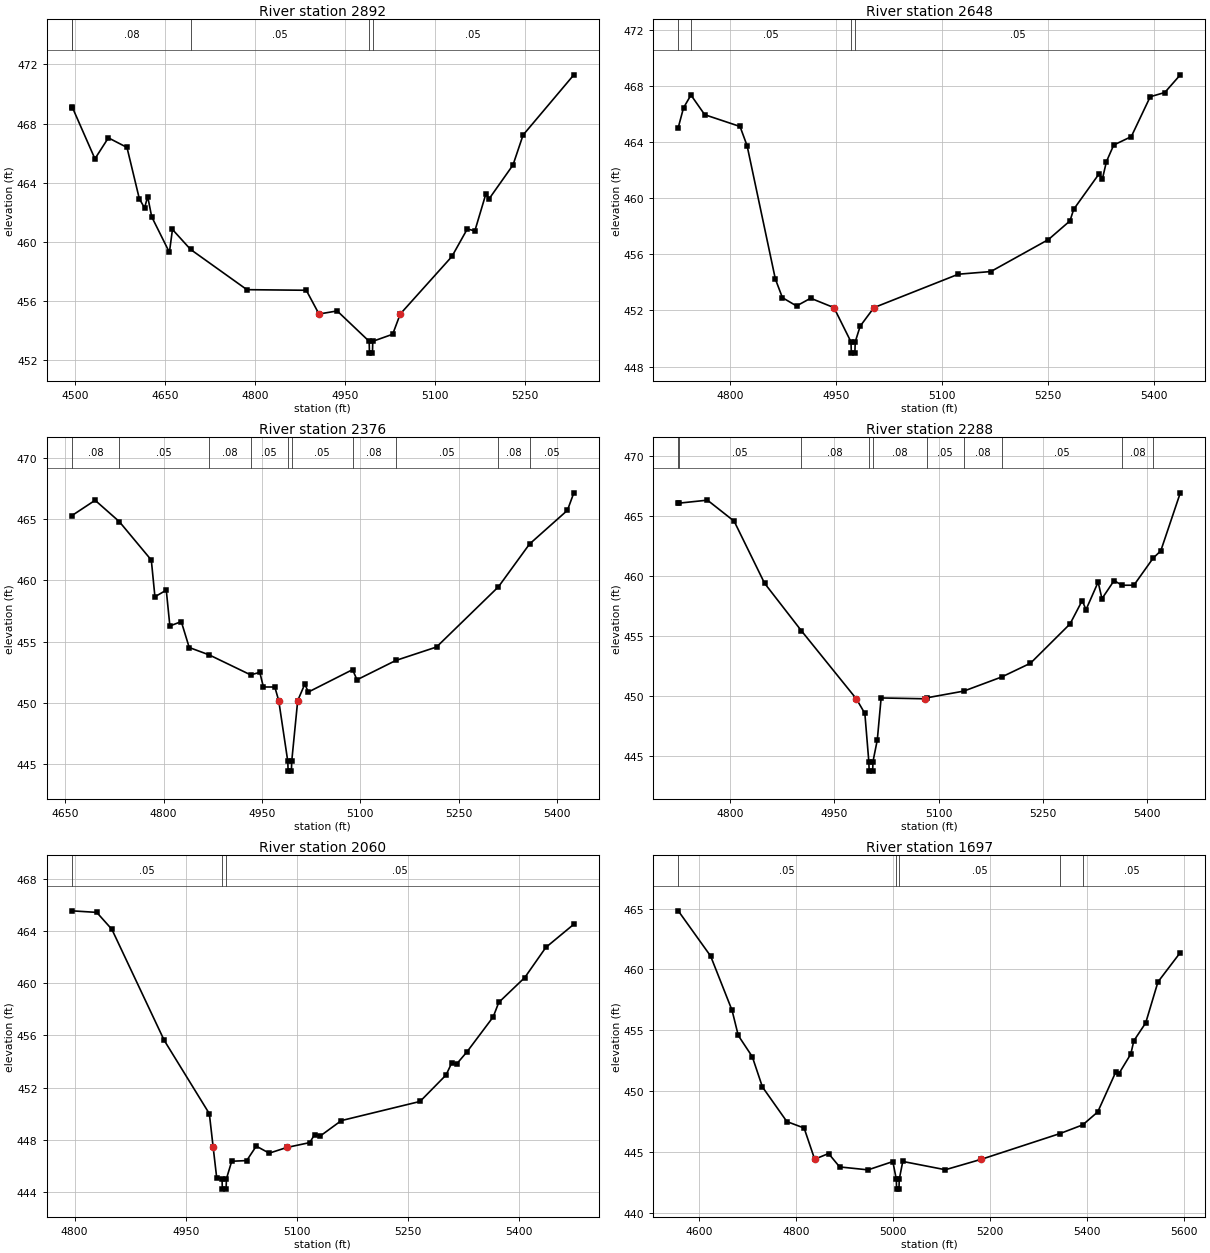
Type RM Length L Ch R = 1,2892,244,244,244
BEGIN DESCRIPTION:
UNT 074 in Running Cr Watershed 2.0
END DESCRIPTION:
XS GIS Cut Line= 3
      2882460.13      7065095.76      2882321.24      7065654.77
      2882407.82      7065900.67
#Sta/Elev= 30
  4494.5  469.04  4495.2  469.12  4533.1  465.61  4555.5  467.03  4586.5  466.38
  4607.1  462.90  4615.8  462.28  4621.0  463.05  4627.7  461.68  4657.2  459.27
  4662.3  460.82  4692.4  459.47  4786.4  456.74  4885.3  456.70  4906.5  455.09
  4936.8  455.30  4990.1  453.24  4990.6  452.44  4995.6  452.44  4996.1  453.24
  5029.3  453.72  5041.9  455.09  5128.0  458.99  5153.7  460.86  5166.2  460.72
  5184.6  463.23  5189.9  462.89  5229.8  465.19  5246.6  467.22  5331.2  471.30
#Mann=5,-1,0
  4494.5    0.05       0  4495.2    0.08       0  4692.4    0.05       0
  4990.1    0.03       0  4996.1    0.05       0
Bank Sta=4906.5,5041.9
Exp/Cntr=0.3,0.1

Type RM Length L Ch R = 1,2648,272,272,272
BEGIN DESCRIPTION:
Mapping XS 35cd84e6
END DESCRIPTION:
XS GIS Cut Line= 3
      2882178.45      7065147.50      2882171.93      7065473.06
      2882267.42      7065846.31
#Sta/Elev= 30
  4726.0  465.02  4733.5  466.43  4744.0  467.34  4763.5  465.94  4813.5  465.10
  4823.5  463.73  4863.5  454.24  4873.5  452.91  4893.5  452.32  4913.5  452.87
  4946.5  452.20  4970.6  449.76  4971.1  448.96  4976.1  448.96  4976.6  449.76
  4983.6  450.88  5003.1  452.20  5122.6  454.58  5168.6  454.77  5250.2  457.05
  5280.7  458.38  5285.9  459.20  5321.6  461.71  5326.7  461.39  5332.3  462.60
  5342.6  463.78  5367.5  464.38  5394.3  467.22  5414.9  467.52  5436.9  468.78
#Mann=4,-1,0
  4726.0    0.08       0  4744.0    0.05       0  4970.6    0.03       0
  4976.6    0.05       0
Bank Sta=4946.5,5003.1
Exp/Cntr=0.3,0.1

Type RM Length L Ch R = 1,2376,88,88,88
BEGIN DESCRIPTION:
Mapping XS bb12ef7c
END DESCRIPTION:
XS GIS Cut Line= 3
      2881757.42      7065112.78      2881959.26      7065544.68
      2882093.62      7065800.39
#Sta/Elev= 30
  4659.9  465.30  4695.5  466.56  4732.3  464.82  4781.2  461.67  4786.7  458.67
  4804.0  459.21  4809.5  456.28  4826.9  456.64  4839.0  454.52  4869.7  453.91
  4932.7  452.28  4946.6  452.49  4952.1  451.29  4969.5  451.29  4975.5  450.17
  4989.3  445.21  4989.8  444.41  4994.8  444.41  4995.3  445.21  5004.4  450.17
  5015.2  451.52  5020.7  450.88  5088.1  452.71  5094.8  451.88  5154.0  453.46
  5216.1  454.56  5310.6  459.49  5357.9  462.98  5415.7  465.74  5425.5  467.17
#Mann=10,-1,0
  4659.9    0.08       0  4732.3    0.05       0  4869.7    0.08       0
  4932.7    0.05       0  4989.3    0.04       0  4995.3    0.05       0
  5088.1    0.08       0  5154.0    0.05       0  5310.6    0.08       0
  5357.9    0.05       0
Bank Sta=4975.5,5004.4
Exp/Cntr=0.3,0.1

Type RM Length L Ch R = 1,2288,228,228,228
BEGIN DESCRIPTION:
Mapping XS c034a108
END DESCRIPTION:
XS GIS Cut Line= 3
      2881703.18      7065171.40      2881894.16      7065605.44
      2881998.04      7065830.52
#Sta/Elev= 30
  4725.5  466.06  4726.4  466.06  4767.5  466.31  4805.9  464.56  4849.6  459.40
  4902.5  455.45  4981.6  449.78  4993.9  448.56  4999.6  444.56  5000.1  443.76
  5005.1  443.76  5005.6  444.56  5011.8  446.36  5017.3  449.85  5080.4  449.78
  5082.9  449.86  5136.2  450.42  5190.9  451.60  5232.1  452.74  5289.0  456.01
  5306.5  457.95  5312.0  457.20  5329.4  459.49  5334.9  458.11  5352.4  459.62
  5363.5  459.23  5380.8  459.23  5408.6  461.49  5419.5  462.09  5447.6  466.92
#Mann=10,-1,0
  4725.5    0.08       0  4726.4    0.05       0  4902.5    0.08       0
  4999.6    0.07       0  5005.6    0.08       0  5082.9    0.05       0
  5136.2    0.08       0  5190.9    0.05       0  5363.5    0.08       0
  5408.6    0.05       0
Bank Sta=4981.6,5080.4
Exp/Cntr=0.3,0.1

Type RM Length L Ch R = 1,2060,363,363,363
BEGIN DESCRIPTION:
Mapping XS b00d4cef
END DESCRIPTION:
XS GIS Cut Line= 3
      2881592.51      7065251.74      2881635.91      7065533.82
      2881896.34      7065826.81
#Sta/Elev= 30
  4796.3  465.56  4830.0  465.44  4850.4  464.14  4921.0  455.62  4981.9  449.99
  4987.1  447.40  4991.8  445.09  4999.0  445.00  4999.5  444.20  5004.5  444.20
  5005.0  445.00  5012.1  446.34  5032.3  446.39  5045.2  447.50  5062.7  446.96
  5086.6  447.40  5117.3  447.77  5124.0  448.39  5131.6  448.28  5160.0  449.46
  5266.2  450.93  5301.3  452.96  5308.8  453.87  5315.5  453.80  5329.7  454.75
  5364.9  457.42  5372.4  458.53  5407.5  460.44  5435.9  462.75  5473.7  464.53
#Mann=3,-1,0
  4796.3    0.05       0  4999.0    0.03       0  5005.0    0.05       0
Bank Sta=4987.1,5086.6
Exp/Cntr=0.3,0.1

Type RM Length L Ch R = 1,1697,311,311,311
BEGIN DESCRIPTION:
Mapping XS df3622bc
END DESCRIPTION:
XS GIS Cut Line= 4
      2881507.88      7065234.33      2881288.69      7065540.33
      2881319.07      7065679.22      2881805.19      7065855.01
#Sta/Elev= 30
  4556.4  464.81  4623.2  461.10  4667.4  456.65  4680.2  454.59  4709.1  452.85
  4730.0  450.37  4780.4  447.53  4816.0  447.00  4837.8  444.44  4866.4  444.91
  4889.3  443.81  4947.8  443.57  4999.0  444.25  5006.2  442.79  5006.7  441.99
  5011.7  441.99  5012.2  442.79  5019.5  444.26  5107.3  443.58  5181.8  444.44
  5344.0  446.55  5390.7  447.26  5421.6  448.32  5459.2  451.63  5464.5  451.41
  5489.8  453.07  5496.0  454.15  5520.5  455.62  5545.8  458.98  5591.9  461.39
#Mann=5,-1,0
  4556.4    0.05       0  5006.2    0.03       0  5012.2    0.05       0
  5344.0    0.16       0  5390.7    0.05       0
Bank Sta=4837.8,5181.8
Exp/Cntr=0.3,0.1

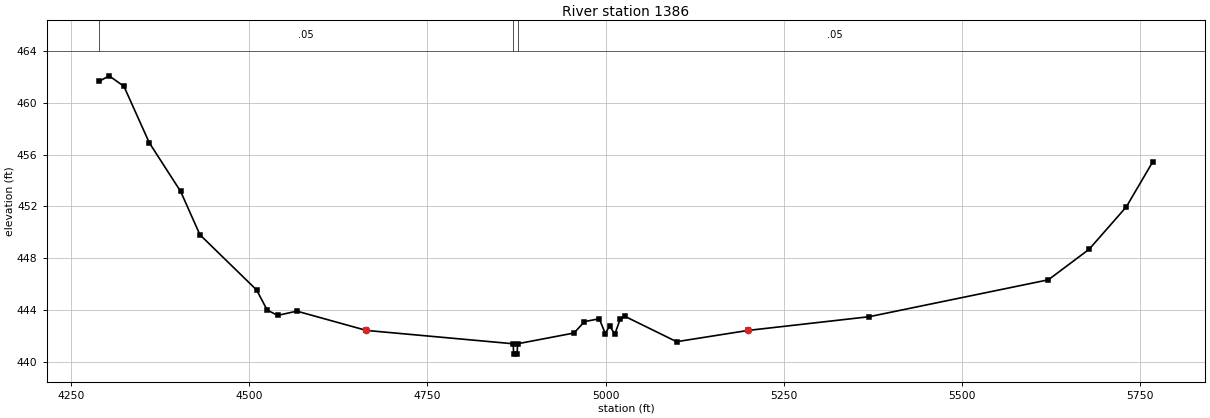
Type RM Length L Ch R = 1,1386,0,0,0
BEGIN DESCRIPTION:
UNT 074 in Running Cr Watershed 1.0
END DESCRIPTION:
XS GIS Cut Line= 4
      2881438.41      7065230.02      2880963.72      7065576.26
      2881123.32      7065790.19      2881735.71      7065907.08
#Sta/Elev= 30
  4289.8  461.66  4303.5  462.08  4324.3  461.27  4359.9  456.91  4403.9  453.15
  4430.9  449.81  4510.5  445.54  4525.2  444.00  4539.9  443.58  4566.9  443.91
  4664.5  442.42  4870.5  441.39  4871.0  440.59  4876.0  440.59  4876.5  441.39
  4955.8  442.22  4970.4  443.10  4991.2  443.32  4999.6  442.18  5005.8  442.77
  5013.0  442.13  5020.4  443.27  5026.7  443.52  5099.7  441.55  5199.9  442.42
  5369.9  443.48  5621.3  446.33  5678.5  448.69  5730.6  451.96  5767.7  455.44
#Mann=3,-1,0
  4289.8    0.05       0  4870.5    0.03       0  4876.5    0.05       0
Bank Sta=4664.5,5199.9
Exp/Cntr=0.3,0.1

Chan Stop Cuts=-1