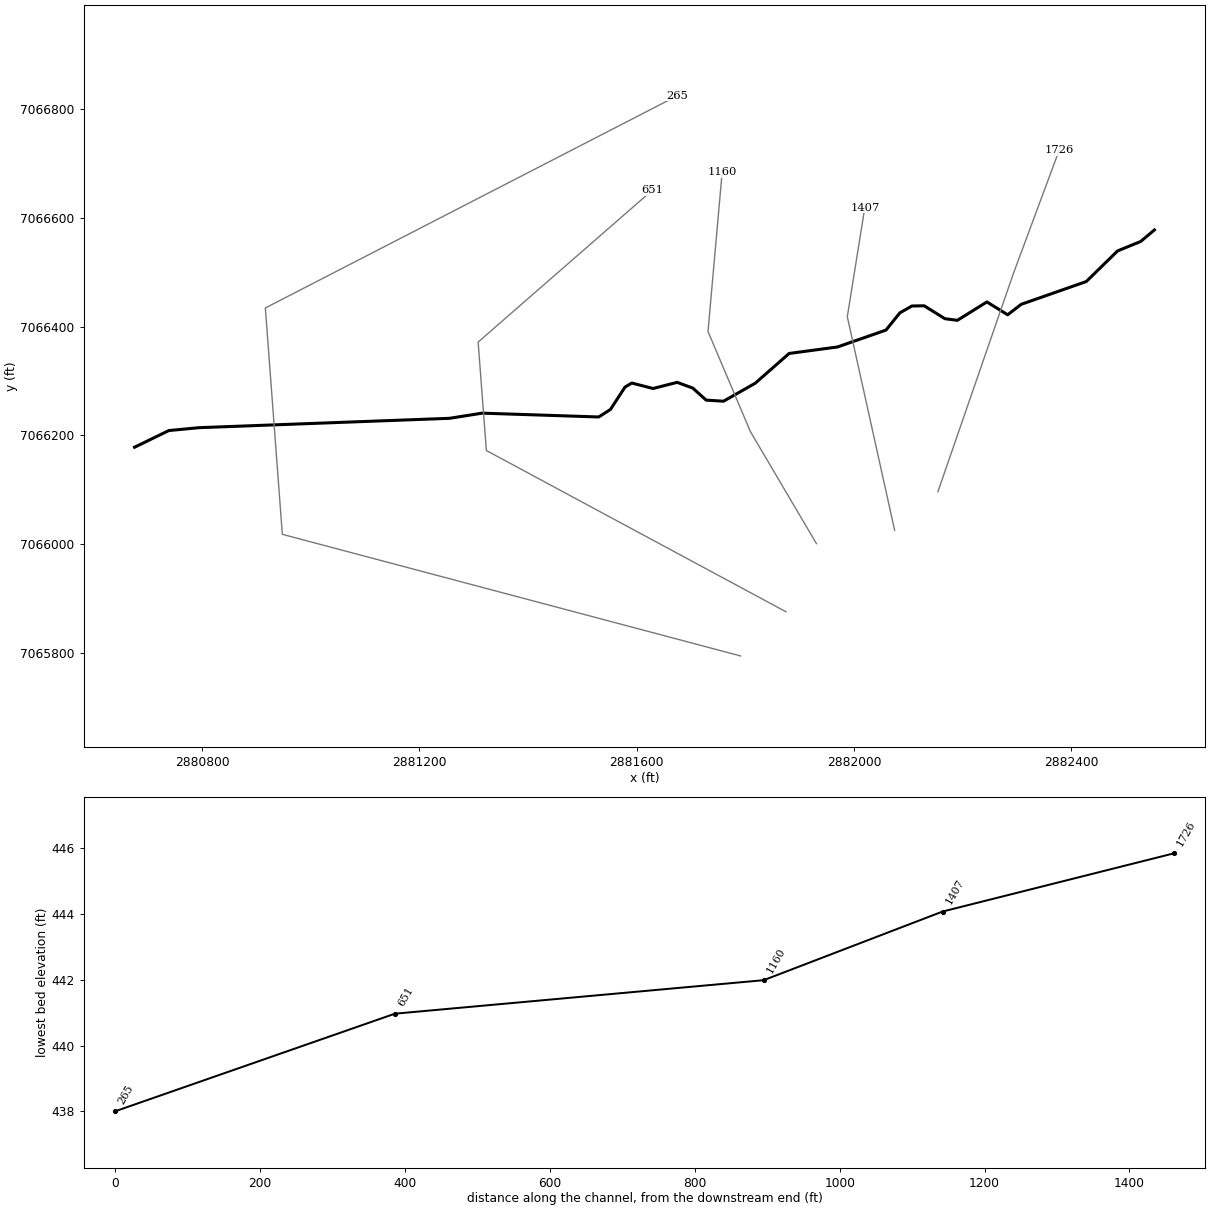
--- UNT 075 in Running Cr Watershed.prj (project) ---

Proj Title=UNT 075 in Running Cr Watershed Base Level Engineering
Current Plan=p01
Default Exp/Contr=0.3,0.1
English Units
Geom File=g01
Flow File=f01
Plan File=p01
BEGIN DESCRIPTION:
UNT 075 in Running Cr Watershed
END DESCRIPTION:

--- UNT 075 in Running Cr Watershed.p01 (plan) ---

Plan Title=Multiple Run
Short Identifier=Multiple
Geom File=g01
Flow File=f01
Subcritical Flow
K Sum by GR= 0
Std Step Tol= 0.01
Critical Tol= 0.01
Num of Std Step Trials= 20
Max Error Tol= 0.3
Flow Tol Ratio= 0.001
Split Flow NTrial= 30
Split Flow Tol= 0.02
Split Flow Ratio= 0.02
Log Output Level= 0
Friction Slope Method= 1
Unsteady Friction Slope Method= 2
Unsteady Bridges Friction Slope Method= 1
Parabolic Critical Depth
Global Vel Dist=  1 , 1 , 1
Global Log Level= 0
CheckData=True
Encroach Param= -1, 0, 0, 0
BEGIN DESCRIPTION:
Multiple Run
END DESCRIPTION:

--- UNT 075 in Running Cr Watershed.f01 (steady flow) ---

Flow Title=Multiple
Number of Profiles=7
Profile Names=10-year,25-year,50-year,1pct_min,100-year,1pct_plu,500-year
River Rch & RM= UNT 075 in Runni,Reach-1,1726
     489     643     766     454     906    1807    1261
Boundary for River Rch & Prof#=UNT 075 in Runni,Reach-1,1
Up Type=0
Dn Type=3
Dn Slope=0.005
Boundary for River Rch & Prof#=UNT 075 in Runni,Reach-1,2
Up Type=0
Dn Type=3
Dn Slope=0.005
Boundary for River Rch & Prof#=UNT 075 in Runni,Reach-1,3
Up Type=0
Dn Type=3
Dn Slope=0.005
Boundary for River Rch & Prof#=UNT 075 in Runni,Reach-1,4
Up Type=0
Dn Type=3
Dn Slope=0.005
Boundary for River Rch & Prof#=UNT 075 in Runni,Reach-1,5
Up Type=0
Dn Type=3
Dn Slope=0.005
Boundary for River Rch & Prof#=UNT 075 in Runni,Reach-1,6
Up Type=0
Dn Type=3
Dn Slope=0.005
Boundary for River Rch & Prof#=UNT 075 in Runni,Reach-1,7
Up Type=0
Dn Type=3
Dn Slope=0.005

--- UNT 075 in Running Cr Watershed.g01 (geometry) ---

Geom Title=Existing Conditions

River Reach=UNT 075 in Runni,Reach-1
Reach XY= 30
      2882553.22      7066577.95      2882527.96      7066556.72
      2882485.52      7066539.39      2882427.75      7066482.94
      2882308.01      7066441.03      2882283.06      7066421.75
      2882244.81      7066445.38      2882190.42      7066411.55
      2882167.42      7066414.56      2882129.39      7066438.30
      2882106.79      7066437.93      2882084.64      7066425.32
      2882059.01      7066393.57      2881969.75      7066362.49
      2881880.73      7066350.55      2881818.43      7066295.80
      2881759.96      7066262.64      2881728.07      7066264.60
      2881703.29      7066286.84      2881674.59      7066297.36
      2881630.26      7066286.05      2881591.07      7066296.08
      2881578.59      7066288.63      2881551.88      7066247.55
      2881530.21      7066233.62      2881315.61      7066240.66
      2881255.49      7066231.16      2880794.44      7066213.91
      2880738.76      7066208.61      2880675.68      7066177.88

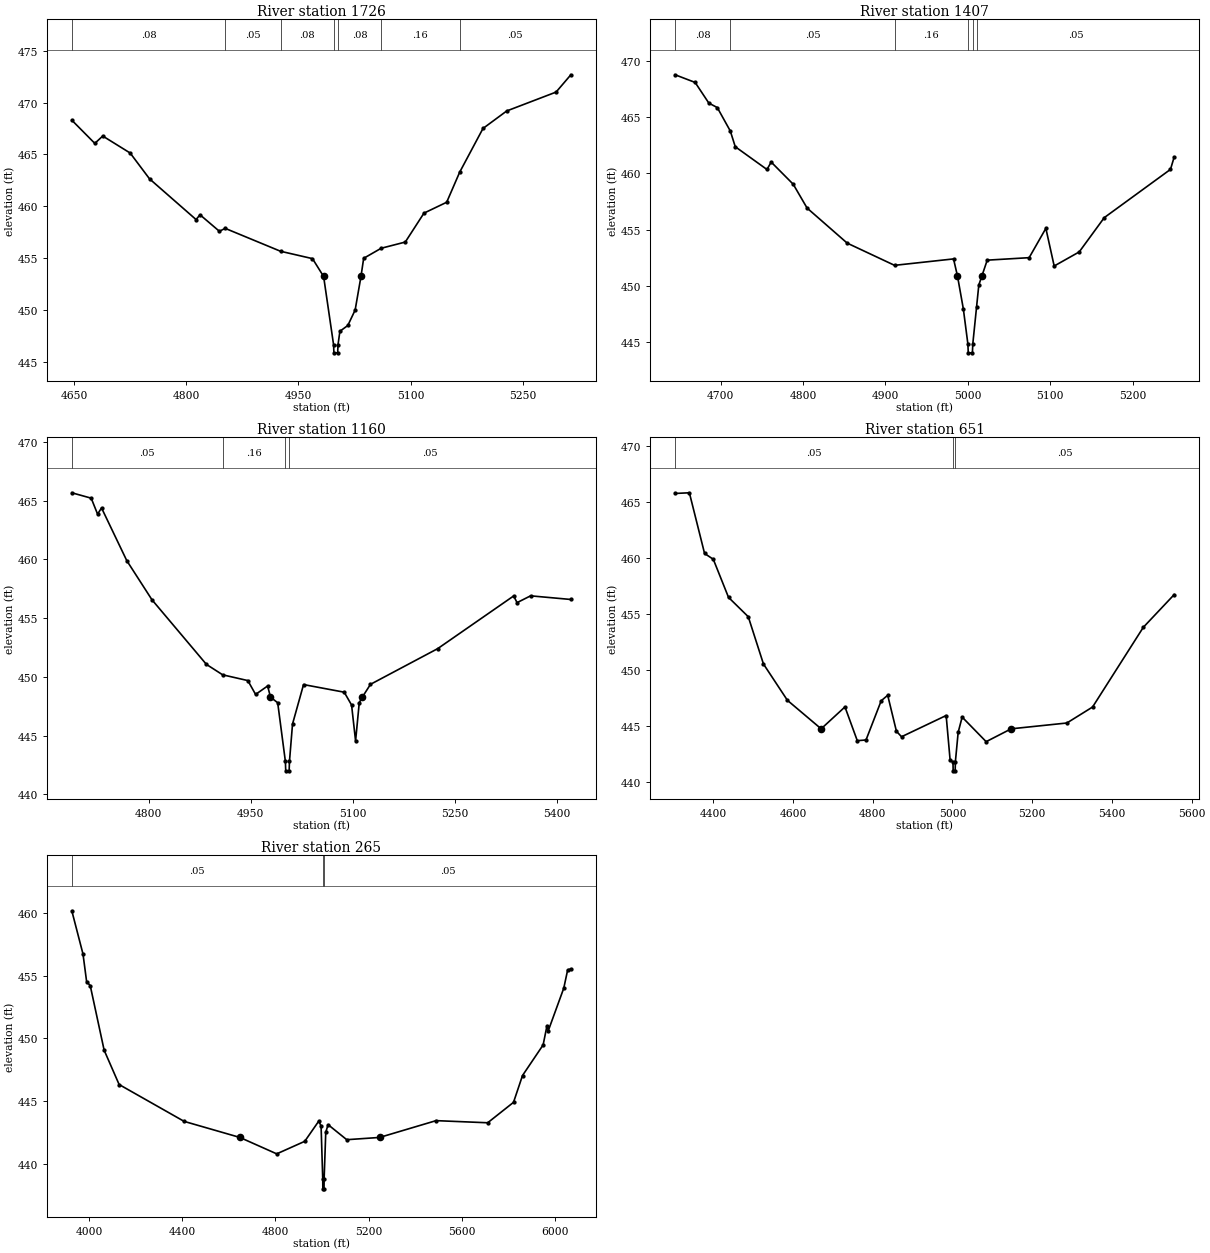
Type RM Length L Ch R = 1,1726,319,319,319
BEGIN DESCRIPTION:
UNT 075 in Running Cr Watershed 4.0
END DESCRIPTION:
XS GIS Cut Line= 3
      2882154.57      7066095.89      2882293.46      7066497.37
      2882378.10      7066725.23
#Sta/Elev= 30
  4646.7  468.30  4677.5  466.06  4688.1  466.77  4724.8  465.13  4750.7  462.64
  4813.0  458.71  4818.3  459.17  4844.2  457.58  4852.0  457.86  4926.1  455.65
  4968.8  454.94  4983.7  453.22  4997.0  446.65  4997.5  445.85  5002.5  445.85
  5003.0  446.65  5005.5  447.93  5016.1  448.49  5025.9  449.98  5033.7  453.22
  5037.3  454.97  5060.7  455.94  5093.0  456.54  5118.0  459.33  5148.4  460.38
  5165.8  463.28  5197.0  467.50  5228.8  469.19  5294.8  471.01  5314.6  472.68
#Mann=7,-1,0
  4646.7    0.08       0  4852.0    0.05       0  4926.1    0.08       0
  4997.0    0.07       0  5003.0    0.08       0  5060.7    0.16       0
  5165.8    0.05       0
Bank Sta=4983.7,5033.7
Exp/Cntr=0.3,0.1

Type RM Length L Ch R = 1,1407,247,247,247
BEGIN DESCRIPTION:
UNT 075 in Running Cr Watershed 3.0
END DESCRIPTION:
XS GIS Cut Line= 3
      2882074.99      7066025.05      2881987.84      7066418.13
      2882020.02      7066618.84
#Sta/Elev= 30
  4644.7  468.74  4669.0  468.06  4685.6  466.23  4695.9  465.83  4711.7  463.75
  4717.7  462.36  4756.2  460.34  4761.3  461.00  4788.1  459.03  4804.9  456.92
  4853.6  453.81  4911.1  451.84  4982.7  452.41  4987.5  450.89  4994.6  447.98
  5000.1  444.88  5000.6  444.08  5005.6  444.08  5006.1  444.88  5010.7  448.17
  5013.4  450.10  5017.1  450.89  5023.6  452.30  5074.5  452.52  5094.8  455.12
  5104.9  451.78  5135.3  453.03  5165.7  456.07  5246.1  460.35  5250.6  461.45
#Mann=6,-1,0
  4644.7    0.08       0  4711.7    0.05       0  4911.1    0.16       0
  5000.1    0.07       0  5006.1    0.16       0  5010.7    0.05       0
Bank Sta=4987.5,5017.1
Exp/Cntr=0.3,0.1

Type RM Length L Ch R = 1,1160,509,509,509
BEGIN DESCRIPTION:
Mapping XS 1ac9b834
END DESCRIPTION:
XS GIS Cut Line= 4
      2881931.03      7066000.43      2881809.52      7066206.57
      2881731.40      7066391.03      2881757.44      7066683.96
#Sta/Elev= 30
  4687.0  465.68  4715.5  465.22  4724.9  463.86  4730.7  464.39  4767.8  459.90
  4804.9  456.56  4884.9  451.06  4908.8  450.17  4945.8  449.68  4957.2  448.50
  4974.9  449.22  4979.1  448.27  4989.7  447.79  5001.0  442.79  5001.5  441.99
  5006.5  441.99  5007.0  442.79  5011.5  445.98  5027.7  449.34  5087.5  448.69
  5098.3  447.60  5104.2  444.54  5109.6  447.79  5114.1  448.27  5126.1  449.36
  5224.9  452.40  5336.6  456.89  5341.6  456.32  5361.5  456.90  5420.7  456.59
#Mann=4,-1,0
  4687.0    0.05       0  4908.8    0.16       0  5001.0    0.07       0
  5007.0    0.05       0
Bank Sta=4979.1,5114.1
Exp/Cntr=0.3,0.1

Type RM Length L Ch R = 1,651,386,386,386
BEGIN DESCRIPTION:
UNT 075 in Running Cr Watershed 2.0
END DESCRIPTION:
XS GIS Cut Line= 4
      2881875.00      7065875.00      2881323.41      7066171.85
      2881308.22      7066371.50      2881628.58      7066650.73
#Sta/Elev= 30
  4304.6  465.79  4340.3  465.85  4378.4  460.42  4400.3  459.90  4438.5  456.49
  4488.0  454.76  4526.1  450.53  4586.2  447.28  4670.8  444.73  4730.5  446.69
  4761.4  443.67  4783.3  443.73  4821.4  447.24  4837.7  447.73  4859.6  444.51
  4872.4  444.02  4984.3  445.92  4994.3  441.91  5001.4  441.77  5001.9  440.97
  5006.9  440.97  5007.4  441.77  5014.4  444.41  5024.4  445.78  5084.6  443.58
  5147.4  444.73  5287.0  445.25  5351.5  446.68  5478.7  453.81  5556.2  456.74
#Mann=3,-1,0
  4304.6    0.05       0  5001.4    0.03       0  5007.4    0.05       0
Bank Sta=4670.8,5147.4
Exp/Cntr=0.3,0.1

Type RM Length L Ch R = 1,265,0,0,0
BEGIN DESCRIPTION:
UNT 075 in Running Cr Watershed 1.0
END DESCRIPTION:
XS GIS Cut Line= 4
      2881791.52      7065793.66      2880947.75      7066017.62
      2880916.50      7066434.29      2881674.96      7066824.98
#Sta/Elev= 30
  3925.3  460.18  3973.4  456.73  3989.0  454.52  4004.5  454.21  4064.2  449.06
  4128.6  446.32  4408.0  443.38  4647.3  442.10  4805.7  440.79  4926.0  441.79
  4986.2  443.40  4996.2  443.02  5003.3  438.80  5003.8  438.00  5008.8  438.00
  5009.3  438.80  5016.3  442.51  5026.3  443.12  5106.5  441.92  5247.5  442.10
  5490.3  443.44  5712.0  443.27  5822.9  444.90  5861.6  447.04  5950.2  449.48
  5966.8  451.02  5972.4  450.62  6038.9  454.01  6055.5  455.46  6069.3  455.54
#Mann=3,-1,0
  3925.3    0.05       0  5003.3    0.03       0  5009.3    0.05       0
Bank Sta=4647.3,5247.5
Exp/Cntr=0.3,0.1

Chan Stop Cuts=-1