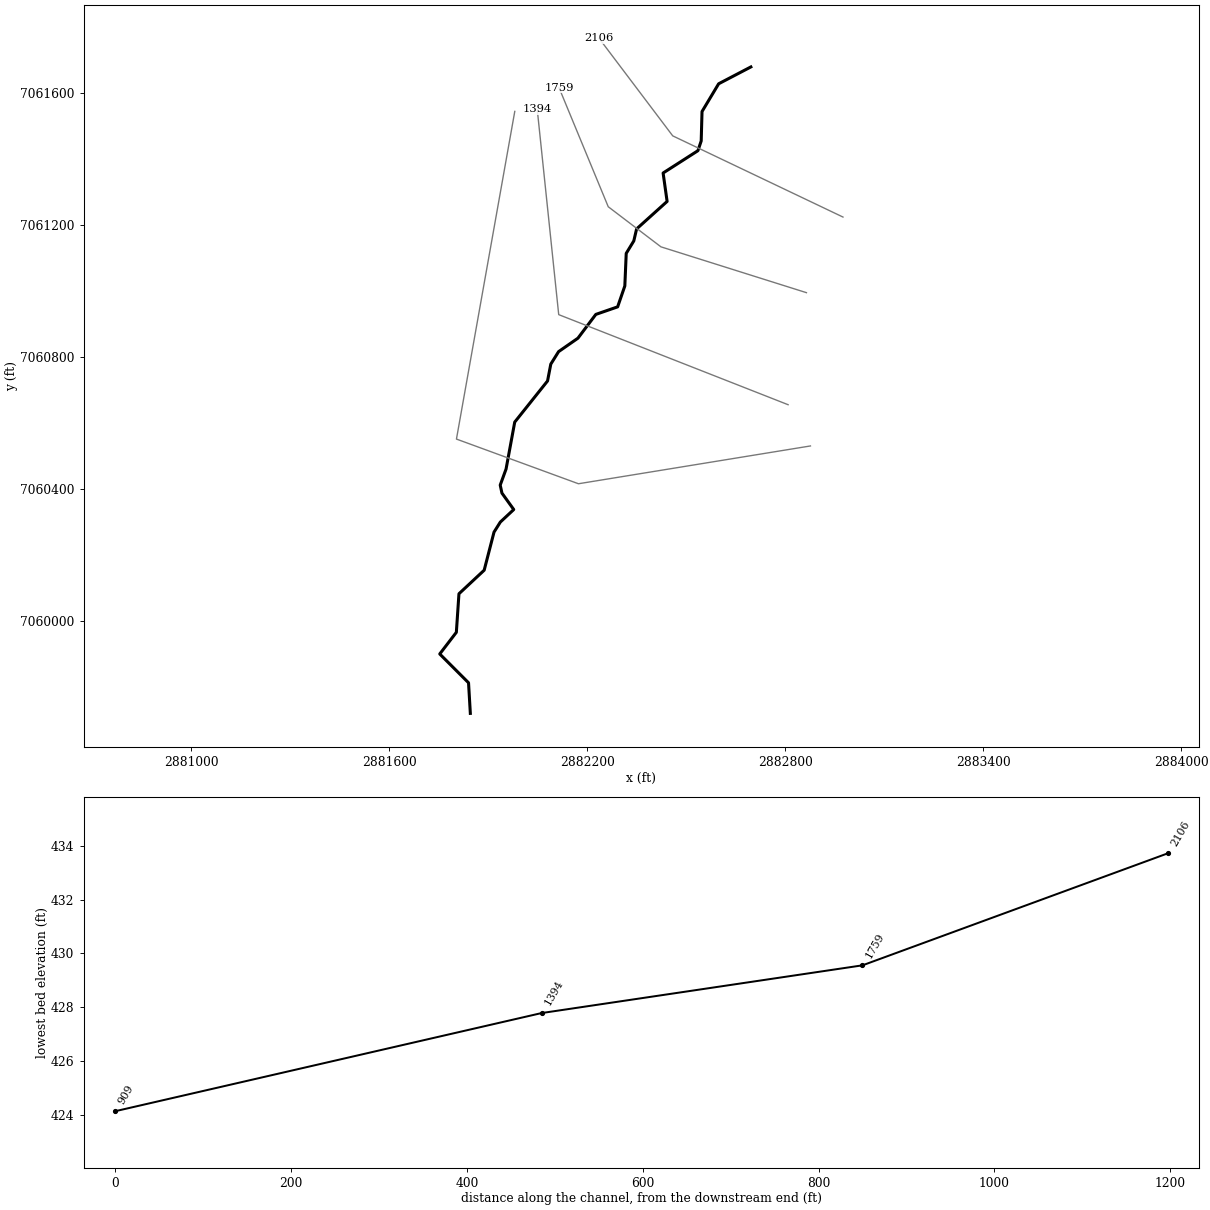
--- UNT 076 in Running Cr Watershed.prj (project) ---

Proj Title=UNT 076 in Running Cr Watershed Base Level Engineering
Current Plan=p01
Default Exp/Contr=0.3,0.1
English Units
Geom File=g01
Flow File=f01
Plan File=p01
BEGIN DESCRIPTION:
UNT 076 in Running Cr Watershed
END DESCRIPTION:

--- UNT 076 in Running Cr Watershed.p01 (plan) ---

Plan Title=Multiple Run
Short Identifier=Multiple
Geom File=g01
Flow File=f01
Subcritical Flow
K Sum by GR= 0
Std Step Tol= 0.01
Critical Tol= 0.01
Num of Std Step Trials= 20
Max Error Tol= 0.3
Flow Tol Ratio= 0.001
Split Flow NTrial= 30
Split Flow Tol= 0.02
Split Flow Ratio= 0.02
Log Output Level= 0
Friction Slope Method= 1
Unsteady Friction Slope Method= 2
Unsteady Bridges Friction Slope Method= 1
Parabolic Critical Depth
Global Vel Dist=  1 , 1 , 1
Global Log Level= 0
CheckData=True
Encroach Param= -1, 0, 0, 0
BEGIN DESCRIPTION:
Multiple Run
END DESCRIPTION:

--- UNT 076 in Running Cr Watershed.f01 (steady flow) ---

Flow Title=Multiple
Number of Profiles=7
Profile Names=10-year,25-year,50-year,1pct_min,100-year,1pct_plu,500-year
River Rch & RM= UNT 076 in Runni,Reach-1,2106
     472     616     731     431     860    1715    1184
Boundary for River Rch & Prof#=UNT 076 in Runni,Reach-1,1
Up Type=0
Dn Type=3
Dn Slope=0.005
Boundary for River Rch & Prof#=UNT 076 in Runni,Reach-1,2
Up Type=0
Dn Type=3
Dn Slope=0.005
Boundary for River Rch & Prof#=UNT 076 in Runni,Reach-1,3
Up Type=0
Dn Type=3
Dn Slope=0.005
Boundary for River Rch & Prof#=UNT 076 in Runni,Reach-1,4
Up Type=0
Dn Type=3
Dn Slope=0.005
Boundary for River Rch & Prof#=UNT 076 in Runni,Reach-1,5
Up Type=0
Dn Type=3
Dn Slope=0.005
Boundary for River Rch & Prof#=UNT 076 in Runni,Reach-1,6
Up Type=0
Dn Type=3
Dn Slope=0.005
Boundary for River Rch & Prof#=UNT 076 in Runni,Reach-1,7
Up Type=0
Dn Type=3
Dn Slope=0.005

--- UNT 076 in Running Cr Watershed.g01 (geometry) ---

Geom Title=Existing Conditions

River Reach=UNT 076 in Runni,Reach-1
Reach XY= 30
      2882695.85      7061680.00      2882598.21      7061628.95
      2882547.81      7061544.81      2882545.30      7061455.65
      2882535.37      7061426.13      2882429.87      7061358.49
      2882441.98      7061272.34      2882349.51      7061189.02
      2882341.03      7061152.67      2882318.06      7061114.91
      2882313.82      7061016.13      2882292.02      7060952.83
      2882225.90      7060929.92      2882171.69      7060857.85
      2882113.05      7060817.10      2882089.42      7060779.20
      2882079.59      7060728.21      2881980.12      7060603.54
      2881953.87      7060461.27      2881936.16      7060412.62
      2881941.36      7060388.32      2881977.17      7060338.50
      2881936.53      7060300.60      2881917.35      7060270.07
      2881887.55      7060154.62      2881811.07      7060083.22
      2881803.20      7059966.38      2881752.86      7059900.76
      2881840.13      7059813.45      2881845.59      7059720.71

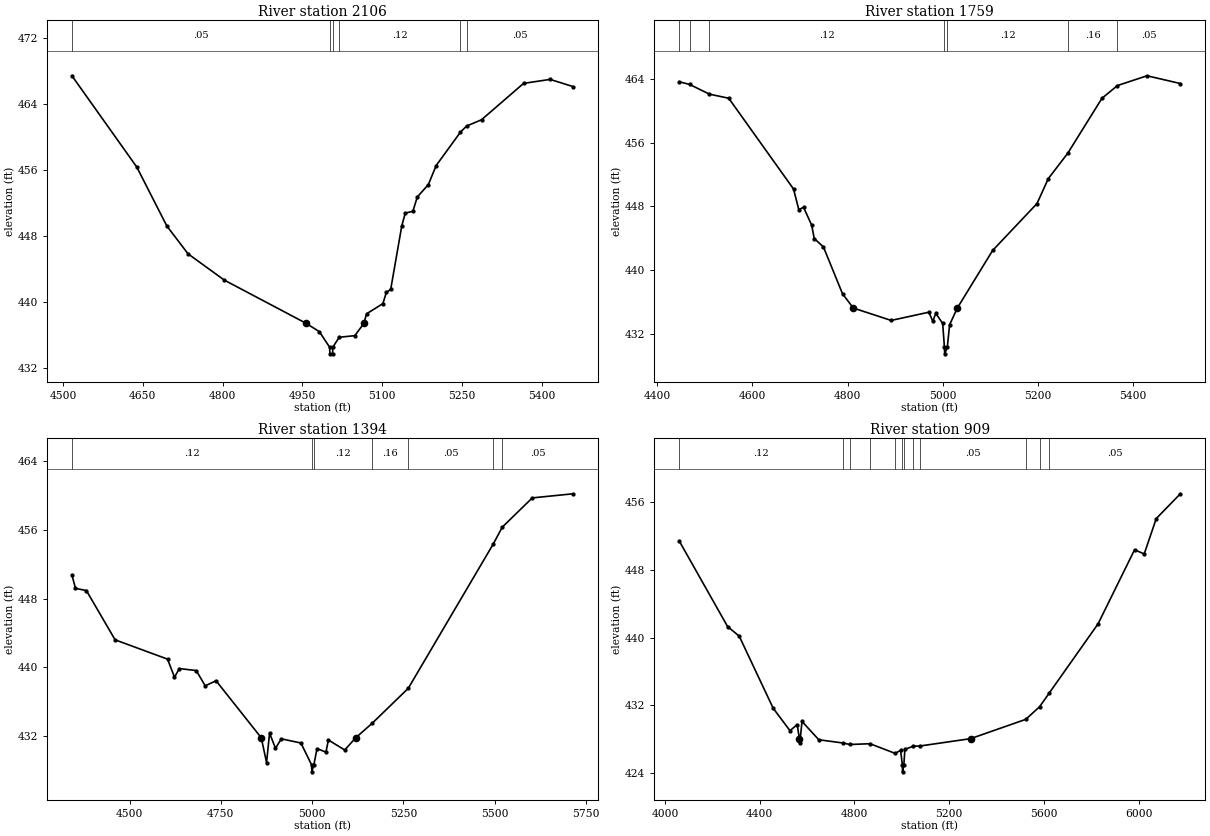
Type RM Length L Ch R = 1,2106,347,347,347
BEGIN DESCRIPTION:
UNT 076 in Running Cr Watershed 3.0
END DESCRIPTION:
XS GIS Cut Line= 3
      2882975.02      7061224.99      2882458.98      7061471.11
      2882235.78      7061766.67
#Sta/Elev= 30
  4516.6  467.39  4638.5  456.34  4695.1  449.19  4735.0  445.82  4803.1  442.64
  4957.1  437.40  4981.9  436.39  5001.1  434.51  5001.6  433.71  5006.6  433.71
  5007.1  434.51  5019.1  435.72  5048.4  435.91  5065.5  437.40  5070.6  438.56
  5101.3  439.80  5107.6  441.14  5115.9  441.52  5136.7  449.20  5143.3  450.76
  5157.6  450.98  5165.9  452.71  5186.7  454.21  5201.3  456.51  5247.0  460.56
  5258.5  461.30  5286.6  462.06  5365.7  466.47  5415.6  466.95  5458.7  466.08
#Mann=6,-1,0
  4516.6    0.05       0  5001.1    0.03       0  5007.1    0.05       0
  5019.1    0.12       0  5247.0    0.16       0  5258.5    0.05       0
Bank Sta=4957.1,5065.5
Exp/Cntr=0.3,0.1

Type RM Length L Ch R = 1,1759,365,365,365
BEGIN DESCRIPTION:
Mapping XS 553f8624
END DESCRIPTION:
XS GIS Cut Line= 4
      2882864.28      7060995.83      2882423.29      7061134.72
      2882263.56      7061256.25      2882114.26      7061617.35
#Sta/Elev= 30
  4446.1  463.60  4467.8  463.27  4509.7  462.05  4550.2  461.54  4686.5  450.18
  4697.6  447.59  4707.5  447.90  4724.7  445.65  4730.0  443.99  4749.4  442.93
  4789.5  437.07  4812.2  435.29  4891.8  433.74  4971.1  434.77  4979.3  433.64
  4985.6  434.63  5000.1  433.36  5003.8  430.36  5004.3  429.56  5009.8  430.36
  5014.7  433.20  5030.9  435.29  5105.1  442.49  5198.4  448.36  5222.3  451.49
  5262.9  454.64  5335.0  461.53  5367.7  463.13  5429.8  464.35  5499.9  463.38
#Mann=7,-1,0
  4446.1    0.12       0  4467.8    0.16       0  4509.7    0.12       0
  5003.8    0.07       0  5009.8    0.12       0  5262.9    0.16       0
  5367.7    0.05       0
Bank Sta=4812.2,5030.9
Exp/Cntr=0.3,0.1

Type RM Length L Ch R = 1,1394,485,485,485
BEGIN DESCRIPTION:
UNT 076 in Running Cr Watershed 2.0
END DESCRIPTION:
XS GIS Cut Line= 3
      2882808.74      7060656.23      2882113.45      7060929.25
      2882048.39      7061551.08
#Sta/Elev= 30
  4342.3  450.76  4352.1  449.18  4381.9  448.93  4460.6  443.18  4604.2  440.93
  4623.2  438.82  4636.4  439.83  4682.8  439.60  4707.3  437.82  4737.0  438.41
  4860.8  431.76  4875.3  428.87  4883.5  432.30  4899.7  430.54  4915.7  431.64
  4969.4  431.15  4998.7  428.59  4999.2  427.79  5004.7  428.59  5013.5  430.50
  5037.9  430.09  5044.6  431.50  5089.3  430.34  5119.4  431.76  5165.2  433.48
  5263.3  437.53  5495.7  454.33  5520.7  456.32  5602.9  459.73  5714.5  460.21
#Mann=7,-1,0
  4342.3    0.12       0  4998.7    0.07       0  5004.7    0.12       0
  5165.2    0.16       0  5263.3    0.05       0  5495.7    0.16       0
  5520.7    0.05       0
Bank Sta=4860.8,5119.4
Exp/Cntr=0.3,0.1

Type RM Length L Ch R = 1,909,0,0,0
BEGIN DESCRIPTION:
UNT 076 in Running Cr Watershed 1.0
END DESCRIPTION:
XS GIS Cut Line= 4
      2882876.42      7060531.25      2882173.29      7060416.67
      2881803.49      7060552.08      2881980.29      7061545.25
#Sta/Elev= 30
  4060.5  451.42  4264.6  441.31  4313.6  440.18  4457.1  431.66  4528.0  429.01
  4558.4  429.73  4567.6  428.07  4569.6  427.61  4578.7  430.10  4649.6  427.94
  4753.3  427.55  4780.3  427.38  4865.7  427.47  4972.1  426.33  4994.7  426.69
  5002.4  424.95  5002.9  424.15  5008.4  424.95  5013.0  426.81  5047.7  427.17
  5078.5  427.21  5290.4  428.07  5523.1  430.35  5581.5  431.84  5621.2  433.42
  5828.2  441.63  5982.3  450.38  6022.9  449.88  6073.7  454.06  6175.5  456.99
#Mann=12,-1,0
  4060.5    0.12       0  4753.3    0.16       0  4780.3    0.12       0
  4865.7    0.16       0  4972.1    0.12       0  5002.4    0.07       0
  5008.4    0.12       0  5047.7    0.16       0  5078.5    0.05       0
  5523.1    0.16       0  5581.5    0.12       0  5621.2    0.05       0
Bank Sta=4567.6,5290.4
Exp/Cntr=0.3,0.1

Chan Stop Cuts=-1