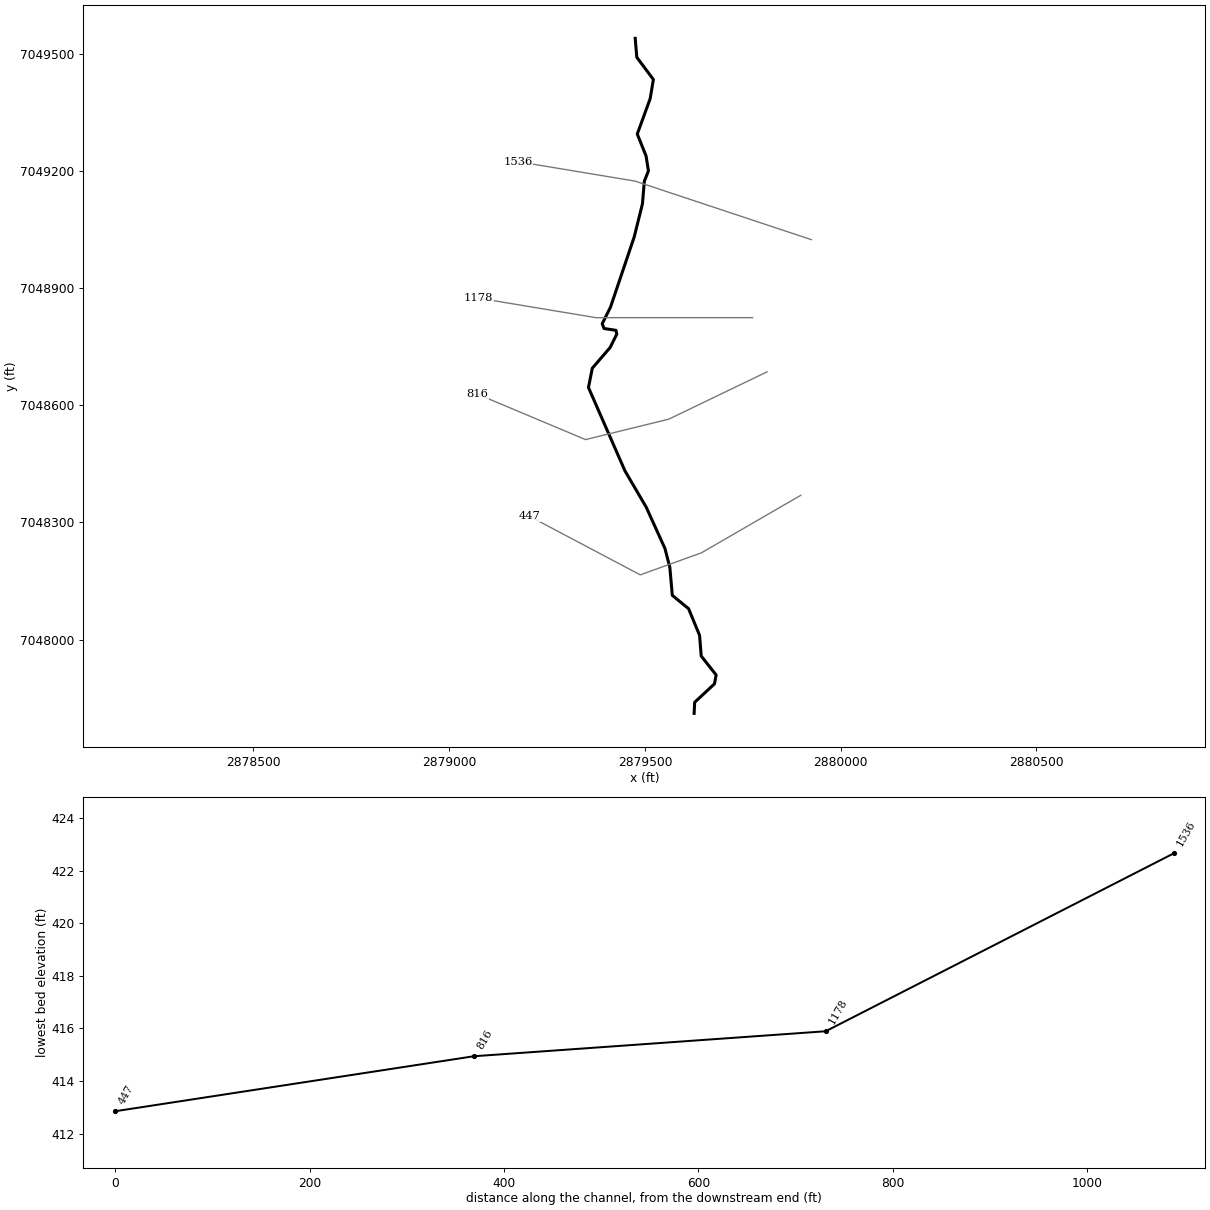
--- UNT 077 in Running Cr Watershed.prj (project) ---

Proj Title=UNT 077 in Running Cr Watershed Base Level Engineering
Current Plan=p01
Default Exp/Contr=0.3,0.1
English Units
Geom File=g01
Flow File=f01
Plan File=p01
BEGIN DESCRIPTION:
UNT 077 in Running Cr Watershed
END DESCRIPTION:

--- UNT 077 in Running Cr Watershed.p01 (plan) ---

Plan Title=Multiple Run
Short Identifier=Multiple
Geom File=g01
Flow File=f01
Subcritical Flow
K Sum by GR= 0
Std Step Tol= 0.01
Critical Tol= 0.01
Num of Std Step Trials= 20
Max Error Tol= 0.3
Flow Tol Ratio= 0.001
Split Flow NTrial= 30
Split Flow Tol= 0.02
Split Flow Ratio= 0.02
Log Output Level= 0
Friction Slope Method= 1
Unsteady Friction Slope Method= 2
Unsteady Bridges Friction Slope Method= 1
Parabolic Critical Depth
Global Vel Dist=  1 , 1 , 1
Global Log Level= 0
CheckData=True
Encroach Param= -1, 0, 0, 0
BEGIN DESCRIPTION:
Multiple Run
END DESCRIPTION:

--- UNT 077 in Running Cr Watershed.f01 (steady flow) ---

Flow Title=Multiple
Number of Profiles=7
Profile Names=10-year,25-year,50-year,1pct_min,100-year,1pct_plu,500-year
River Rch & RM= UNT 077 in Runni,Reach-1,1536
     333     430     506     297     592    1180     810
Boundary for River Rch & Prof#=UNT 077 in Runni,Reach-1,1
Up Type=0
Dn Type=3
Dn Slope=0.005
Boundary for River Rch & Prof#=UNT 077 in Runni,Reach-1,2
Up Type=0
Dn Type=3
Dn Slope=0.005
Boundary for River Rch & Prof#=UNT 077 in Runni,Reach-1,3
Up Type=0
Dn Type=3
Dn Slope=0.005
Boundary for River Rch & Prof#=UNT 077 in Runni,Reach-1,4
Up Type=0
Dn Type=3
Dn Slope=0.005
Boundary for River Rch & Prof#=UNT 077 in Runni,Reach-1,5
Up Type=0
Dn Type=3
Dn Slope=0.005
Boundary for River Rch & Prof#=UNT 077 in Runni,Reach-1,6
Up Type=0
Dn Type=3
Dn Slope=0.005
Boundary for River Rch & Prof#=UNT 077 in Runni,Reach-1,7
Up Type=0
Dn Type=3
Dn Slope=0.005

--- UNT 077 in Running Cr Watershed.g01 (geometry) ---

Geom Title=Existing Conditions

River Reach=UNT 077 in Runni,Reach-1
Reach XY= 30
      2879475.08      7049541.00      2879479.19      7049492.44
      2879521.51      7049435.52      2879513.31      7049386.33
      2879480.36      7049295.69      2879502.84      7049239.49
      2879508.87      7049201.17      2879498.41      7049174.65
      2879493.57      7049116.59      2879472.54      7049031.97
      2879411.93      7048851.77      2879390.88      7048809.59
      2879395.38      7048797.29      2879425.89      7048792.53
      2879428.09      7048782.87      2879411.04      7048748.51
      2879365.56      7048695.60      2879355.66      7048646.06
      2879449.00      7048432.12      2879503.01      7048339.64
      2879551.03      7048233.53      2879563.59      7048184.82
      2879569.86      7048113.27      2879611.55      7048078.92
      2879639.55      7048010.65      2879643.74      7047957.61
      2879681.81      7047909.19      2879677.58      7047886.32
      2879627.02      7047839.14      2879625.59      7047810.71

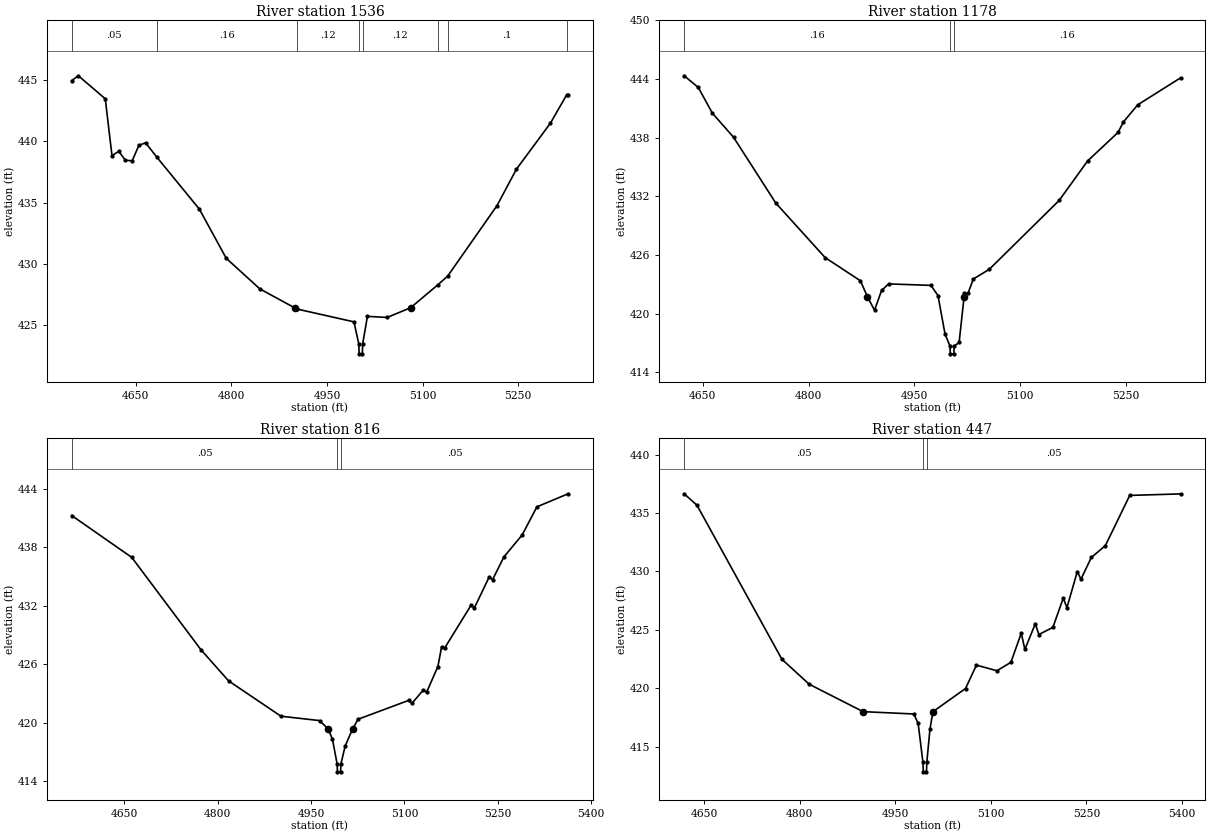
Type RM Length L Ch R = 1,1536,358,358,358
BEGIN DESCRIPTION:
UNT 077 in Running Cr Watershed 3.0
END DESCRIPTION:
XS GIS Cut Line= 3
      2879924.99      7049025.00      2879475.00      7049175.00
      2879174.97      7049225.00
#Sta/Elev= 30
  4549.7  444.96  4560.2  445.35  4602.4  443.47  4612.9  438.83  4623.5  439.18
  4634.0  438.45  4644.6  438.41  4655.1  439.67  4665.6  439.88  4683.0  438.72
  4750.0  434.46  4792.1  430.45  4844.8  427.95  4899.3  426.41  4902.9  426.31
  4992.4  425.26  5000.0  423.45  5000.5  422.65  5005.5  422.65  5006.0  423.45
  5013.5  425.71  5044.3  425.62  5081.1  426.41  5124.0  428.29  5139.4  429.00
  5216.7  434.75  5247.1  437.72  5300.3  441.47  5325.7  443.77  5328.2  443.77
#Mann=8,-1,0
  4549.7    0.05       0  4683.0    0.16       0  4902.9    0.12       0
  5000.0    0.07       0  5006.0    0.12       0  5124.0    0.16       0
  5139.4     0.1       0  5325.7    0.16       0
Bank Sta=4899.3,5081.1
Exp/Cntr=0.3,0.1

Type RM Length L Ch R = 1,1178,362,362,362
BEGIN DESCRIPTION:
UNT 077 in Running Cr Watershed 2.0
END DESCRIPTION:
XS GIS Cut Line= 3
      2879774.97      7048825.00      2879375.00      7048825.00
      2879075.01      7048875.00
#Sta/Elev= 30
  4623.6  444.32  4643.6  443.13  4663.6  440.50  4693.6  438.04  4753.6  431.30
  4823.6  425.73  4873.6  423.36  4883.6  421.72  4893.6  420.35  4903.6  422.37
  4913.6  423.04  4973.6  422.89  4983.6  421.85  4993.6  417.91  5000.6  416.69
  5001.1  415.89  5006.1  415.89  5006.6  416.69  5013.6  417.05  5020.6  421.72
  5021.1  422.06  5026.1  422.06  5033.7  423.54  5056.5  424.54  5155.4  431.57
  5195.9  435.62  5239.0  438.53  5246.6  439.60  5266.9  441.35  5327.7  444.11
#Mann=3,-1,0
  4623.6    0.16       0  5000.6    0.07       0  5006.6    0.16       0
Bank Sta=4883.6,5020.6
Exp/Cntr=0.3,0.1

Type RM Length L Ch R = 1,816,369,369,369
BEGIN DESCRIPTION:
Mapping XS bf0a01a9
END DESCRIPTION:
XS GIS Cut Line= 4
      2879811.85      7048686.12      2879560.83      7048564.82
      2879348.29      7048512.50      2879072.27      7048628.81
#Sta/Elev= 30
  4565.6  441.25  4662.1  436.95  4773.1  427.48  4817.5  424.28  4901.6  420.65
  4963.7  420.20  4977.7  419.32  4984.3  418.30  4991.9  415.74  4992.4  414.94
  4997.4  414.94  4997.9  415.74  5004.9  417.61  5016.6  419.32  5025.5  420.34
  5106.6  422.27  5112.0  421.97  5130.3  423.34  5135.7  423.13  5153.7  425.75
  5159.5  427.73  5164.9  427.68  5206.9  432.04  5212.3  431.77  5236.1  434.95
  5241.5  434.67  5259.8  437.01  5289.0  439.25  5312.7  442.14  5362.8  443.48
#Mann=3,-1,0
  4565.6    0.05       0  4991.9    0.03       0  4997.9    0.05       0
Bank Sta=4977.7,5016.6
Exp/Cntr=0.3,0.1

Type RM Length L Ch R = 1,447,0,0,0
BEGIN DESCRIPTION:
UNT 077 in Running Cr Watershed 1.0
END DESCRIPTION:
XS GIS Cut Line= 4
      2879898.07      7048369.72      2879644.21      7048222.18
      2879487.96      7048165.76      2879205.88      7048315.47
#Sta/Elev= 30
  4618.6  436.64  4638.7  435.66  4772.0  422.48  4815.0  420.34  4899.4  418.00
  4979.0  417.80  4985.8  416.99  4993.4  413.65  4993.9  412.85  4998.9  412.85
  4999.4  413.65  5004.4  416.53  5009.1  418.00  5060.2  419.98  5077.3  421.98
  5109.4  421.50  5131.4  422.22  5147.7  424.72  5153.3  423.32  5169.7  425.52
  5175.3  424.60  5197.3  425.21  5213.6  427.72  5219.3  426.89  5235.6  429.99
  5241.3  429.33  5257.6  431.19  5279.6  432.20  5317.9  436.50  5397.7  436.63
#Mann=3,-1,0
  4618.6    0.05       0  4993.4    0.03       0  4999.4    0.05       0
Bank Sta=4899.4,5009.1
Exp/Cntr=0.3,0.1

Chan Stop Cuts=-1