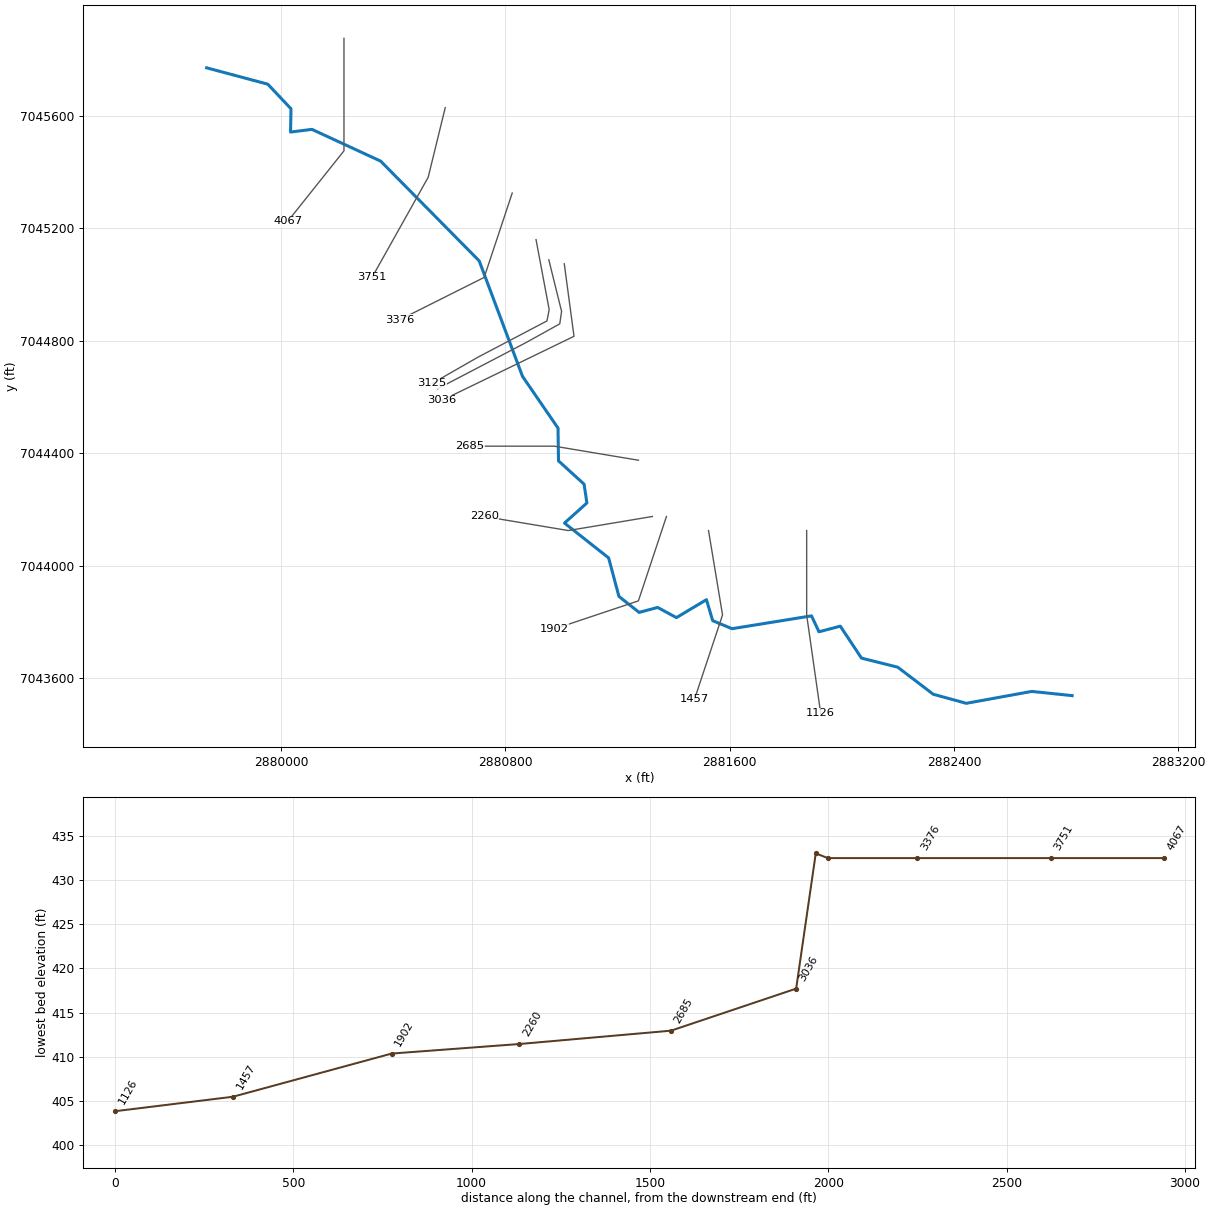
--- UNT 078 in Running Cr Watershed.prj (project) ---

Proj Title=UNT 078 in Running Cr Watershed Base Level Engineering
Current Plan=p01
Default Exp/Contr=0.3,0.1
English Units
Geom File=g01
Flow File=f01
Plan File=p01
BEGIN DESCRIPTION:
UNT 078 in Running Cr Watershed
END DESCRIPTION:

--- UNT 078 in Running Cr Watershed.p01 (plan) ---

Plan Title=Multiple Run
Short Identifier=Multiple
Geom File=g01
Flow File=f01
Subcritical Flow
K Sum by GR= 0
Std Step Tol= 0.01
Critical Tol= 0.01
Num of Std Step Trials= 20
Max Error Tol= 0.3
Flow Tol Ratio= 0.001
Split Flow NTrial= 30
Split Flow Tol= 0.02
Split Flow Ratio= 0.02
Log Output Level= 0
Friction Slope Method= 1
Unsteady Friction Slope Method= 2
Unsteady Bridges Friction Slope Method= 1
Parabolic Critical Depth
Global Vel Dist=  1 , 1 , 1
Global Log Level= 0
CheckData=True
Encroach Param= -1, 0, 0, 0
BEGIN DESCRIPTION:
Multiple Run
END DESCRIPTION:

--- UNT 078 in Running Cr Watershed.f01 (steady flow) ---

Flow Title=Multiple
Number of Profiles=7
Profile Names=10-year,25-year,50-year,1pct_min,100-year,1pct_plu,500-year
River Rch & RM= UNT 078 in Runni,Reach-1,4067
     248     313     364     211     421     839     561
Boundary for River Rch & Prof#=UNT 078 in Runni,Reach-1,1
Up Type=0
Dn Type=3
Dn Slope=0.005
Boundary for River Rch & Prof#=UNT 078 in Runni,Reach-1,2
Up Type=0
Dn Type=3
Dn Slope=0.005
Boundary for River Rch & Prof#=UNT 078 in Runni,Reach-1,3
Up Type=0
Dn Type=3
Dn Slope=0.005
Boundary for River Rch & Prof#=UNT 078 in Runni,Reach-1,4
Up Type=0
Dn Type=3
Dn Slope=0.005
Boundary for River Rch & Prof#=UNT 078 in Runni,Reach-1,5
Up Type=0
Dn Type=3
Dn Slope=0.005
Boundary for River Rch & Prof#=UNT 078 in Runni,Reach-1,6
Up Type=0
Dn Type=3
Dn Slope=0.005
Boundary for River Rch & Prof#=UNT 078 in Runni,Reach-1,7
Up Type=0
Dn Type=3
Dn Slope=0.005

--- UNT 078 in Running Cr Watershed.g01 (geometry) ---

Geom Title=Existing Conditions

River Reach=UNT 078 in Runni,Reach-1
Reach XY= 30
      2879735.36      7045770.15      2879953.38      7045711.97
      2880036.09      7045624.49      2880034.50      7045541.79
      2880110.84      7045551.33      2880355.78      7045438.40
      2880707.29      7045083.72      2880861.57      7044673.36
      2880988.27      7044489.29      2880990.03      7044372.74
      2881081.21      7044289.93      2881091.31      7044223.03
      2881011.42      7044151.60      2881168.76      7044027.72
      2881205.59      7043890.71      2881277.49      7043834.01
      2881343.58      7043851.60      2881410.62      7043815.47
      2881517.60      7043879.18      2881539.94      7043804.53
      2881608.88      7043776.01      2881892.26      7043821.65
      2881918.88      7043765.07      2881994.96      7043785.04
      2882070.55      7043671.41      2882199.88      7043639.07
      2882326.35      7043543.03      2882444.26      7043510.70
      2882677.71      7043553.02      2882821.59      7043538.11

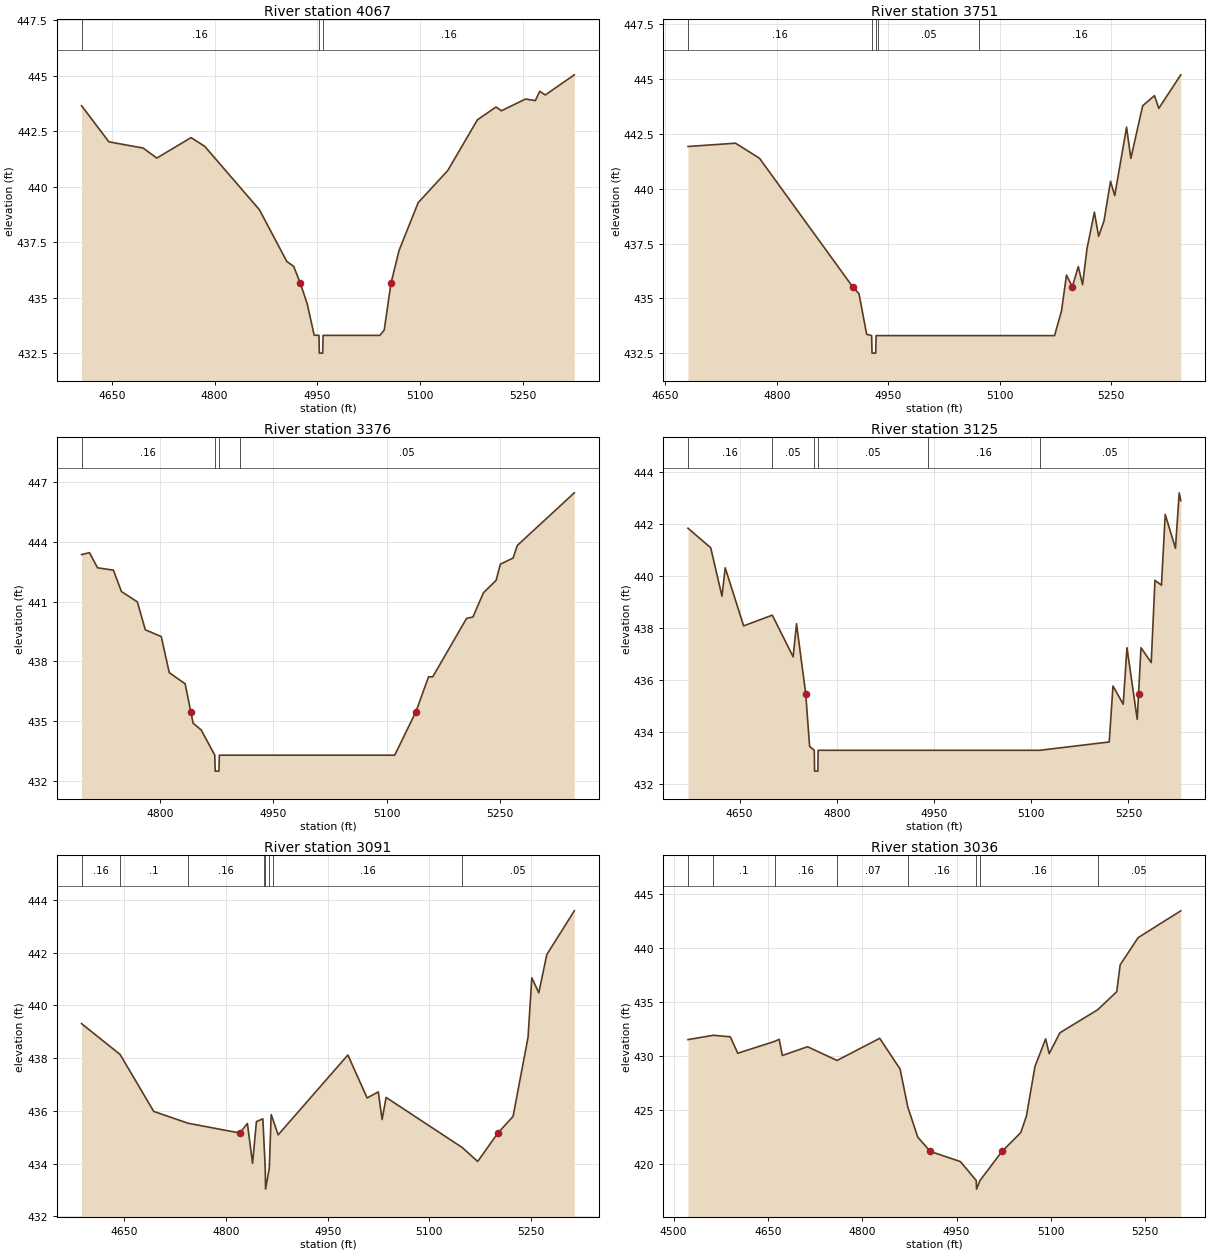
Type RM Length L Ch R = 1,4067,316,316,316
BEGIN DESCRIPTION:
UNT 078 in Running Cr Watershed 9.0
END DESCRIPTION:
XS GIS Cut Line= 3
      2880225.00      7045874.99      2880225.00      7045475.00
      2880024.97      7045224.96
#Sta/Elev= 30
  4605.5  443.65  4645.5  442.02  4695.5  441.74  4715.5  441.29  4765.5  442.21
  4785.5  441.82  4865.5  438.96  4905.5  436.63  4915.5  436.41  4925.4  435.64
  4935.5  434.70  4945.5  433.31  4952.5  433.30  4953.0  432.50  4958.0  432.50
  4958.5  433.30  5041.5  433.30  5047.9  433.54  5057.7  435.64  5069.5  437.12
  5097.5  439.28  5140.8  440.73  5184.0  443.01  5211.2  443.59  5219.2  443.42
  5254.4  443.95  5268.8  443.88  5275.2  444.30  5283.2  444.13  5325.7  445.04
#Mann=3,-1,0
  4605.5    0.16       0  4952.5    0.07       0  4958.5    0.16       0
Bank Sta=4925.4,5057.7
Exp/Cntr=0.3,0.1

Type RM Length L Ch R = 1,3751,375,375,375
BEGIN DESCRIPTION:
UNT 078 in Running Cr Watershed 8.0
END DESCRIPTION:
XS GIS Cut Line= 3
      2880586.13      7045628.57      2880525.36      7045381.14
      2880325.01      7045025.01
#Sta/Elev= 30
  4680.6  441.93  4744.6  442.08  4776.9  441.39  4902.2  435.53  4910.8  435.21
  4921.1  433.36  4927.8  433.30  4928.3  432.50  4933.3  432.50  4933.8  433.30
  4936.7  433.30  5072.1  433.30  5174.1  433.30  5183.4  434.42  5190.1  436.06
  5198.0  435.53  5206.0  436.45  5211.8  435.63  5217.8  437.28  5227.7  438.93
  5233.4  437.83  5240.7  438.54  5249.4  440.34  5255.1  439.69  5271.0  442.81
  5276.8  441.39  5292.7  443.79  5308.6  444.25  5314.4  443.67  5344.0  445.20
#Mann=5,-1,0
  4680.6    0.16       0  4927.8   0.033       0  4933.8    0.16       0
  4936.7    0.05       0  5072.1    0.16       0
Bank Sta=4902.2,5198
Exp/Cntr=0.3,0.1

Type RM Length L Ch R = 1,3376,251,251,251
BEGIN DESCRIPTION:
UNT 078 in Running Cr Watershed 7.0
END DESCRIPTION:
XS GIS Cut Line= 3
      2880825.00      7045325.01      2880725.00      7045025.00
      2880425.04      7044875.02
#Sta/Elev= 30
  4696.4  443.36  4706.9  443.46  4717.5  442.70  4738.6  442.58  4749.1  441.51
  4770.2  440.99  4780.7  439.59  4801.8  439.25  4812.4  437.44  4833.4  436.88
  4840.8  435.49  4844.0  434.90  4854.5  434.57  4872.6  433.30  4873.1  432.50
  4878.1  432.50  4878.6  433.30  4906.3  433.30  5110.5  433.30  5138.7  435.49
  5155.2  437.23  5160.8  437.23  5205.5  440.16  5213.9  440.23  5227.9  441.45
  5244.6  442.07  5250.2  442.88  5267.0  443.19  5272.6  443.82  5348.0  446.46
#Mann=4,-1,0
  4696.4    0.16       0  4872.6   0.033       0  4878.6    0.16       0
  4906.3    0.05       0
Bank Sta=4840.8,5138.7
Exp/Cntr=0.3,0.1

Type RM Length L Ch R = 1,3125,34,34,34
BEGIN DESCRIPTION:
Mapping XS 8060e54e
END DESCRIPTION:
XS GIS Cut Line= 5
      2880909.91      7045159.35      2880956.78      7044910.66
      2880948.97      7044870.29      2880702.88      7044741.39
      2880539.39      7044647.96
#Sta/Elev= 30
  4570.4  441.83  4605.4  441.08  4622.8  439.22  4627.8  440.31  4656.2  438.08
  4700.4  438.49  4732.6  436.89  4737.8  438.16  4752.0  435.48  4758.0  433.45
  4765.2  433.30  4765.7  432.50  4770.7  432.50  4771.2  433.30  4941.3  433.30
  5112.9  433.30  5220.3  433.62  5226.1  435.77  5241.9  435.07  5247.7  437.24
  5263.5  434.49  5265.6  435.48  5269.3  437.24  5285.1  436.67  5290.9  439.83
  5300.9  439.64  5306.7  442.36  5322.5  441.06  5328.3  443.19  5330.7  442.89
#Mann=6,-1,0
  4570.4    0.16       0  4700.4    0.05       0  4765.2    0.07       0
  4771.2    0.05       0  4941.3    0.16       0  5112.9    0.05       0
Bank Sta=4752,5265.6
Exp/Cntr=0.3,0.1

Type RM Length L Ch R = 1,3091,55,55,55
BEGIN DESCRIPTION:
Mapping XS 891969e9
END DESCRIPTION:
XS GIS Cut Line= 6
      2880955.49      7045087.70      2880985.43      7044966.65
      2881001.05      7044904.15      2880994.54      7044859.87
      2880872.15      7044792.17      2880558.55      7044628.89
#Sta/Elev= 30
  4586.8  439.31  4643.7  438.14  4693.3  435.98  4744.0  435.53  4820.3  435.16
  4831.6  435.52  4839.2  434.01  4844.9  435.59  4854.4  435.70  4856.3  434.68
  4857.9  433.83  4858.4  433.03  4863.9  433.83  4866.7  435.86  4869.3  435.67
  4877.0  435.09  4979.9  438.12  5008.3  436.49  5024.8  436.72  5030.4  435.67
  5036.3  436.51  5148.6  434.61  5171.5  434.08  5201.3  435.16  5223.7  435.79
  5245.8  438.79  5251.4  441.05  5261.7  440.48  5273.5  441.93  5314.1  443.59
#Mann=8,-1,0
  4586.8    0.16       0  4643.7     0.1       0  4744.0    0.16       0
  4856.3    0.05       0  4857.9    0.07       0  4863.9    0.05       0
  4869.3    0.16       0  5148.6    0.05       0
Bank Sta=4820.3,5201.3
Exp/Cntr=0.3,0.1

Type RM Length L Ch R = 1,3036,351,351,351
BEGIN DESCRIPTION:
UNT 078 in Running Cr Watershed 6.0
END DESCRIPTION:
XS GIS Cut Line= 3
      2881010.60      7045073.39      2881045.32      7044815.60
      2880573.93      7044587.72
#Sta/Elev= 30
  4522.9  431.56  4563.1  431.96  4590.1  431.82  4602.0  430.30  4661.5  431.41
  4667.9  431.59  4672.9  430.09  4713.0  430.90  4759.9  429.63  4827.8  431.68
  4860.2  428.83  4872.4  425.33  4888.3  422.53  4908.2  421.21  4956.1  420.27
  4981.3  418.52  4981.8  417.72  4987.3  418.52  5022.2  421.21  5052.1  422.95
  5061.1  424.48  5074.7  429.07  5091.7  431.63  5097.3  430.26  5114.3  432.19
  5174.4  434.32  5204.7  435.99  5210.2  438.48  5238.8  441.00  5306.6  443.48
#Mann=8,-1,0
  4522.9    0.16       0  4563.1     0.1       0  4661.5    0.16       0
  4759.9    0.07       0  4872.4    0.16       0  4981.3    0.07       0
  4987.3    0.16       0  5174.4    0.05       0
Bank Sta=4908.2,5022.2
Exp/Cntr=0.3,0.1

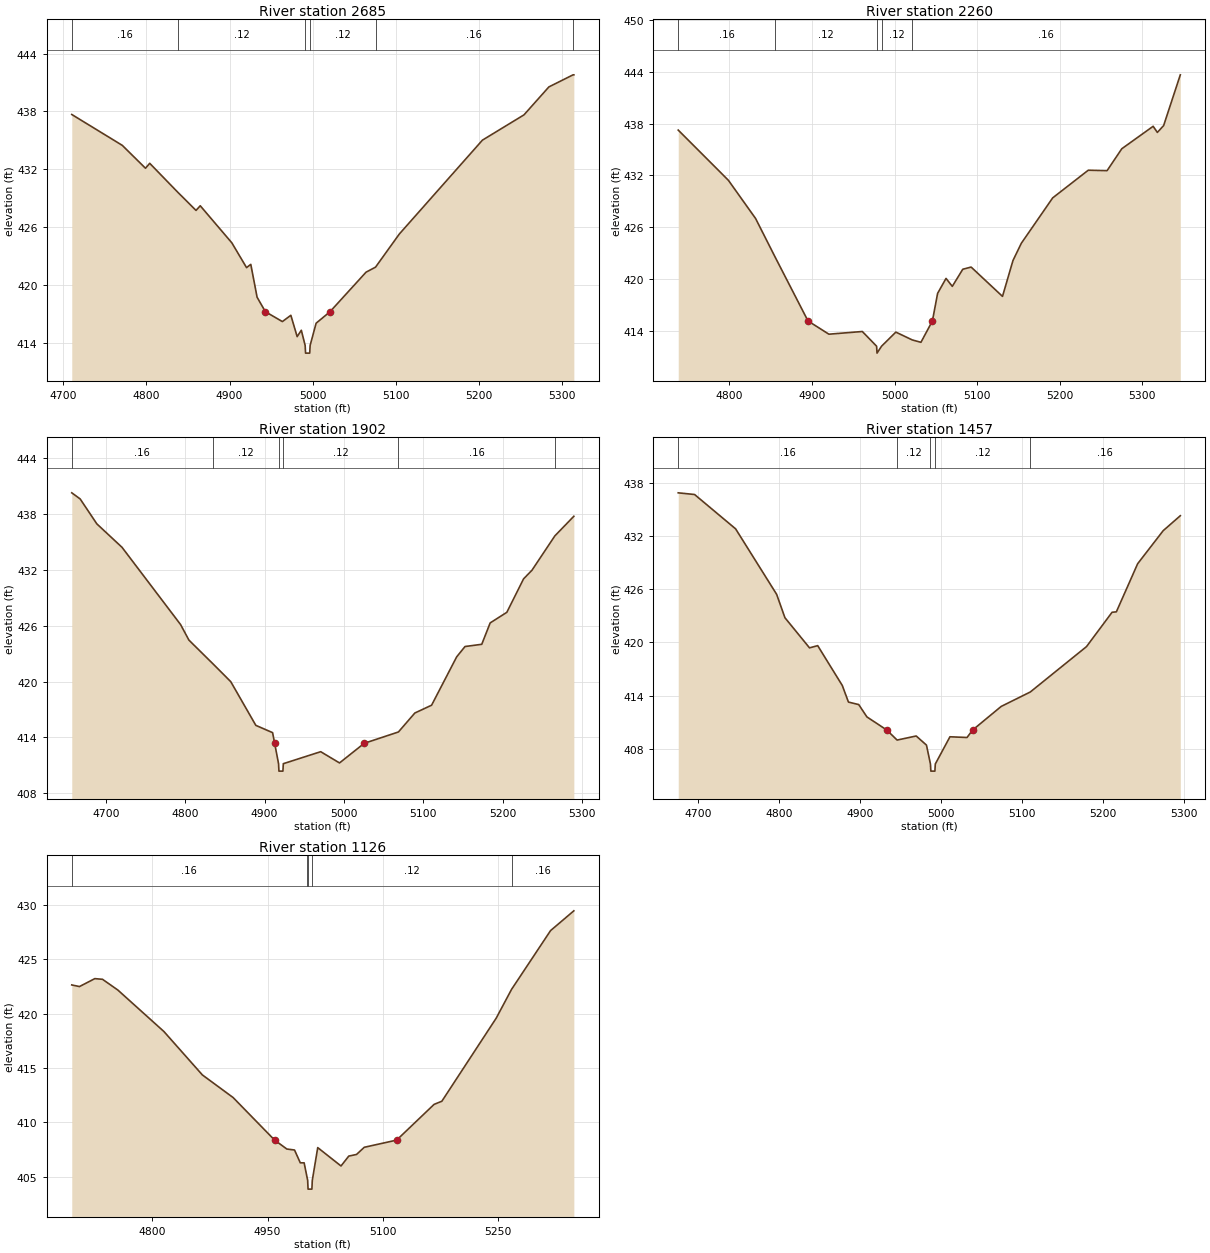
Type RM Length L Ch R = 1,2685,425,425,425
BEGIN DESCRIPTION:
UNT 078 in Running Cr Watershed 5.0
END DESCRIPTION:
XS GIS Cut Line= 3
      2881274.98      7044375.00      2880975.00      7044425.00
      2880675.02      7044425.00
#Sta/Elev= 30
  4710.2  437.69  4771.0  434.49  4798.9  432.12  4804.0  432.63  4837.9  429.62
  4859.7  427.75  4864.8  428.23  4902.8  424.39  4920.5  421.82  4925.6  422.16
  4933.2  418.75  4943.2  417.25  4963.6  416.23  4973.8  416.88  4981.4  414.67
  4986.4  415.33  4991.0  413.76  4991.5  412.96  4996.5  412.96  4997.0  413.76
  5004.2  416.06  5020.9  417.25  5064.3  421.35  5075.7  421.87  5104.3  425.30
  5204.3  435.03  5254.3  437.65  5284.3  440.55  5313.4  441.80  5314.3  441.80
#Mann=6,-1,0
  4710.2    0.16       0  4837.9    0.12       0  4991.0    0.07       0
  4997.0    0.12       0  5075.7    0.16       0  5313.4    0.05       0
Bank Sta=4943.2,5020.9
Exp/Cntr=0.3,0.1

Type RM Length L Ch R = 1,2260,358,358,358
BEGIN DESCRIPTION:
UNT 078 in Running Cr Watershed 4.0
END DESCRIPTION:
XS GIS Cut Line= 3
      2881324.97      7044175.00      2881025.00      7044125.00
      2880725.05      7044174.99
#Sta/Elev= 30
  4738.0  437.24  4798.8  431.43  4831.7  427.02  4855.2  422.59  4895.2  415.17
  4920.5  413.64  4961.0  413.95  4978.3  412.25  4978.8  411.45  4984.3  412.25
  5001.6  413.88  5021.4  412.98  5032.0  412.70  5045.9  415.17  5052.2  418.36
  5062.4  420.09  5070.0  419.17  5082.7  421.15  5092.8  421.40  5130.8  418.01
  5143.5  422.16  5153.6  424.15  5191.6  429.40  5234.7  432.60  5257.5  432.55
  5275.3  435.08  5313.3  437.68  5318.4  436.97  5326.0  437.76  5346.2  443.63
#Mann=5,-1,0
  4738.0    0.16       0  4855.2    0.12       0  4978.3    0.07       0
  4984.3    0.12       0  5021.4    0.16       0
Bank Sta=4895.2,5045.9
Exp/Cntr=0.3,0.1

Type RM Length L Ch R = 1,1902,445,445,445
BEGIN DESCRIPTION:
UNT 078 in Running Cr Watershed 3.0
END DESCRIPTION:
XS GIS Cut Line= 3
      2881375.01      7044175.02      2881275.00      7043875.00
      2880974.98      7043774.99
#Sta/Elev= 30
  4657.2  440.30  4667.8  439.64  4688.8  436.96  4720.5  434.44  4794.3  426.13
  4804.8  424.46  4834.7  421.94  4857.5  419.99  4889.1  415.29  4910.2  414.51
  4912.8  413.36  4917.7  411.17  4918.2  410.37  4923.2  410.37  4923.7  411.17
  4970.8  412.46  4994.5  411.25  5025.6  413.36  5068.7  414.58  5089.4  416.62
  5110.5  417.46  5142.1  422.66  5152.6  423.77  5173.7  424.01  5184.3  426.31
  5205.3  427.45  5226.4  431.05  5237.0  431.98  5265.7  435.66  5289.7  437.78
#Mann=6,-1,0
  4657.2    0.16       0  4834.7    0.12       0  4917.7    0.07       0
  4923.7    0.12       0  5068.7    0.16       0  5265.7    0.05       0
Bank Sta=4912.8,5025.6
Exp/Cntr=0.3,0.1

Type RM Length L Ch R = 1,1457,331,331,331
BEGIN DESCRIPTION:
UNT 078 in Running Cr Watershed 2.0
END DESCRIPTION:
XS GIS Cut Line= 3
      2881525.01      7044124.96      2881575.00      7043825.00
      2881475.01      7043525.03
#Sta/Elev= 30
  4675.2  436.84  4695.4  436.65  4746.1  432.78  4796.8  425.40  4807.0  422.77
  4837.4  419.37  4847.5  419.62  4877.9  415.13  4885.5  413.26  4898.2  412.98
  4908.3  411.59  4932.9  410.11  4945.6  408.98  4969.2  409.44  4981.9  408.41
  4986.8  406.28  4987.3  405.48  4992.3  405.48  4992.8  406.28  5010.9  409.35
  5032.0  409.27  5038.9  410.11  5074.2  412.77  5110.2  414.40  5179.6  419.51
  5211.2  423.38  5216.5  423.43  5242.8  428.85  5274.4  432.58  5295.5  434.26
#Mann=5,-1,0
  4675.2    0.16       0  4945.6    0.12       0  4986.8    0.07       0
  4992.8    0.12       0  5110.2    0.16       0
Bank Sta=4932.9,5038.9
Exp/Cntr=0.3,0.1

Type RM Length L Ch R = 1,1126,0,0,0
BEGIN DESCRIPTION:
UNT 078 in Running Cr Watershed 1.0
END DESCRIPTION:
XS GIS Cut Line= 3
      2881875.00      7044125.02      2881875.00      7043825.00
      2881925.00      7043474.97
#Sta/Elev= 30
  4695.2  422.63  4705.2  422.48  4725.2  423.21  4735.2  423.15  4755.2  422.16
  4815.2  418.34  4865.2  414.35  4905.2  412.27  4959.3  408.35  4975.2  407.53
  4985.2  407.44  4992.7  406.26  4997.7  406.26  5000.8  405.17  5002.3  404.64
  5002.8  403.84  5007.8  403.84  5008.3  404.64  5015.4  407.66  5045.7  405.97
  5055.8  406.88  5065.9  407.03  5076.0  407.69  5118.1  408.35  5166.9  411.64
  5177.0  411.93  5247.8  419.58  5267.7  422.22  5318.5  427.63  5348.8  429.45
#Mann=5,-1,0
  4695.2    0.16       0  5000.8    0.12       0  5002.3    0.07       0
  5008.3    0.12       0  5267.7    0.16       0
Bank Sta=4959.3,5118.1
Exp/Cntr=0.3,0.1

Chan Stop Cuts=-1