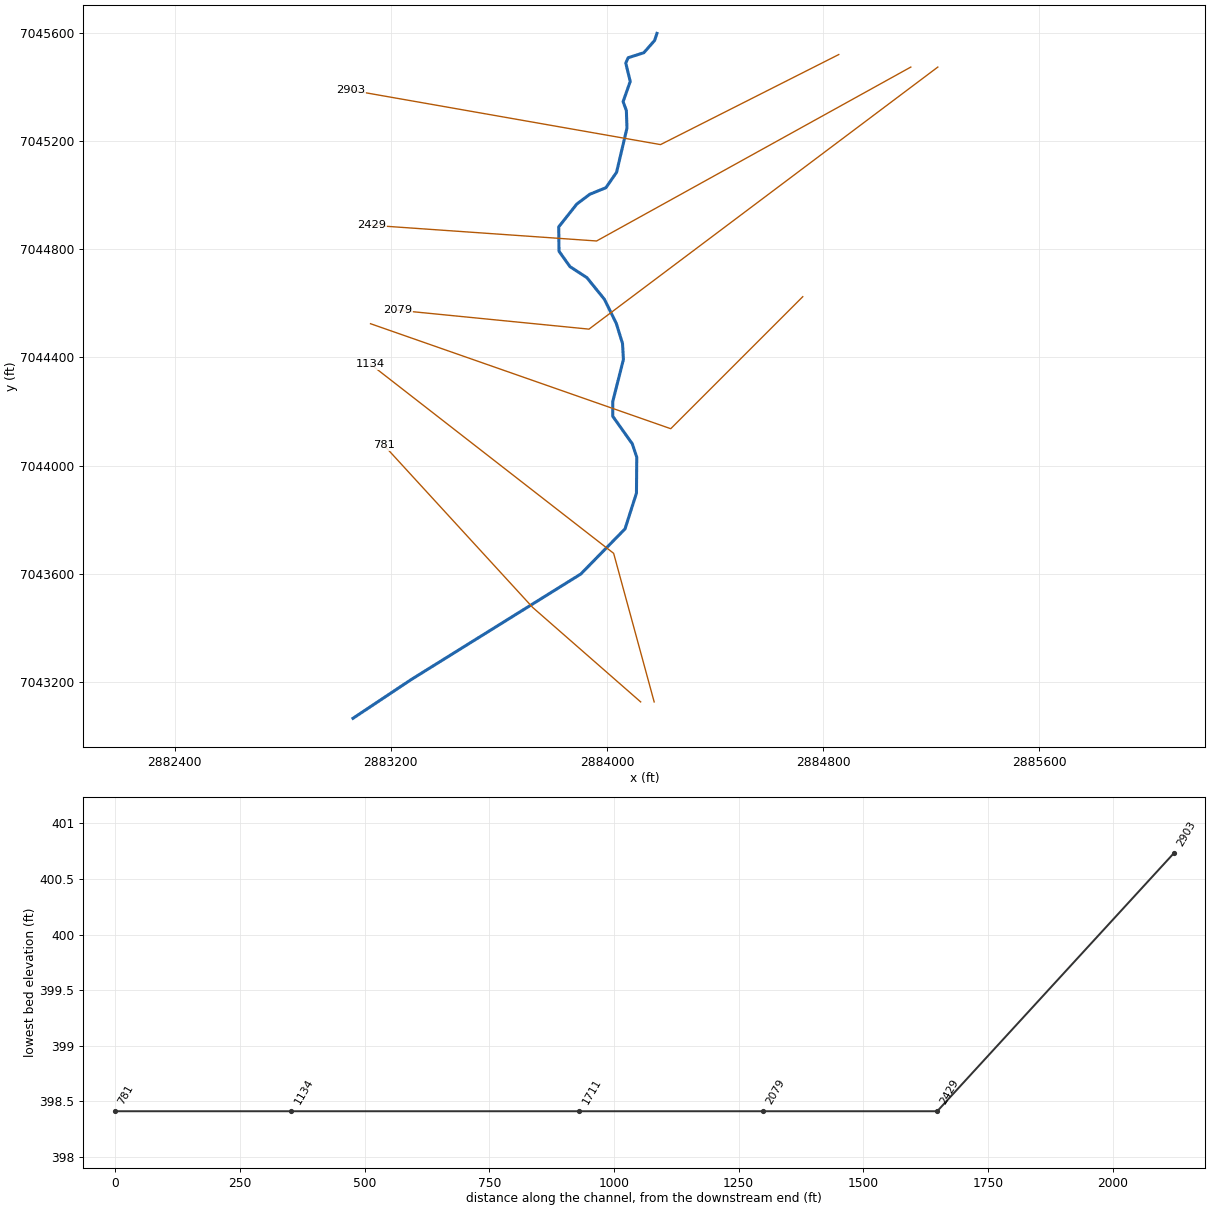
--- UNT 079 in Running Cr Watershed.prj (project) ---

Proj Title=UNT 079 in Running Cr Watershed Base Level Engineering
Current Plan=p01
Default Exp/Contr=0.3,0.1
English Units
Geom File=g01
Flow File=f01
Plan File=p01
BEGIN DESCRIPTION:
UNT 079 in Running Cr Watershed
END DESCRIPTION:

--- UNT 079 in Running Cr Watershed.p01 (plan) ---

Plan Title=Multiple Run
Short Identifier=Multiple
Geom File=g01
Flow File=f01
Subcritical Flow
K Sum by GR= 0
Std Step Tol= 0.01
Critical Tol= 0.01
Num of Std Step Trials= 20
Max Error Tol= 0.3
Flow Tol Ratio= 0.001
Split Flow NTrial= 30
Split Flow Tol= 0.02
Split Flow Ratio= 0.02
Log Output Level= 0
Friction Slope Method= 1
Unsteady Friction Slope Method= 2
Unsteady Bridges Friction Slope Method= 1
Parabolic Critical Depth
Global Vel Dist=  1 , 1 , 1
Global Log Level= 0
CheckData=True
Encroach Param= -1, 0, 0, 0
BEGIN DESCRIPTION:
Multiple Run
END DESCRIPTION:

--- UNT 079 in Running Cr Watershed.f01 (steady flow) ---

Flow Title=Multiple
Number of Profiles=7
Profile Names=10-year,25-year,50-year,1pct_min,100-year,1pct_plu,500-year
River Rch & RM= UNT 079 in Runni,Reach-1,2903
     421     550     652     384     767    1530    1063
Boundary for River Rch & Prof#=UNT 079 in Runni,Reach-1,1
Up Type=0
Dn Type=3
Dn Slope=0.005
Boundary for River Rch & Prof#=UNT 079 in Runni,Reach-1,2
Up Type=0
Dn Type=3
Dn Slope=0.005
Boundary for River Rch & Prof#=UNT 079 in Runni,Reach-1,3
Up Type=0
Dn Type=3
Dn Slope=0.005
Boundary for River Rch & Prof#=UNT 079 in Runni,Reach-1,4
Up Type=0
Dn Type=3
Dn Slope=0.005
Boundary for River Rch & Prof#=UNT 079 in Runni,Reach-1,5
Up Type=0
Dn Type=3
Dn Slope=0.005
Boundary for River Rch & Prof#=UNT 079 in Runni,Reach-1,6
Up Type=0
Dn Type=3
Dn Slope=0.005
Boundary for River Rch & Prof#=UNT 079 in Runni,Reach-1,7
Up Type=0
Dn Type=3
Dn Slope=0.005

--- UNT 079 in Running Cr Watershed.g01 (geometry) ---

Geom Title=Existing Conditions

River Reach=UNT 079 in Runni,Reach-1
Reach XY= 30
      2884185.24      7045599.63      2884176.45      7045573.26
      2884136.90      7045528.22      2884078.68      7045509.54
      2884069.89      7045489.77      2884086.37      7045421.66
      2884060.00      7045346.96      2884072.09      7045314.00
      2884074.28      7045249.18      2884035.83      7045085.50
      2883996.28      7045028.37      2883936.96      7045004.21
      2883888.63      7044967.95      2883821.61      7044883.36
      2883822.71      7044793.28      2883863.36      7044736.16
      2883925.98      7044695.51      2883990.79      7044615.31
      2884034.73      7044526.33      2884057.80      7044451.63
      2884061.10      7044392.31      2884021.55      7044236.31
      2884021.55      7044182.48      2884094.06      7044080.32
      2884110.53      7044030.88      2884109.44      7043897.95
      2884067.09      7043765.49      2883903.27      7043598.32
      2883274.73      7043207.16      2883060.07      7043064.28

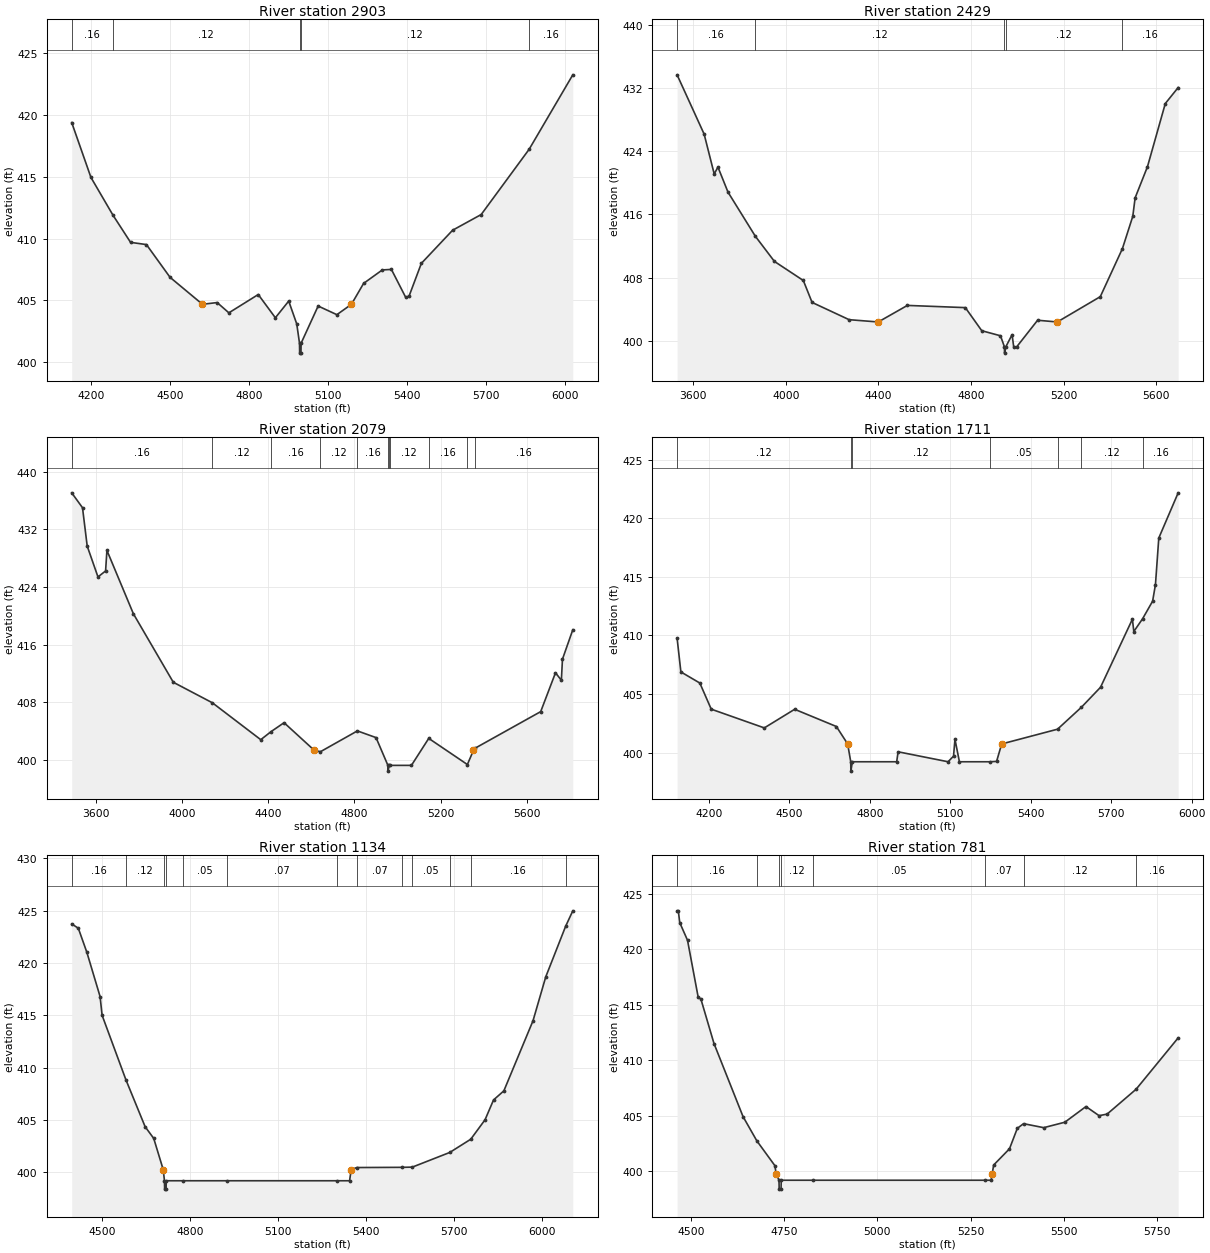
Type RM Length L Ch R = 1,2903,474,474,474
BEGIN DESCRIPTION:
UNT 079 in Running Cr Watershed 6.0
END DESCRIPTION:
XS GIS Cut Line= 3
      2884858.24      7045521.32      2884198.53      7045188.00
      2883052.73      7045389.38
#Sta/Elev= 30
  4125.7  419.38  4198.7  414.94  4282.3  411.89  4349.1  409.69  4409.4  409.51
  4499.1  406.86  4622.1  404.68  4677.9  404.82  4722.4  403.99  4833.9  405.47
  4898.9  403.59  4949.6  404.94  4980.1  403.09  4990.6  401.53  4991.1  400.73
  4996.1  400.73  4996.6  401.53  5061.3  404.54  5132.4  403.84  5187.8  404.68
  5233.9  406.37  5305.0  407.46  5339.5  407.50  5393.8  405.24  5406.5  405.34
  5453.2  407.99  5571.8  410.67  5680.4  411.94  5862.5  417.22  6028.2  423.24
#Mann=5,-1,0
  4125.7    0.16       0  4282.3    0.12       0  4990.6    0.07       0
  4996.6    0.12       0  5862.5    0.16       0
Bank Sta=4622.1,5187.8
Exp/Cntr=0.3,0.1

Type RM Length L Ch R = 1,2429,350,350,350
BEGIN DESCRIPTION:
UNT 079 in Running Cr Watershed 5.0
END DESCRIPTION:
XS GIS Cut Line= 3
      2885125.01      7045475.00      2883961.88      7044831.22
      2883129.52      7044889.36
#Sta/Elev= 30
  3530.5  433.70  3647.3  426.18  3690.8  421.13  3706.9  422.00  3750.4  418.82
  3868.4  413.23  3950.8  410.04  4075.6  407.62  4113.4  404.84  4273.4  402.65
  4399.1  402.36  4524.9  404.46  4775.2  404.18  4846.2  401.25  4927.0  400.61
  4944.0  399.21  4944.5  398.41  4950.0  399.21  4977.1  400.75  4984.0  399.22
  4997.1  399.21  5087.3  402.58  5172.3  402.36  5358.0  405.57  5453.5  411.66
  5498.3  415.76  5508.4  418.10  5561.7  422.05  5638.7  430.06  5694.3  432.09
#Mann=5,-1,0
  3530.5    0.16       0  3868.4    0.12       0  4944.0    0.07       0
  4950.0    0.12       0  5453.5    0.16       0
Bank Sta=4399.1,5172.3
Exp/Cntr=0.3,0.1

Type RM Length L Ch R = 1,2079,368,368,368
BEGIN DESCRIPTION:
UNT 079 in Running Cr Watershed 4.0
END DESCRIPTION:
XS GIS Cut Line= 3
      2885225.03      7045475.02      2883933.66      7044504.91
      2883224.98      7044575.00
#Sta/Elev= 30
  3486.7  437.09  3536.8  435.02  3558.6  429.69  3608.6  425.40  3644.0  426.23
  3650.2  429.09  3773.1  420.28  3958.5  410.76  4139.9  407.91  4364.7  402.78
  4412.5  403.90  4473.0  405.14  4613.7  401.29  4642.0  401.11  4813.5  404.00
  4900.1  403.07  4955.3  399.21  4955.8  398.41  4961.3  399.21  4964.3  399.21
  5064.5  399.21  5144.9  402.96  5324.3  399.33  5352.6  401.29  5361.7  401.62
  5664.9  406.68  5733.6  412.08  5760.9  411.04  5766.0  413.97  5814.0  418.06
#Mann=11,-1,0
  3486.7    0.16       0  4139.9    0.12       0  4412.5    0.16       0
  4642.0    0.12       0  4813.5    0.16       0  4955.3    0.07       0
  4961.3    0.16       0  4964.3    0.12       0  5144.9    0.16       0
  5324.3    0.08       0  5361.7    0.16       0
Bank Sta=4613.7,5352.6
Exp/Cntr=0.3,0.1

Type RM Length L Ch R = 1,1711,577,577,577
BEGIN DESCRIPTION:
UNT 079 in Running Cr Watershed 3.0
END DESCRIPTION:
XS GIS Cut Line= 3
      2884724.98      7044624.98      2884236.32      7044136.32
      2883125.00      7044525.00
#Sta/Elev= 30
  4081.4  409.77  4095.5  406.88  4166.2  405.93  4208.7  403.70  4406.6  402.10
  4519.8  403.69  4675.3  402.22  4717.4  400.73  4728.9  399.21  4729.4  398.41
  4734.9  399.21  4900.2  399.21  4905.5  400.06  5091.8  399.21  5112.2  399.69
  5117.5  401.13  5134.1  399.21  5247.7  399.21  5272.7  399.24  5291.7  400.73
  5500.0  401.99  5589.3  403.87  5660.3  405.57  5779.1  411.38  5784.4  410.33
  5817.4  411.43  5854.5  412.92  5865.1  414.34  5877.5  418.31  5949.8  422.17
#Mann=7,-1,0
  4081.4    0.12       0  4728.9    0.07       0  4734.9    0.12       0
  5247.7    0.05       0  5500.0    0.16       0  5589.3    0.12       0
  5817.4    0.16       0
Bank Sta=4717.4,5291.7
Exp/Cntr=0.3,0.1

Type RM Length L Ch R = 1,1134,353,353,353
BEGIN DESCRIPTION:
UNT 079 in Running Cr Watershed 2.0
END DESCRIPTION:
XS GIS Cut Line= 3
      2884175.00      7043124.98      2884025.00      7043675.00
      2883124.98      7044375.01
#Sta/Elev= 30
  4396.4  423.72  4418.9  423.31  4448.2  421.00  4493.2  416.79  4500.1  415.00
  4581.3  408.85  4646.9  404.37  4676.3  403.25  4708.6  400.28  4713.0  399.21
  4713.5  398.41  4718.5  398.41  4719.0  399.21  4776.6  399.21  4926.8  399.21
  5303.3  399.21  5344.8  399.21  5350.3  400.28  5369.6  400.47  5524.3  400.49
  5558.9  400.51  5686.7  401.91  5758.3  403.17  5807.2  405.03  5836.1  406.92
  5871.4  407.79  5970.9  414.48  6014.4  418.67  6082.3  423.50  6106.7  424.97
#Mann=13,-1,0
  4396.4    0.16       0  4581.3    0.12       0  4713.0    0.07       0
  4719.0    0.12       0  4776.6    0.05       0  4926.8    0.07       0
  5303.3    0.05       0  5369.6    0.07       0  5524.3    0.16       0
  5558.9    0.05       0  5686.7    0.12       0  5758.3    0.16       0
  6082.3    0.12       0
Bank Sta=4708.6,5350.3
Exp/Cntr=0.3,0.1

Type RM Length L Ch R = 1,781,0,0,0
BEGIN DESCRIPTION:
UNT 079 in Running Cr Watershed 1.0
END DESCRIPTION:
XS GIS Cut Line= 3
      2884124.97      7043125.03      2883725.00      7043475.00
      2883175.00      7044074.99
#Sta/Elev= 30
  4462.2  423.45  4465.5  423.45  4469.3  422.39  4490.2  420.80  4518.6  415.72
  4526.2  415.50  4561.3  411.51  4639.2  404.94  4676.2  402.76  4724.6  400.53
  4728.5  399.76  4735.8  399.21  4736.3  398.41  4741.3  398.41  4741.8  399.21
  4826.2  399.21  5287.8  399.21  5305.4  399.21  5308.1  399.76  5312.2  400.58
  5354.7  402.04  5375.7  403.88  5392.4  404.30  5446.6  403.94  5503.3  404.43
  5560.0  405.84  5595.2  405.02  5616.8  405.16  5694.7  407.40  5807.6  412.02
#Mann=8,-1,0
  4462.2    0.16       0  4676.2    0.12       0  4735.8   0.033       0
  4741.8    0.12       0  4826.2    0.05       0  5287.8    0.07       0
  5392.4    0.12       0  5694.7    0.16       0
Bank Sta=4728.5,5308.1
Exp/Cntr=0.3,0.1

Chan Stop Cuts=-1