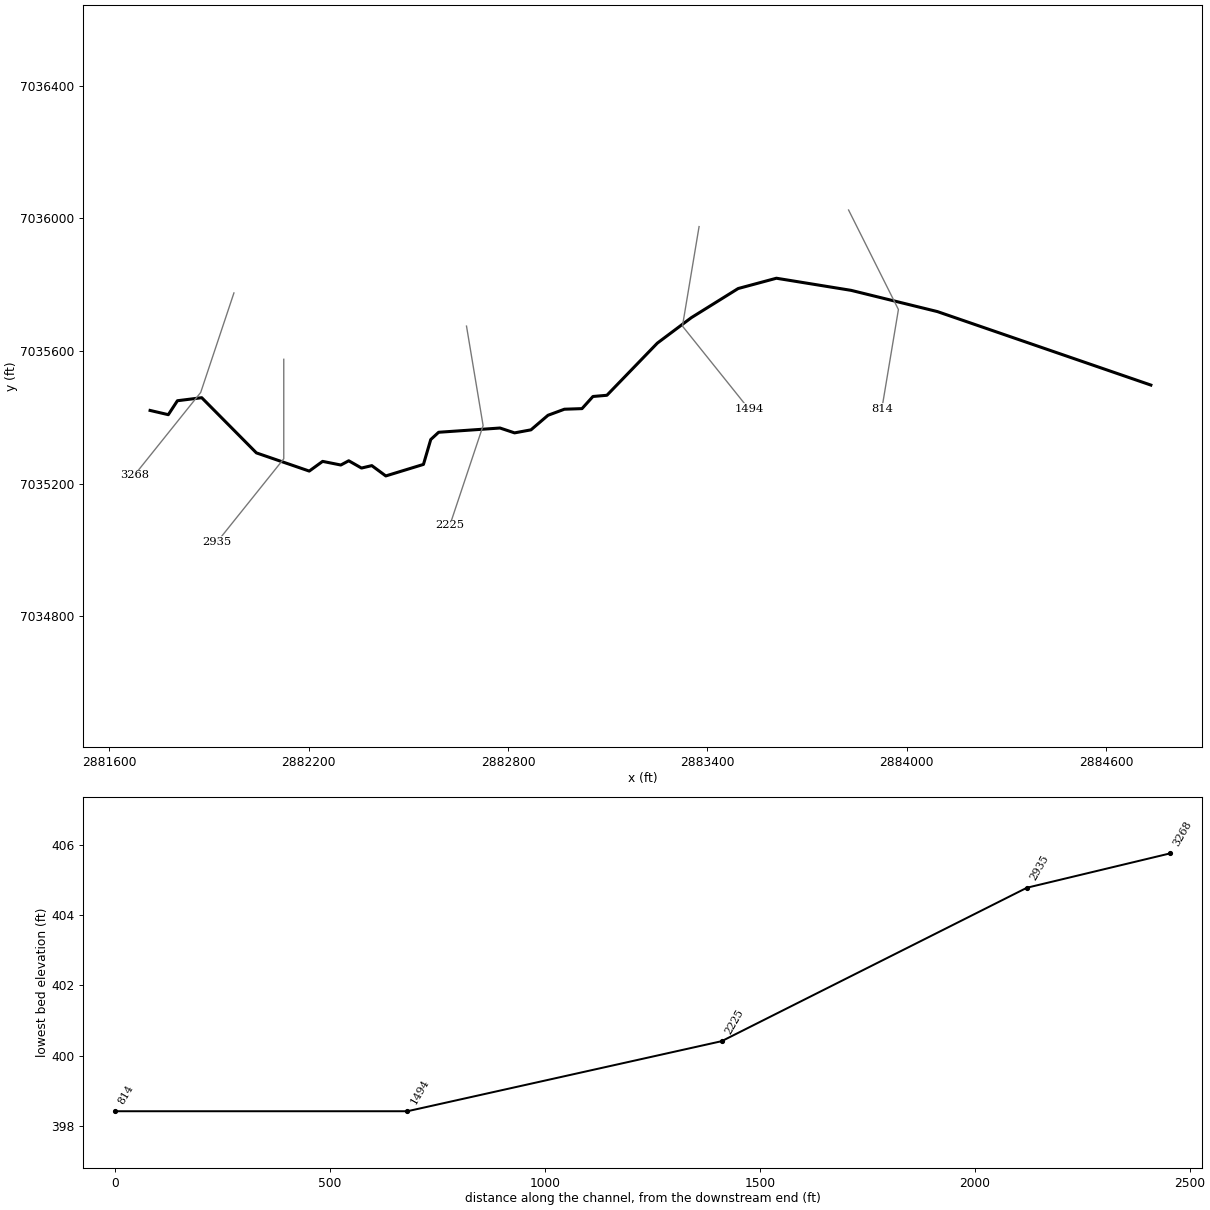
--- UNT 080 in Running Cr Watershed.prj (project) ---

Proj Title=UNT 080 in Running Cr Watershed Base Level Engineering
Current Plan=p01
Default Exp/Contr=0.3,0.1
English Units
Geom File=g01
Flow File=f01
Plan File=p01
BEGIN DESCRIPTION:
UNT 080 in Running Cr Watershed
END DESCRIPTION:

--- UNT 080 in Running Cr Watershed.p01 (plan) ---

Plan Title=Multiple Run
Short Identifier=Multiple
Geom File=g01
Flow File=f01
Subcritical Flow
K Sum by GR= 0
Std Step Tol= 0.01
Critical Tol= 0.01
Num of Std Step Trials= 20
Max Error Tol= 0.3
Flow Tol Ratio= 0.001
Split Flow NTrial= 30
Split Flow Tol= 0.02
Split Flow Ratio= 0.02
Log Output Level= 0
Friction Slope Method= 1
Unsteady Friction Slope Method= 2
Unsteady Bridges Friction Slope Method= 1
Parabolic Critical Depth
Global Vel Dist=  1 , 1 , 1
Global Log Level= 0
CheckData=True
Encroach Param= -1, 0, 0, 0
BEGIN DESCRIPTION:
Multiple Run
END DESCRIPTION:

--- UNT 080 in Running Cr Watershed.f01 (steady flow) ---

Flow Title=Multiple
Number of Profiles=7
Profile Names=10-year,25-year,50-year,1pct_min,100-year,1pct_plu,500-year
River Rch & RM= UNT 080 in Runni,Reach-1,3268
     254     320     370     213     425     848     561
Boundary for River Rch & Prof#=UNT 080 in Runni,Reach-1,1
Up Type=0
Dn Type=3
Dn Slope=0.005
Boundary for River Rch & Prof#=UNT 080 in Runni,Reach-1,2
Up Type=0
Dn Type=3
Dn Slope=0.005
Boundary for River Rch & Prof#=UNT 080 in Runni,Reach-1,3
Up Type=0
Dn Type=3
Dn Slope=0.005
Boundary for River Rch & Prof#=UNT 080 in Runni,Reach-1,4
Up Type=0
Dn Type=3
Dn Slope=0.005
Boundary for River Rch & Prof#=UNT 080 in Runni,Reach-1,5
Up Type=0
Dn Type=3
Dn Slope=0.005
Boundary for River Rch & Prof#=UNT 080 in Runni,Reach-1,6
Up Type=0
Dn Type=3
Dn Slope=0.005
Boundary for River Rch & Prof#=UNT 080 in Runni,Reach-1,7
Up Type=0
Dn Type=3
Dn Slope=0.005

--- UNT 080 in Running Cr Watershed.g01 (geometry) ---

Geom Title=Existing Conditions

River Reach=UNT 080 in Runni,Reach-1
Reach XY= 30
      2881722.66      7035420.76      2881777.51      7035407.96
      2881804.94      7035450.02      2881878.08      7035459.16
      2882042.63      7035292.77      2882201.70      7035237.92
      2882241.93      7035267.18      2882296.78      7035256.21
      2882320.55      7035269.00      2882358.95      7035247.06
      2882390.03      7035254.38      2882432.08      7035223.29
      2882545.44      7035258.03      2882567.38      7035333.00
      2882591.15      7035354.94      2882775.82      7035367.74
      2882819.70      7035353.11      2882869.07      7035362.25
      2882920.27      7035406.14      2882969.63      7035424.42
      2883022.66      7035426.25      2883055.57      7035462.82
      2883097.62      7035466.47      2883249.38      7035623.72
      2883351.77      7035700.51      2883492.56      7035788.27
      2883607.75      7035819.35      2883832.64      7035782.79
      2884092.27      7035718.79      2884734.84      7035497.22

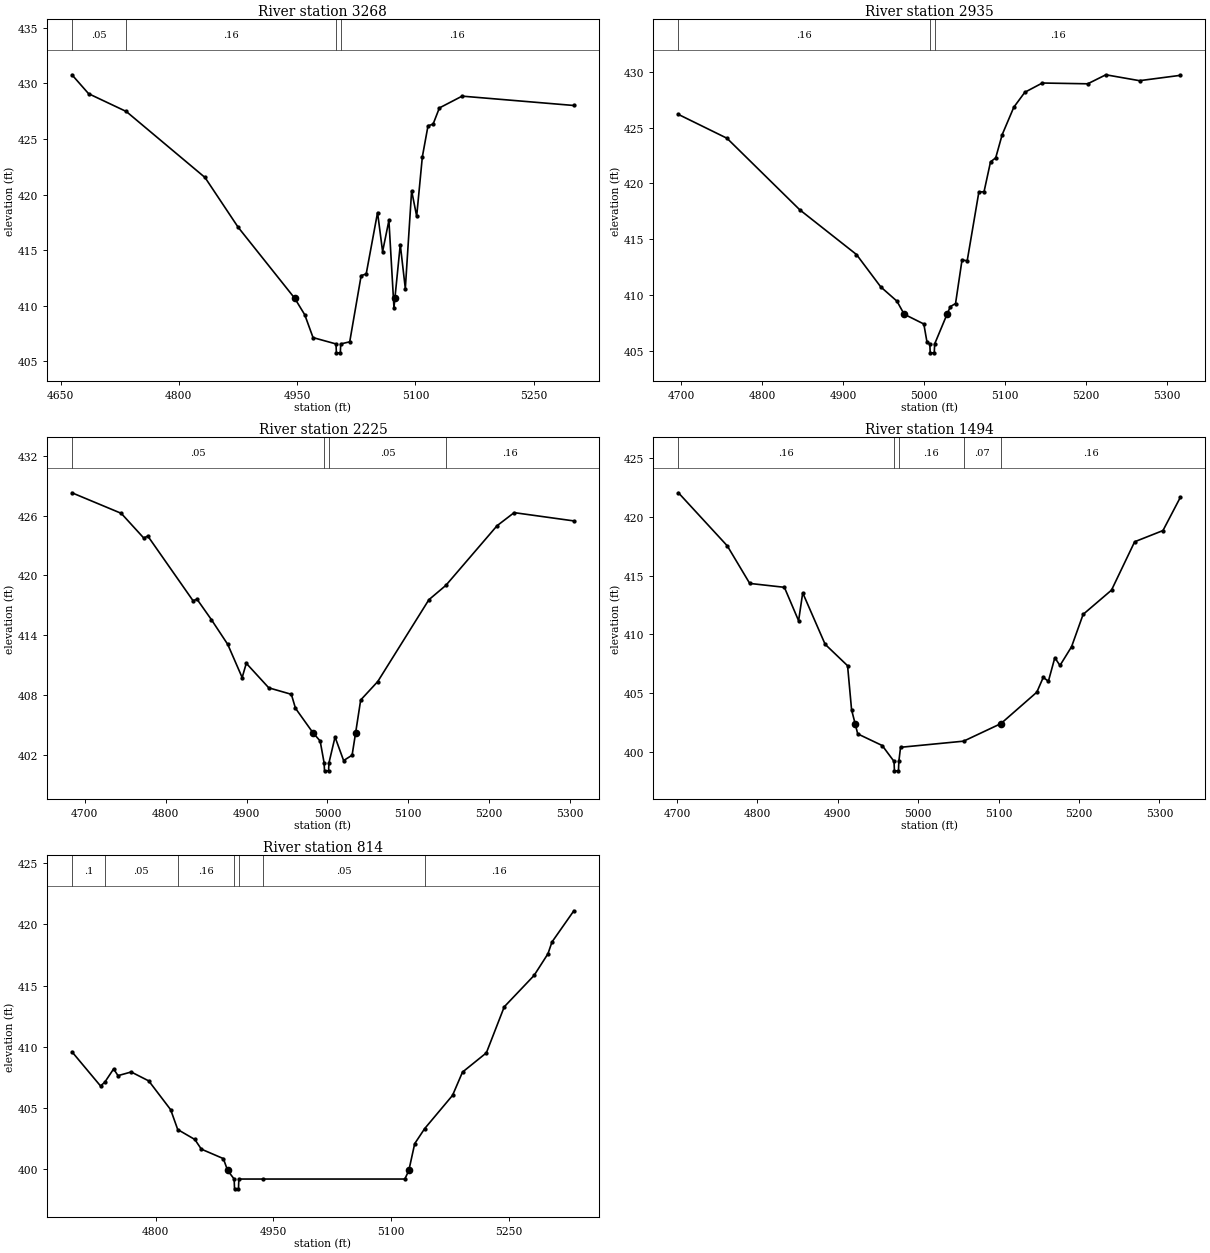
Type RM Length L Ch R = 1,3268,333,333,333
BEGIN DESCRIPTION:
UNT 080 in Running Cr Watershed 5.0
END DESCRIPTION:
XS GIS Cut Line= 3
      2881975.00      7035775.00      2881875.00      7035475.00
      2881674.99      7035224.99
#Sta/Elev= 30
  4664.5  430.76  4685.6  429.06  4733.4  427.46  4833.2  421.53  4875.3  417.05
  4946.9  410.68  4959.7  409.19  4970.2  407.14  4999.3  406.57  4999.8  405.77
  5004.8  405.77  5005.3  406.57  5016.7  406.76  5031.2  412.71  5037.6  412.86
  5052.0  418.38  5058.4  414.87  5066.4  417.67  5072.8  409.83  5074.0  410.68
  5080.8  415.50  5087.2  411.55  5095.2  420.34  5101.6  418.05  5108.8  423.39
  5116.0  426.18  5122.4  426.32  5130.4  427.78  5159.2  428.84  5300.9  428.00
#Mann=4,-1,0
  4664.5    0.05       0  4733.4    0.16       0  4999.3    0.07       0
  5005.3    0.16       0
Bank Sta=4946.9,5074
Exp/Cntr=0.3,0.1

Type RM Length L Ch R = 1,2935,710,710,710
BEGIN DESCRIPTION:
UNT 080 in Running Cr Watershed 4.0
END DESCRIPTION:
XS GIS Cut Line= 3
      2882125.00      7035574.96      2882125.00      7035275.00
      2881925.01      7035025.01
#Sta/Elev= 30
  4696.3  426.20  4756.3  424.06  4846.3  417.63  4916.3  413.62  4946.3  410.71
  4966.3  409.43  4975.2  408.26  4999.5  407.38  5003.5  405.72  5006.9  405.59
  5007.4  404.79  5012.4  404.79  5012.9  405.59  5028.2  408.26  5032.3  408.94
  5038.7  409.22  5046.7  413.13  5053.1  413.06  5067.5  419.23  5073.9  419.26
  5081.9  421.94  5088.3  422.30  5096.3  424.38  5110.7  426.85  5124.3  428.19
  5145.9  429.02  5202.0  428.95  5224.4  429.76  5266.0  429.23  5316.4  429.71
#Mann=3,-1,0
  4696.3    0.16       0  5006.9    0.07       0  5012.9    0.16       0
Bank Sta=4975.2,5028.2
Exp/Cntr=0.3,0.1

Type RM Length L Ch R = 1,2225,731,731,731
BEGIN DESCRIPTION:
UNT 080 in Running Cr Watershed 3.0
END DESCRIPTION:
XS GIS Cut Line= 3
      2882675.00      7035675.03      2882725.00      7035375.00
      2882625.00      7035074.99
#Sta/Elev= 30
  4684.2  428.28  4745.1  426.22  4772.9  423.75  4778.0  423.94  4833.8  417.47
  4838.8  417.61  4856.6  415.56  4876.8  413.08  4894.6  409.76  4899.7  411.19
  4927.5  408.73  4955.4  408.08  4960.5  406.68  4981.9  404.25  4991.0  403.40
  4995.9  401.21  4996.4  400.41  5001.4  400.41  5001.9  401.21  5009.4  403.80
  5020.0  401.44  5030.5  401.98  5034.9  404.25  5041.1  407.51  5062.2  409.36
  5125.4  417.56  5146.4  419.00  5209.7  424.98  5230.8  426.29  5304.6  425.46
#Mann=4,-1,0
  4684.2    0.05       0  4995.9    0.04       0  5001.9    0.05       0
  5146.4    0.16       0
Bank Sta=4981.9,5034.9
Exp/Cntr=0.3,0.1

Type RM Length L Ch R = 1,1494,680,680,680
BEGIN DESCRIPTION:
UNT 080 in Running Cr Watershed 2.0
END DESCRIPTION:
XS GIS Cut Line= 3
      2883375.00      7035975.01      2883325.00      7035675.00
      2883524.99      7035425.01
#Sta/Elev= 30
  4701.7  422.03  4762.5  417.52  4790.4  414.33  4833.5  414.00  4851.2  411.16
  4856.3  413.53  4884.2  409.16  4912.1  407.34  4917.1  403.59  4921.5  402.42
  4924.7  401.55  4955.2  400.56  4969.9  399.21  4970.4  398.41  4975.4  398.41
  4975.9  399.21  4978.0  400.41  5056.4  400.93  5102.8  402.42  5147.5  405.09
  5155.5  406.35  5161.9  406.02  5169.9  408.02  5176.3  407.36  5190.7  408.95
  5205.1  411.70  5240.4  413.76  5269.2  417.87  5304.4  418.82  5326.0  421.64
#Mann=5,-1,0
  4701.7    0.16       0  4969.9    0.07       0  4975.9    0.16       0
  5056.4    0.07       0  5102.8    0.16       0
Bank Sta=4921.5,5102.8
Exp/Cntr=0.3,0.1

Type RM Length L Ch R = 1,814,0,0,0
BEGIN DESCRIPTION:
UNT 080 in Running Cr Watershed 1.0
END DESCRIPTION:
XS GIS Cut Line= 3
      2883824.98      7036025.03      2883975.00      7035725.00
      2883925.00      7035424.98
#Sta/Elev= 30
  4693.5  409.60  4729.9  406.81  4735.3  407.11  4746.6  408.20  4752.2  407.65
  4769.0  407.95  4791.4  407.22  4819.3  404.87  4828.3  403.25  4850.1  402.44
  4858.4  401.65  4886.4  400.88  4891.9  399.91  4900.2  399.21  4900.7  398.41
  4905.7  398.41  4906.2  399.21  4936.4  399.21  5117.7  399.21  5122.8  399.91
  5130.3  402.10  5142.9  403.32  5178.5  406.04  5191.2  407.94  5221.6  409.51
  5244.4  413.27  5282.4  415.83  5300.1  417.60  5305.2  418.56  5333.1  421.11
#Mann=7,-1,0
  4693.5     0.1       0  4735.3    0.05       0  4828.3    0.16       0
  4900.2   0.033       0  4906.2    0.16       0  4936.4    0.05       0
  5142.9    0.16       0
Bank Sta=4891.9,5122.8
Exp/Cntr=0.3,0.1

Chan Stop Cuts=-1