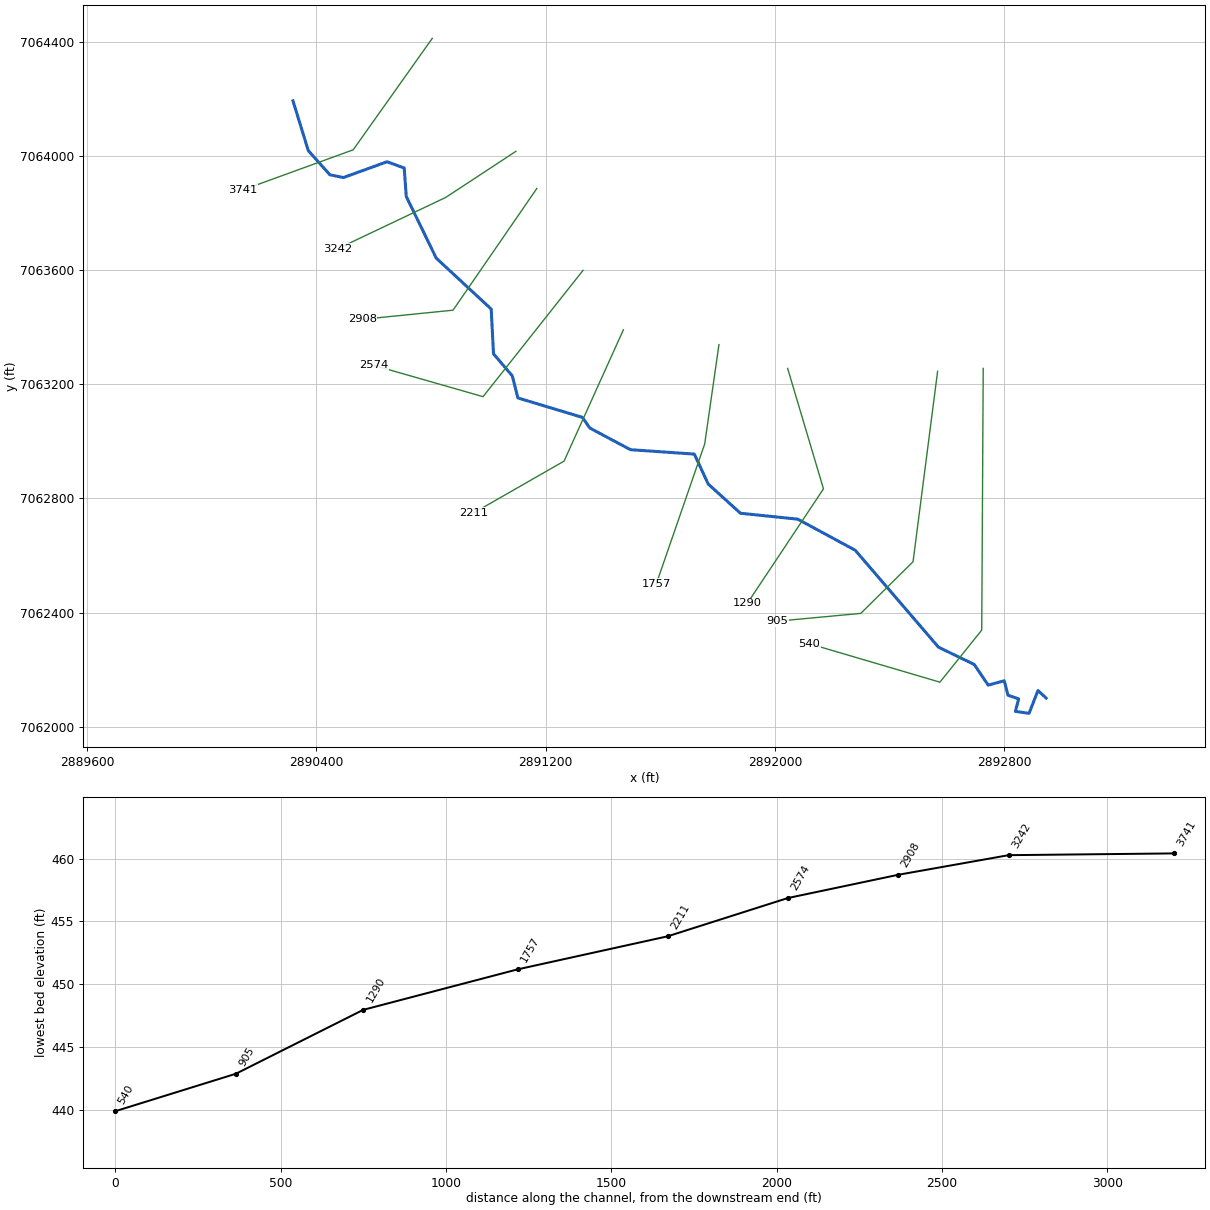
--- UNT 081 in Running Cr Watershed.prj (project) ---

Proj Title=UNT 081 in Running Cr Watershed Base Level Engineering
Current Plan=p01
Default Exp/Contr=0.3,0.1
English Units
Geom File=g01
Flow File=f01
Plan File=p01
BEGIN DESCRIPTION:
UNT 081 in Running Cr Watershed
END DESCRIPTION:

--- UNT 081 in Running Cr Watershed.p01 (plan) ---

Plan Title=Multiple Run
Short Identifier=Multiple
Geom File=g01
Flow File=f01
Subcritical Flow
K Sum by GR= 0
Std Step Tol= 0.01
Critical Tol= 0.01
Num of Std Step Trials= 20
Max Error Tol= 0.3
Flow Tol Ratio= 0.001
Split Flow NTrial= 30
Split Flow Tol= 0.02
Split Flow Ratio= 0.02
Log Output Level= 0
Friction Slope Method= 1
Unsteady Friction Slope Method= 2
Unsteady Bridges Friction Slope Method= 1
Parabolic Critical Depth
Global Vel Dist=  1 , 1 , 1
Global Log Level= 0
CheckData=True
Encroach Param= -1, 0, 0, 0
BEGIN DESCRIPTION:
Multiple Run
END DESCRIPTION:

--- UNT 081 in Running Cr Watershed.f01 (steady flow) ---

Flow Title=Multiple
Number of Profiles=7
Profile Names=10-year,25-year,50-year,1pct_min,100-year,1pct_plu,500-year
River Rch & RM= UNT 081 in Runni,Reach-1,3741
     801    1084    1315     791    1579    3150    2270
Boundary for River Rch & Prof#=UNT 081 in Runni,Reach-1,1
Up Type=0
Dn Type=3
Dn Slope=0.005
Boundary for River Rch & Prof#=UNT 081 in Runni,Reach-1,2
Up Type=0
Dn Type=3
Dn Slope=0.005
Boundary for River Rch & Prof#=UNT 081 in Runni,Reach-1,3
Up Type=0
Dn Type=3
Dn Slope=0.005
Boundary for River Rch & Prof#=UNT 081 in Runni,Reach-1,4
Up Type=0
Dn Type=3
Dn Slope=0.005
Boundary for River Rch & Prof#=UNT 081 in Runni,Reach-1,5
Up Type=0
Dn Type=3
Dn Slope=0.005
Boundary for River Rch & Prof#=UNT 081 in Runni,Reach-1,6
Up Type=0
Dn Type=3
Dn Slope=0.005
Boundary for River Rch & Prof#=UNT 081 in Runni,Reach-1,7
Up Type=0
Dn Type=3
Dn Slope=0.005

--- UNT 081 in Running Cr Watershed.g01 (geometry) ---

Geom Title=Existing Conditions

River Reach=UNT 081 in Runni,Reach-1
Reach XY= 30
      2890318.20      7064192.65      2890371.65      7064018.27
      2890447.02      7063933.66      2890494.20      7063923.92
      2890646.36      7063979.31      2890706.16      7063957.40
      2890713.49      7063857.59      2890817.99      7063641.68
      2891009.71      7063463.33      2891017.77      7063306.40
      2891083.09      7063229.59      2891102.98      7063151.91
      2891327.66      7063083.96      2891353.73      7063046.53
      2891495.59      7062970.71      2891718.37      7062955.29
      2891766.57      7062850.63      2891879.21      7062748.07
      2892079.05      7062727.36      2892279.59      7062618.50
      2892569.98      7062278.98      2892694.65      7062218.39
      2892743.48      7062145.99      2892799.38      7062161.24
      2892812.64      7062110.48      2892849.74      7062097.84
      2892838.25      7062054.21      2892885.95      7062047.07
      2892917.00      7062127.02      2892945.59      7062100.71

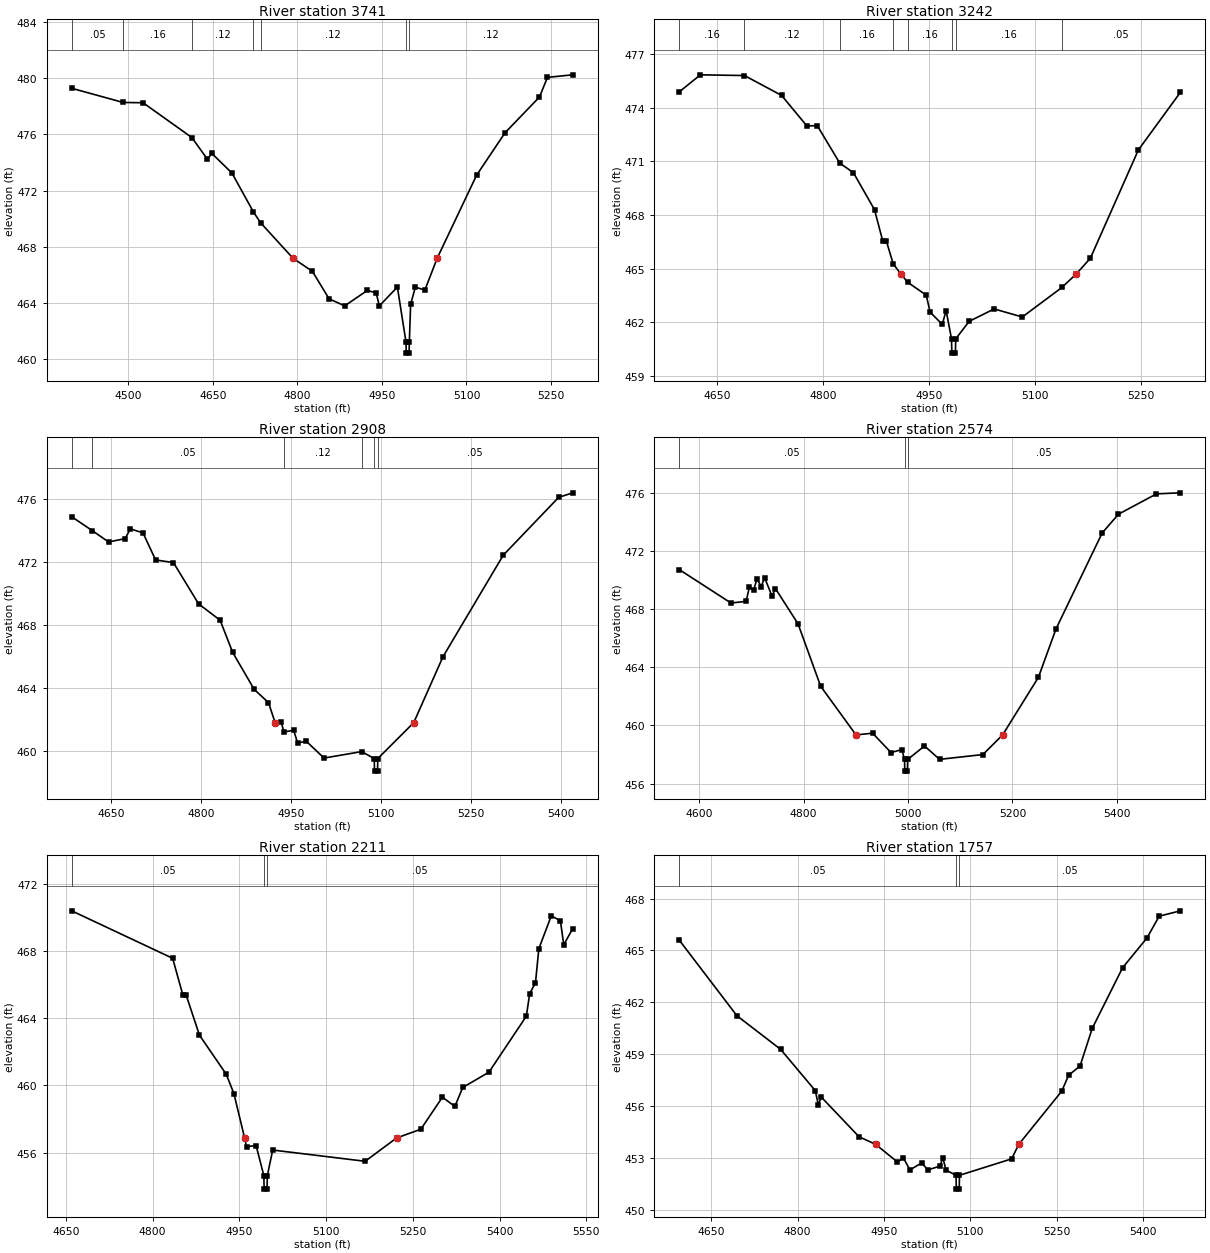
Type RM Length L Ch R = 1,3741,499,499,499
BEGIN DESCRIPTION:
UNT 081 in Running Cr Watershed 8.0
END DESCRIPTION:
XS GIS Cut Line= 3
      2890804.20      7064411.61      2890528.18      7064021.02
      2890142.81      7063880.41
#Sta/Elev= 30
  4400.0  479.29  4491.2  478.28  4526.5  478.26  4613.0  475.78  4640.7  474.23
  4648.4  474.65  4684.1  473.25  4722.0  470.49  4734.8  469.71  4792.5  467.17
  4826.8  466.24  4856.4  464.28  4884.1  463.78  4924.2  464.88  4939.9  464.70
  4945.5  463.78  4977.5  465.12  4992.7  461.21  4993.2  460.41  4998.2  460.41
  4998.7  461.21  5001.0  463.89  5009.4  465.12  5026.2  464.90  5048.0  467.17
  5117.9  473.09  5168.4  476.12  5229.5  478.67  5243.6  480.07  5288.5  480.25
#Mann=7,-1,0
  4400.0    0.05       0  4491.2    0.16       0  4613.0    0.12       0
  4722.0    0.16       0  4734.8    0.12       0  4992.7    0.07       0
  4998.7    0.12       0
Bank Sta=4792.5,5048
Exp/Cntr=0.3,0.1

Type RM Length L Ch R = 1,3242,334,334,334
BEGIN DESCRIPTION:
UNT 081 in Running Cr Watershed 7.0
END DESCRIPTION:
XS GIS Cut Line= 3
      2891095.93      7064015.83      2890851.10      7063854.35
      2890474.96      7063674.98
#Sta/Elev= 30
  4596.4  474.88  4626.3  475.83  4688.7  475.79  4741.3  474.68  4777.2  472.97
  4791.9  472.99  4823.8  470.89  4843.1  470.36  4873.0  468.29  4884.6  466.55
  4889.7  466.55  4899.5  465.26  4910.6  464.68  4920.1  464.23  4946.3  463.51
  4951.8  462.56  4969.0  461.88  4974.5  462.65  4982.1  461.07  4982.6  460.27
  4987.6  460.27  4988.1  461.07  5007.2  462.05  5042.6  462.74  5082.4  462.29
  5138.5  463.94  5158.5  464.68  5178.8  465.57  5246.9  471.63  5306.4  474.85
#Mann=8,-1,0
  4596.4    0.16       0  4688.7    0.12       0  4823.8    0.16       0
  4899.5    0.12       0  4920.1    0.16       0  4982.1    0.07       0
  4988.1    0.16       0  5138.5    0.05       0
Bank Sta=4910.6,5158.5
Exp/Cntr=0.3,0.1

Type RM Length L Ch R = 1,2908,334,334,334
BEGIN DESCRIPTION:
UNT 081 in Running Cr Watershed 6.0
END DESCRIPTION:
XS GIS Cut Line= 3
      2891168.81      7063885.60      2890876.57      7063459.38
      2890559.68      7063427.29
#Sta/Elev= 30
  4583.8  474.86  4618.1  473.98  4645.2  473.26  4672.8  473.47  4681.5  474.09
  4702.6  473.84  4723.6  472.12  4753.4  471.95  4795.3  469.33  4831.2  468.29
  4852.1  466.25  4888.0  463.90  4911.8  463.06  4922.9  461.79  4932.7  461.84
  4937.8  461.19  4953.7  461.31  4960.4  460.50  4974.7  460.61  5004.5  459.54
  5067.2  459.95  5088.1  459.51  5088.6  458.71  5093.6  458.71  5094.1  459.51
  5154.0  461.79  5202.7  465.97  5303.2  472.42  5395.5  476.09  5419.1  476.38
#Mann=6,-1,0
  4583.8    0.12       0  4618.1    0.05       0  4937.8    0.12       0
  5067.2    0.05       0  5088.1    0.07       0  5094.1    0.05       0
Bank Sta=4922.9,5154
Exp/Cntr=0.3,0.1

Type RM Length L Ch R = 1,2574,363,363,363
BEGIN DESCRIPTION:
UNT 081 in Running Cr Watershed 5.0
END DESCRIPTION:
XS GIS Cut Line= 3
      2891330.24      7063599.11      2890981.31      7063156.44
      2890601.09      7063265.82
#Sta/Elev= 30
  4562.1  470.72  4661.1  468.42  4690.0  468.54  4696.4  469.53  4704.5  469.32
  4710.8  470.08  4718.9  469.55  4725.3  470.17  4739.7  468.89  4746.1  469.42
  4789.4  466.99  4832.7  462.70  4900.4  459.35  4932.1  459.47  4967.4  458.14
  4988.2  458.34  4993.3  457.66  4993.8  456.86  4998.8  456.86  4999.3  457.66
  5031.5  458.59  5060.4  457.67  5143.3  458.00  5181.1  459.35  5249.6  463.31
  5283.3  466.64  5371.7  473.24  5402.9  474.53  5475.7  475.93  5521.4  476.00
#Mann=3,-1,0
  4562.1    0.05       0  4993.3    0.03       0  4999.3    0.05       0
Bank Sta=4900.4,5181.1
Exp/Cntr=0.3,0.1

Type RM Length L Ch R = 1,2211,454,454,454
BEGIN DESCRIPTION:
UNT 081 in Running Cr Watershed 4.0
END DESCRIPTION:
XS GIS Cut Line= 3
      2891470.89      7063390.80      2891263.88      7062930.67
      2890950.03      7062750.17
#Sta/Elev= 30
  4660.0  470.41  4834.6  467.58  4852.2  465.39  4857.7  465.41  4880.9  463.00
  4927.2  460.67  4940.5  459.52  4959.0  456.87  4962.4  456.35  4978.9  456.42
  4992.3  454.62  4992.8  453.82  4997.8  453.82  4998.3  454.62  5007.6  456.15
  5167.5  455.48  5221.9  456.87  5263.8  457.39  5301.1  459.30  5322.7  458.75
  5336.3  459.88  5381.6  460.79  5446.3  464.13  5452.1  465.48  5462.1  466.12
  5467.9  468.15  5489.4  470.11  5505.2  469.82  5511.0  468.39  5526.6  469.35
#Mann=3,-1,0
  4660.0    0.05       0  4992.3    0.03       0  4998.3    0.05       0
Bank Sta=4959,5221.9
Exp/Cntr=0.3,0.1

Type RM Length L Ch R = 1,1757,467,467,467
BEGIN DESCRIPTION:
UNT 081 in Running Cr Watershed 3.0
END DESCRIPTION:
XS GIS Cut Line= 3
      2891804.23      7063338.77      2891754.44      7062990.68
      2891585.48      7062500.20
#Sta/Elev= 30
  4594.5  465.59  4694.6  461.22  4770.4  459.28  4830.7  456.89  4836.0  456.06
  4841.0  456.52  4906.7  454.22  4935.6  453.78  4973.3  452.76  4983.9  452.99
  4995.1  452.30  5015.6  452.71  5026.3  452.30  5047.0  452.52  5052.3  452.99
  5057.9  452.29  5075.2  451.99  5075.7  451.19  5080.7  451.19  5081.2  451.99
  5171.8  452.94  5184.2  453.78  5258.9  456.86  5270.8  457.78  5290.6  458.31
  5311.8  460.49  5364.6  464.00  5406.9  465.72  5428.1  466.98  5464.9  467.29
#Mann=3,-1,0
  4594.5    0.05       0  5075.2    0.03       0  5081.2    0.05       0
Bank Sta=4935.6,5184.2
Exp/Cntr=0.3,0.1

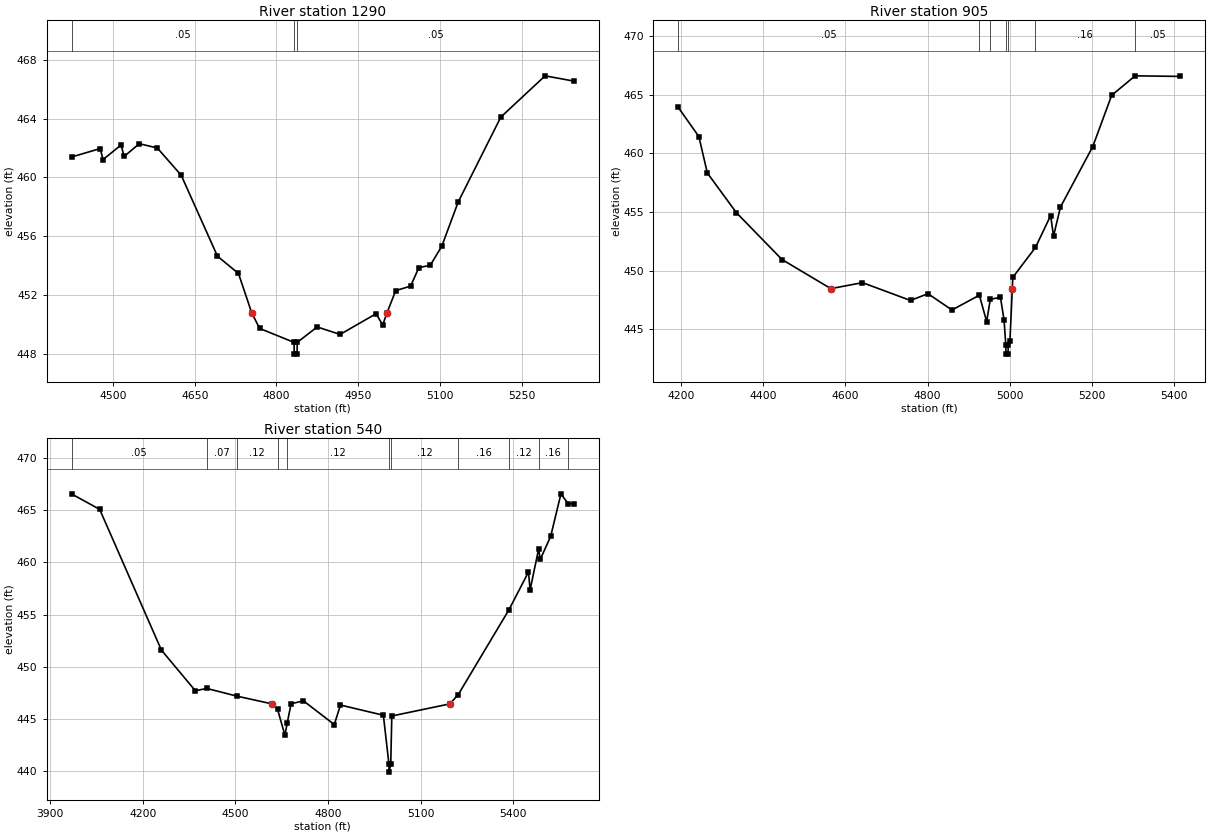
Type RM Length L Ch R = 1,1290,385,385,385
BEGIN DESCRIPTION:
Mapping XS 512f10bb
END DESCRIPTION:
XS GIS Cut Line= 3
      2892043.81      7063255.41      2892168.81      7062833.52
      2891903.21      7062432.52
#Sta/Elev= 30
  4424.5  461.39  4476.7  461.96  4481.9  461.21  4515.1  462.21  4520.4  461.42
  4548.4  462.29  4581.4  462.00  4625.3  460.14  4691.8  454.63  4730.3  453.46
  4754.6  450.78  4769.1  449.72  4832.2  448.77  4832.7  447.97  4837.7  447.97
  4838.2  448.77  4874.6  449.82  4916.7  449.31  4982.7  450.72  4994.9  449.95
  5002.7  450.78  5018.7  452.29  5046.1  452.60  5061.1  453.85  5082.2  454.02
  5103.2  455.31  5133.3  458.32  5211.5  464.10  5292.8  466.91  5345.5  466.55
#Mann=3,-1,0
  4424.5    0.05       0  4832.2    0.03       0  4838.2    0.05       0
Bank Sta=4754.6,5002.7
Exp/Cntr=0.3,0.1

Type RM Length L Ch R = 1,905,365,365,365
BEGIN DESCRIPTION:
UNT 081 in Running Cr Watershed 2.0
END DESCRIPTION:
XS GIS Cut Line= 4
      2892566.95      7063245.22      2892481.31      7062578.31
      2892298.90      7062397.23      2892008.78      7062370.11
#Sta/Elev= 30
  4193.7  463.91  4243.8  461.43  4264.5  458.32  4335.1  454.94  4446.0  450.95
  4564.8  448.47  4641.7  448.98  4758.5  447.46  4800.9  448.04  4859.3  446.65
  4925.9  447.91  4943.6  445.66  4952.5  447.56  4977.2  447.73  4986.0  445.78
  4990.1  443.69  4990.6  442.89  4995.6  442.89  4996.1  443.69  5000.2  443.99
  5006.0  448.47  5007.2  449.43  5062.3  451.98  5099.2  454.69  5106.2  452.95
  5123.1  455.42  5201.6  460.57  5247.6  464.94  5304.7  466.60  5414.5  466.55
#Mann=7,-1,0
  4193.7    0.05       0  4925.9    0.16       0  4952.5    0.12       0
  4990.1    0.07       0  4996.1    0.12       0  5062.3    0.16       0
  5304.7    0.05       0
Bank Sta=4564.8,5006
Exp/Cntr=0.3,0.1

Type RM Length L Ch R = 1,540,0,0,0
BEGIN DESCRIPTION:
UNT 081 in Running Cr Watershed 1.0
END DESCRIPTION:
XS GIS Cut Line= 4
      2892726.10      7063255.41      2892720.89      7062338.73
      2892575.06      7062156.44      2892118.32      7062291.38
#Sta/Elev= 30
  3969.9  466.56  4060.3  465.09  4260.3  451.60  4370.3  447.71  4407.3  447.93
  4505.1  447.19  4618.7  446.45  4636.4  445.94  4660.3  443.45  4667.8  444.61
  4680.3  446.46  4720.3  446.74  4820.3  444.47  4840.3  446.34  4979.3  445.36
  4997.2  440.71  4997.7  439.91  5003.2  440.71  5006.6  445.29  5194.6  446.45
  5221.6  447.33  5385.9  455.46  5449.4  459.09  5454.6  457.37  5481.9  461.25
  5487.9  460.32  5521.2  462.50  5554.5  466.58  5577.8  465.63  5596.3  465.63
#Mann=11,-1,0
  3969.9    0.05       0  4407.3    0.07       0  4505.1    0.12       0
  4636.4    0.07       0  4667.8    0.12       0  4997.2    0.07       0
  5003.2    0.12       0  5221.6    0.16       0  5385.9    0.12       0
  5481.9    0.16       0  5577.8    0.05       0
Bank Sta=4618.7,5194.6
Exp/Cntr=0.3,0.1

Chan Stop Cuts=-1