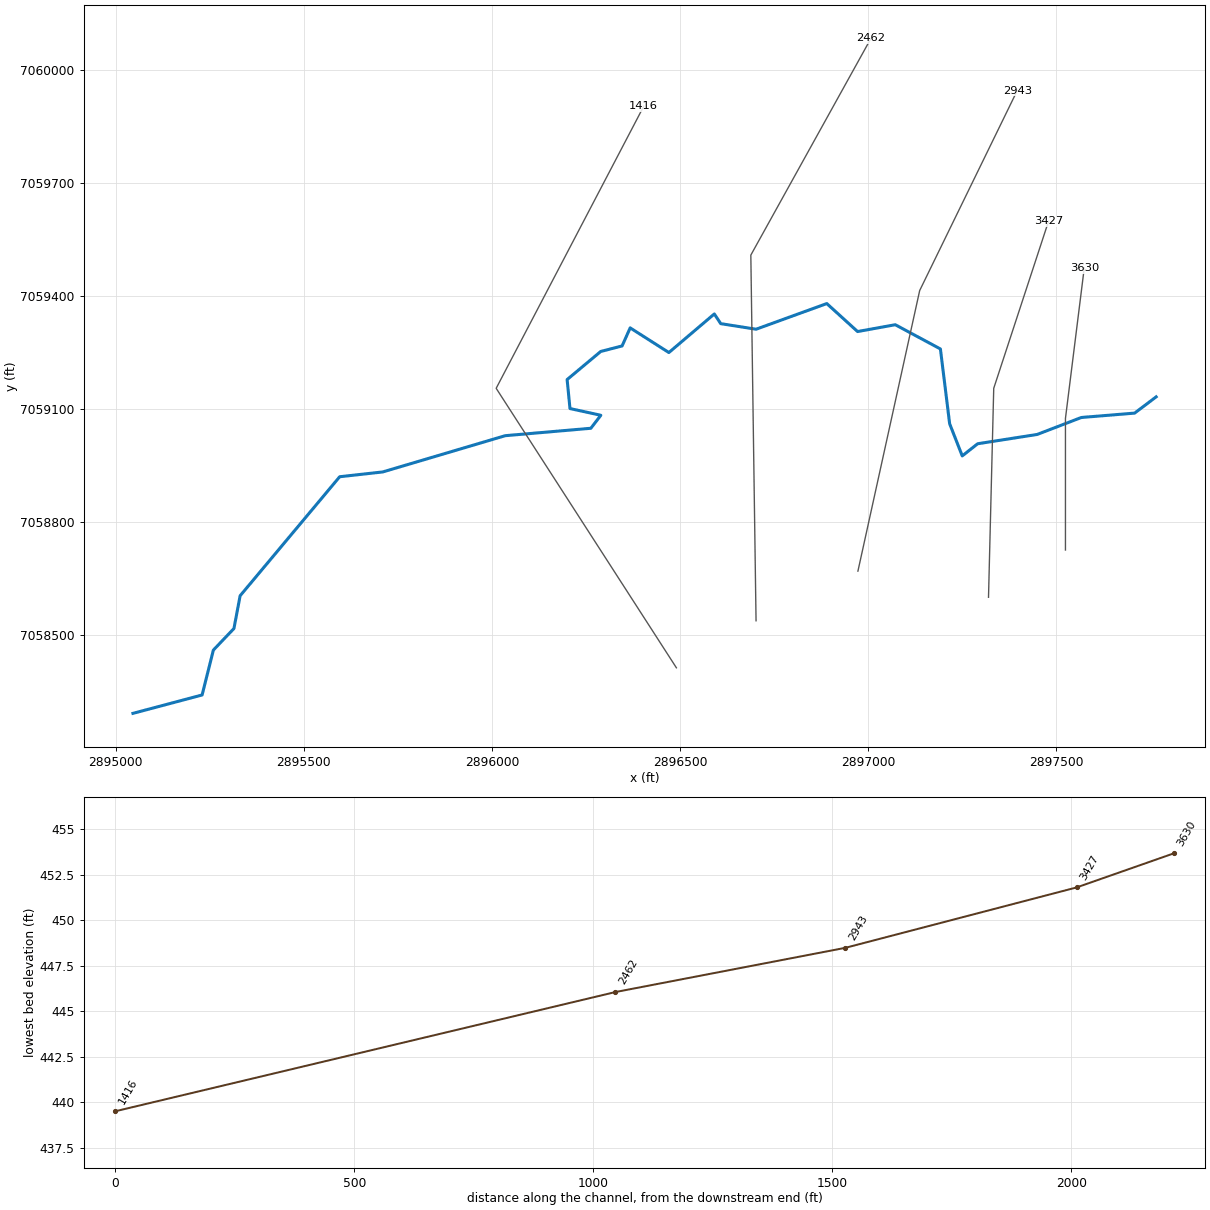
--- UNT 082 in Running Cr Watershed.prj (project) ---

Proj Title=UNT 082 in Running Cr Watershed Base Level Engineering
Current Plan=p01
Default Exp/Contr=0.3,0.1
English Units
Geom File=g01
Flow File=f01
Plan File=p01
BEGIN DESCRIPTION:
UNT 082 in Running Cr Watershed
END DESCRIPTION:

--- UNT 082 in Running Cr Watershed.p01 (plan) ---

Plan Title=Multiple Run
Short Identifier=Multiple
Geom File=g01
Flow File=f01
Subcritical Flow
K Sum by GR= 0
Std Step Tol= 0.01
Critical Tol= 0.01
Num of Std Step Trials= 20
Max Error Tol= 0.3
Flow Tol Ratio= 0.001
Split Flow NTrial= 30
Split Flow Tol= 0.02
Split Flow Ratio= 0.02
Log Output Level= 0
Friction Slope Method= 1
Unsteady Friction Slope Method= 2
Unsteady Bridges Friction Slope Method= 1
Parabolic Critical Depth
Global Vel Dist=  1 , 1 , 1
Global Log Level= 0
CheckData=True
Encroach Param= -1, 0, 0, 0
BEGIN DESCRIPTION:
Multiple Run
END DESCRIPTION:

--- UNT 082 in Running Cr Watershed.f01 (steady flow) ---

Flow Title=Multiple
Number of Profiles=7
Profile Names=10-year,25-year,50-year,1pct_min,100-year,1pct_plu,500-year
River Rch & RM= UNT 082 in Runni,Reach-1,3630
     436     574     684     406     809    1614    1133
Boundary for River Rch & Prof#=UNT 082 in Runni,Reach-1,1
Up Type=0
Dn Type=3
Dn Slope=0.005
Boundary for River Rch & Prof#=UNT 082 in Runni,Reach-1,2
Up Type=0
Dn Type=3
Dn Slope=0.005
Boundary for River Rch & Prof#=UNT 082 in Runni,Reach-1,3
Up Type=0
Dn Type=3
Dn Slope=0.005
Boundary for River Rch & Prof#=UNT 082 in Runni,Reach-1,4
Up Type=0
Dn Type=3
Dn Slope=0.005
Boundary for River Rch & Prof#=UNT 082 in Runni,Reach-1,5
Up Type=0
Dn Type=3
Dn Slope=0.005
Boundary for River Rch & Prof#=UNT 082 in Runni,Reach-1,6
Up Type=0
Dn Type=3
Dn Slope=0.005
Boundary for River Rch & Prof#=UNT 082 in Runni,Reach-1,7
Up Type=0
Dn Type=3
Dn Slope=0.005

--- UNT 082 in Running Cr Watershed.g01 (geometry) ---

Geom Title=Existing Conditions

River Reach=UNT 082 in Runni,Reach-1
Reach XY= 30
      2897766.19      7059132.27      2897708.97      7059089.08
      2897567.23      7059077.40      2897449.92      7059032.32
      2897291.55      7059007.58      2897250.62      7058975.26
      2897217.09      7059060.82      2897192.56      7059259.62
      2897072.54      7059324.08      2896972.28      7059305.93
      2896890.46      7059380.30      2896702.44      7059312.08
      2896608.42      7059326.92      2896591.42      7059352.70
      2896470.60      7059250.09      2896367.71      7059315.65
      2896346.23      7059267.65      2896289.45      7059252.94
      2896200.06      7059178.27      2896207.62      7059101.20
      2896289.69      7059083.29      2896263.10      7059048.74
      2896035.39      7059029.00      2895710.00      7058932.66
      2895595.37      7058919.90      2895330.62      7058603.40
      2895314.19      7058516.32      2895259.51      7058458.99
      2895229.56      7058339.62      2895045.59      7058290.71

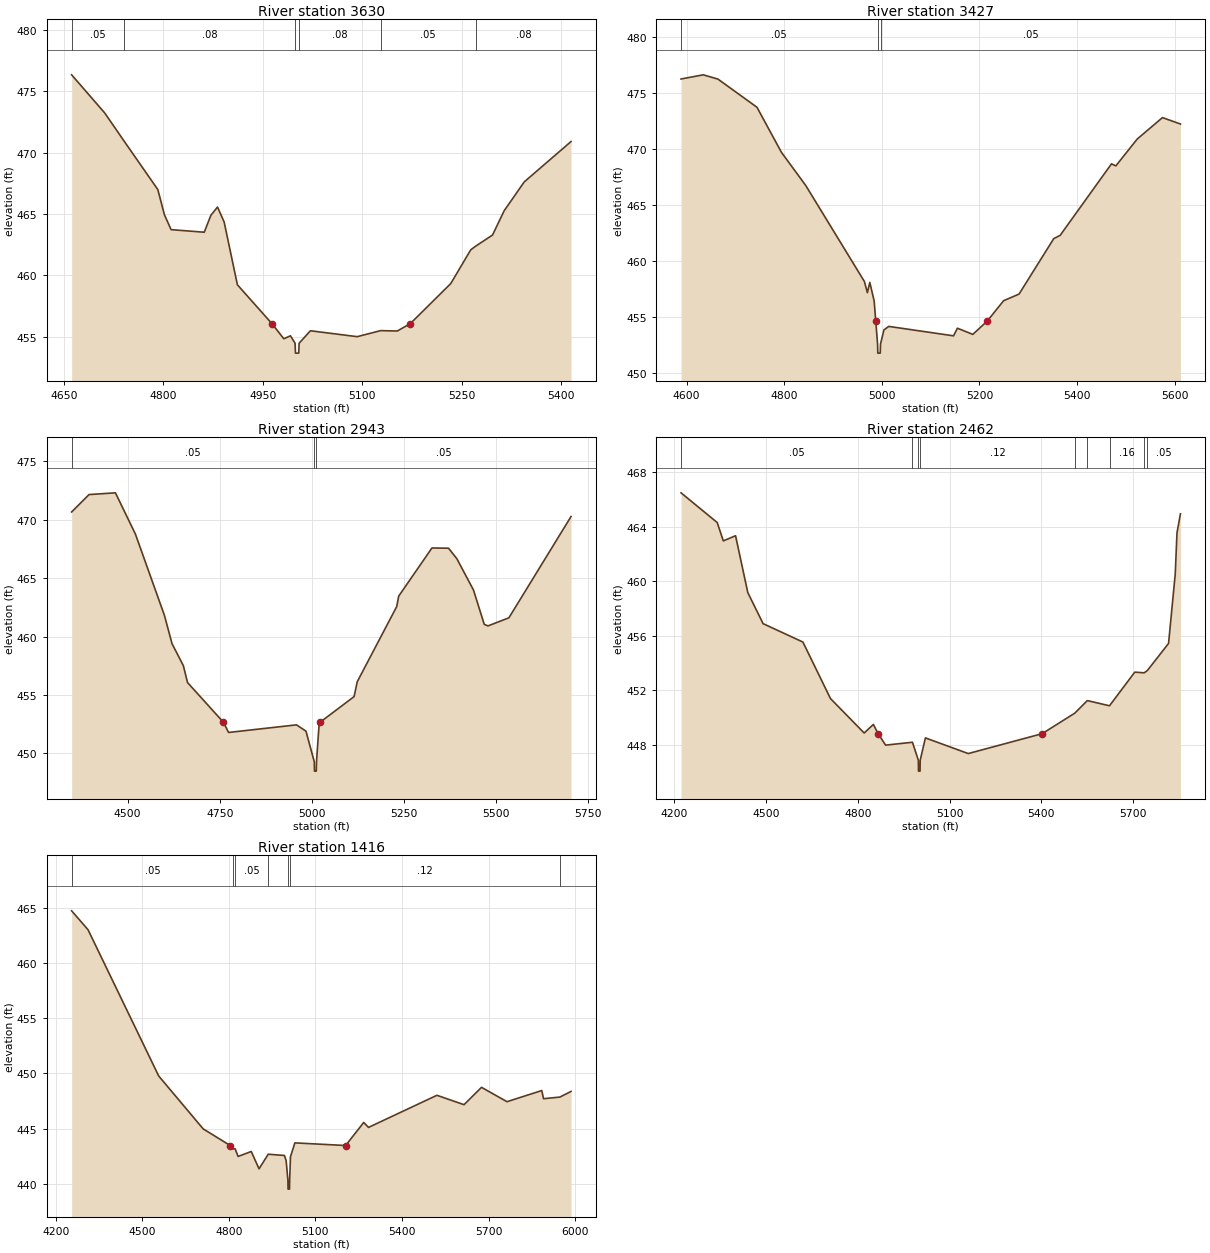
Type RM Length L Ch R = 1,3630,203,203,203
BEGIN DESCRIPTION:
UNT 082 in Running Cr Watershed 5.0
END DESCRIPTION:
XS GIS Cut Line= 3
      2897525.00      7058725.02      2897525.00      7059075.00
      2897575.00      7059475.00
#Sta/Elev= 30
  4661.6  476.33  4711.6  473.22  4739.9  471.00  4791.6  466.99  4801.6  464.93
  4811.6  463.73  4861.6  463.52  4871.6  464.90  4881.6  465.57  4891.6  464.35
  4911.6  459.24  4963.5  456.09  4981.6  454.85  4991.6  455.09  4998.6  454.48
  4999.1  453.68  5004.1  453.68  5004.6  454.48  5021.7  455.50  5092.2  455.02
  5127.5  455.51  5152.7  455.48  5172.5  456.09  5233.3  459.34  5263.5  462.09
  5271.3  462.40  5296.3  463.29  5313.9  465.27  5344.2  467.62  5414.7  470.90
#Mann=6,-1,0
  4661.6    0.05       0  4739.9    0.08       0  4998.6    0.07       0
  5004.6    0.08       0  5127.5    0.05       0  5271.3    0.08       0
Bank Sta=4963.5,5172.5
Exp/Cntr=0.3,0.1

Type RM Length L Ch R = 1,3427,484,484,484
BEGIN DESCRIPTION:
UNT 082 in Running Cr Watershed 4.0
END DESCRIPTION:
XS GIS Cut Line= 3
      2897320.43      7058599.41      2897334.32      7059154.99
      2897480.08      7059599.23
#Sta/Elev= 30
  4588.7  476.23  4634.3  476.60  4664.3  476.22  4744.3  473.71  4794.4  469.70
  4844.4  466.73  4964.4  458.19  4970.5  457.20  4975.5  458.11  4984.4  456.46
  4987.7  454.66  4991.4  452.61  4991.9  451.81  4996.9  451.81  4997.4  452.61
  5004.4  453.88  5014.4  454.19  5147.1  453.35  5155.0  454.03  5186.6  453.48
  5216.0  454.66  5249.7  456.48  5281.3  457.07  5352.4  462.01  5365.5  462.30
  5470.7  468.67  5479.7  468.49  5523.4  470.88  5575.2  472.79  5612.0  472.22
#Mann=3,-1,0
  4588.7    0.05       0  4991.4    0.03       0  4997.4    0.05       0
Bank Sta=4987.7,5216
Exp/Cntr=0.3,0.1

Type RM Length L Ch R = 1,2943,481,481,481
BEGIN DESCRIPTION:
UNT 082 in Running Cr Watershed 3.0
END DESCRIPTION:
XS GIS Cut Line= 3
      2896973.22      7058668.91      2897137.45      7059414.96
      2897396.82      7059946.66
#Sta/Elev= 30
  4348.1  470.67  4395.3  472.16  4467.0  472.31  4521.2  468.78  4600.1  461.81
  4620.6  459.40  4651.3  457.52  4662.7  456.07  4759.9  452.68  4774.1  451.80
  4958.5  452.45  4984.2  451.91  5006.7  449.29  5007.2  448.49  5012.2  448.49
  5012.7  449.29  5019.9  452.53  5022.7  452.68  5114.8  454.87  5123.3  456.14
  5230.4  462.57  5235.9  463.47  5326.1  467.59  5371.1  467.57  5393.7  466.67
  5438.7  464.00  5468.1  461.05  5478.2  460.92  5534.9  461.61  5703.6  470.28
#Mann=3,-1,0
  4348.1    0.05       0  5006.7    0.03       0  5012.7    0.05       0
Bank Sta=4759.9,5022.7
Exp/Cntr=0.3,0.1

Type RM Length L Ch R = 1,2462,1046,1046,1046
BEGIN DESCRIPTION:
UNT 082 in Running Cr Watershed 2.0
END DESCRIPTION:
XS GIS Cut Line= 3
      2896702.38      7058536.90      2896688.49      7059509.16
      2897007.91      7060085.51
#Sta/Elev= 30
  4222.9  466.50  4341.0  464.32  4361.0  462.97  4401.0  463.35  4441.0  459.17
  4491.0  456.89  4621.0  455.54  4711.0  451.39  4821.1  448.86  4851.1  449.49
  4866.7  448.81  4891.1  447.97  4978.8  448.18  4998.1  446.86  4998.6  446.06
  5003.6  446.06  5004.1  446.86  5021.1  448.50  5161.1  447.35  5402.5  448.81
  5509.2  450.32  5550.1  451.24  5622.5  450.86  5705.0  453.33  5735.8  453.28
  5746.2  453.45  5815.4  455.44  5837.2  460.53  5842.9  463.56  5854.2  464.96
#Mann=9,-1,0
  4222.9    0.05       0  4978.8    0.12       0  4998.1    0.07       0
  5004.1    0.12       0  5509.2    0.16       0  5550.1    0.12       0
  5622.5    0.16       0  5735.8    0.07       0  5746.2    0.05       0
Bank Sta=4866.7,5402.5
Exp/Cntr=0.3,0.1

Type RM Length L Ch R = 1,1416,0,0,0
BEGIN DESCRIPTION:
UNT 082 in Running Cr Watershed 1.0
END DESCRIPTION:
XS GIS Cut Line= 3
      2896490.58      7058411.91      2896011.40      7059154.99
      2896403.76      7059904.98
#Sta/Elev= 30
  4255.2  464.72  4312.0  463.01  4556.9  449.76  4711.0  444.97  4804.7  443.46
  4815.7  443.16  4821.7  443.16  4832.1  442.47  4877.6  442.92  4904.7  441.35
  4936.4  442.67  4992.5  442.56  4998.5  442.11  5004.7  440.31  5005.2  439.51
  5010.2  439.51  5010.7  440.31  5013.6  442.45  5028.8  443.70  5204.6  443.46
  5267.5  445.55  5283.9  445.10  5521.1  448.01  5615.0  447.16  5675.6  448.73
  5763.9  447.43  5884.3  448.44  5890.6  447.70  5947.4  447.85  5985.8  448.36
#Mann=7,-1,0
  4255.2    0.05       0  4815.7    0.12       0  4821.7    0.05       0
  4936.4    0.12       0  5004.7    0.07       0  5010.7    0.12       0
  5947.4    0.05       0
Bank Sta=4804.7,5204.6
Exp/Cntr=0.3,0.1

Chan Stop Cuts=-1