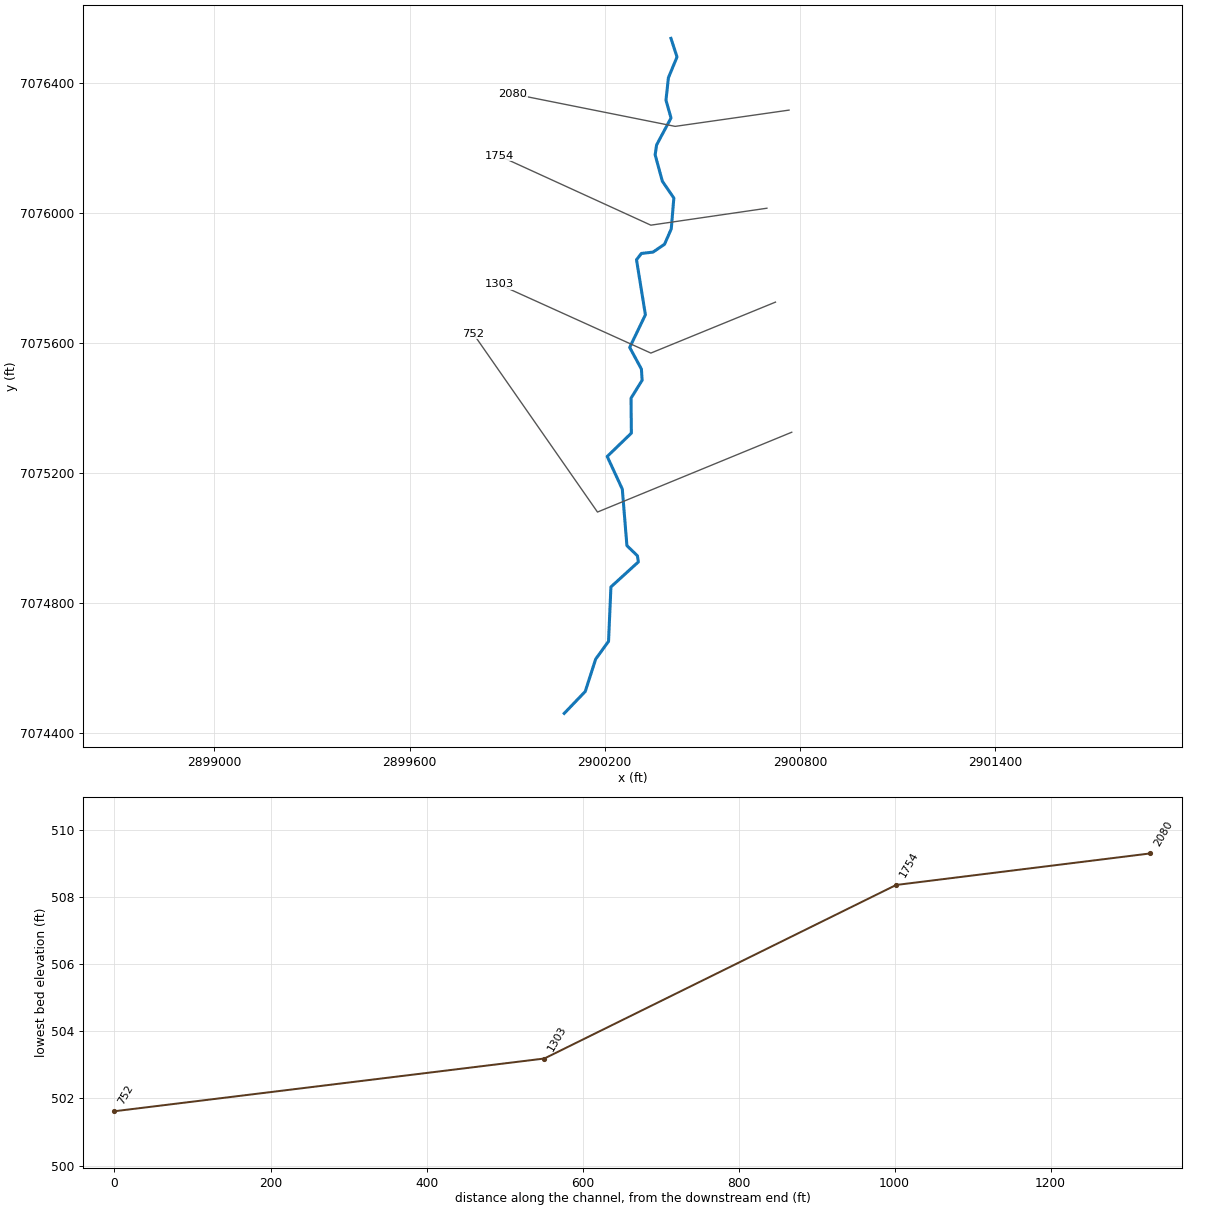
--- UNT 083 in Running Cr Watershed.prj (project) ---

Proj Title=UNT 083 in Running Cr Watershed Base Level Engineering
Current Plan=p01
Default Exp/Contr=0.3,0.1
English Units
Geom File=g01
Flow File=f01
Plan File=p01
BEGIN DESCRIPTION:
UNT 083 in Running Cr Watershed
END DESCRIPTION:

--- UNT 083 in Running Cr Watershed.p01 (plan) ---

Plan Title=Multiple Run
Short Identifier=Multiple
Geom File=g01
Flow File=f01
Subcritical Flow
K Sum by GR= 0
Std Step Tol= 0.01
Critical Tol= 0.01
Num of Std Step Trials= 20
Max Error Tol= 0.3
Flow Tol Ratio= 0.001
Split Flow NTrial= 30
Split Flow Tol= 0.02
Split Flow Ratio= 0.02
Log Output Level= 0
Friction Slope Method= 1
Unsteady Friction Slope Method= 2
Unsteady Bridges Friction Slope Method= 1
Parabolic Critical Depth
Global Vel Dist=  1 , 1 , 1
Global Log Level= 0
CheckData=True
Encroach Param= -1, 0, 0, 0
BEGIN DESCRIPTION:
Multiple Run
END DESCRIPTION:

--- UNT 083 in Running Cr Watershed.f01 (steady flow) ---

Flow Title=Multiple
Number of Profiles=7
Profile Names=10-year,25-year,50-year,1pct_min,100-year,1pct_plu,500-year
River Rch & RM= UNT 083 in Runni,Reach-1,2080
     197     241     273     154     308     615     389
Boundary for River Rch & Prof#=UNT 083 in Runni,Reach-1,1
Up Type=0
Dn Type=3
Dn Slope=0.005
Boundary for River Rch & Prof#=UNT 083 in Runni,Reach-1,2
Up Type=0
Dn Type=3
Dn Slope=0.005
Boundary for River Rch & Prof#=UNT 083 in Runni,Reach-1,3
Up Type=0
Dn Type=3
Dn Slope=0.005
Boundary for River Rch & Prof#=UNT 083 in Runni,Reach-1,4
Up Type=0
Dn Type=3
Dn Slope=0.005
Boundary for River Rch & Prof#=UNT 083 in Runni,Reach-1,5
Up Type=0
Dn Type=3
Dn Slope=0.005
Boundary for River Rch & Prof#=UNT 083 in Runni,Reach-1,6
Up Type=0
Dn Type=3
Dn Slope=0.005
Boundary for River Rch & Prof#=UNT 083 in Runni,Reach-1,7
Up Type=0
Dn Type=3
Dn Slope=0.005

--- UNT 083 in Running Cr Watershed.g01 (geometry) ---

Geom Title=Existing Conditions

River Reach=UNT 083 in Runni,Reach-1
Reach XY= 30
      2900403.66      7076535.92      2900422.32      7076478.63
      2900395.85      7076414.83      2900388.35      7076345.75
      2900403.89      7076291.02      2900359.60      7076208.38
      2900355.06      7076178.18      2900377.32      7076096.39
      2900412.54      7076045.07      2900404.70      7075950.40
      2900384.06      7075903.01      2900348.62      7075878.79
      2900312.90      7075874.60      2900297.78      7075855.28
      2900325.12      7075686.02      2900276.85      7075585.72
      2900312.80      7075519.30      2900315.05      7075484.78
      2900280.90      7075429.63      2900281.96      7075322.28
      2900207.71      7075250.50      2900254.13      7075150.12
      2900268.27      7074976.40      2900300.61      7074945.13
      2900303.53      7074926.35      2900219.12      7074849.37
      2900211.80      7074682.28      2900172.20      7074627.40
      2900140.17      7074528.00      2900075.59      7074460.71

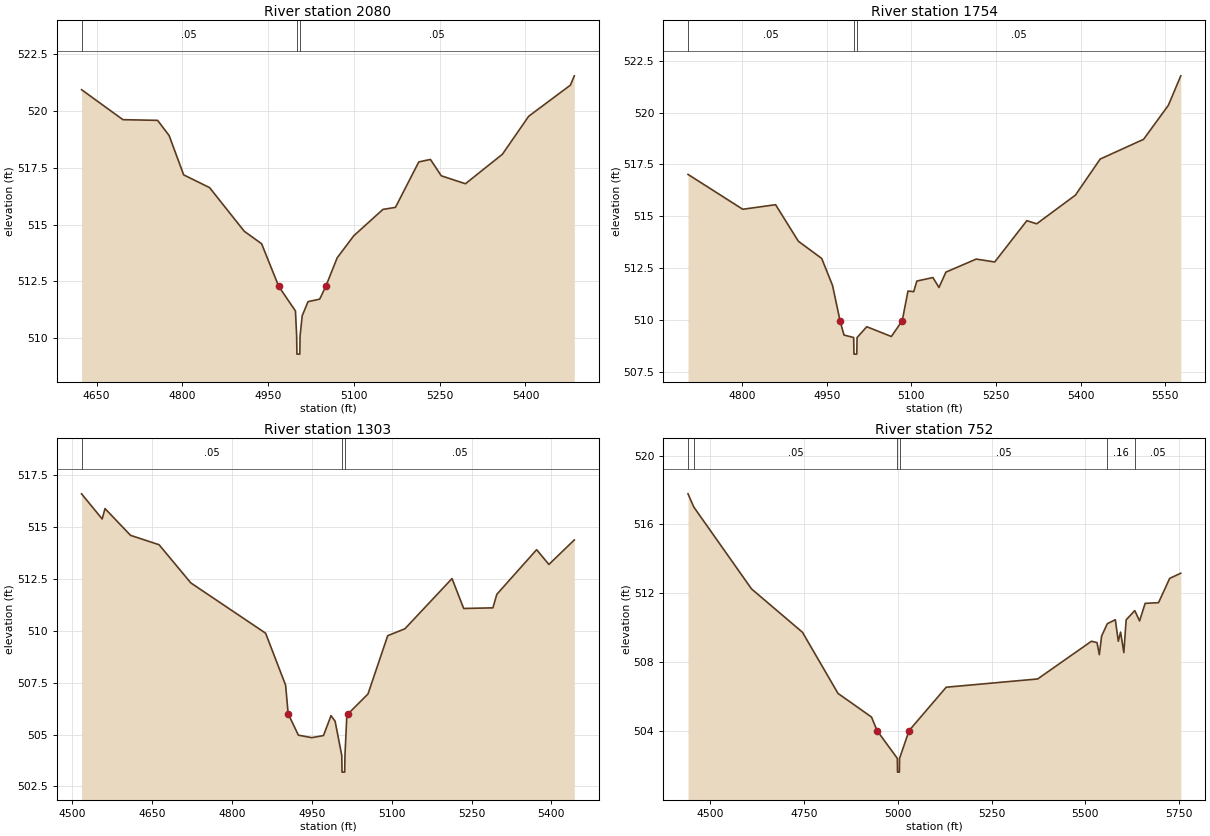
Type RM Length L Ch R = 1,2080,326,326,326
BEGIN DESCRIPTION:
UNT 083 in Running Cr Watershed 4.0
END DESCRIPTION:
XS GIS Cut Line= 3
      2900766.69      7076315.28      2900416.67      7076265.28
      2899918.31      7076364.95
#Sta/Elev= 30
  4623.6  520.94  4696.0  519.62  4756.6  519.59  4776.8  518.92  4802.2  517.19
  4847.5  516.63  4908.1  514.71  4938.5  514.16  4968.5  512.28  4997.7  511.20
  4999.8  510.10  5000.3  509.30  5005.3  509.30  5005.8  510.10  5009.5  510.99
  5019.7  511.61  5040.1  511.72  5050.7  512.28  5070.7  513.54  5099.7  514.51
  5150.7  515.67  5172.6  515.76  5213.4  517.76  5233.8  517.87  5252.7  517.15
  5295.0  516.80  5359.7  518.10  5405.6  519.77  5478.6  521.14  5485.4  521.55
#Mann=3,-1,0
  4623.6    0.05       0  4999.8    0.03       0  5005.8    0.05       0
Bank Sta=4968.5,5050.7
Exp/Cntr=0.3,0.1

Type RM Length L Ch R = 1,1754,451,451,451
BEGIN DESCRIPTION:
UNT 083 in Running Cr Watershed 3.0
END DESCRIPTION:
XS GIS Cut Line= 3
      2900698.66      7076013.65      2900341.88      7075961.56
      2899875.01      7076174.99
#Sta/Elev= 30
  4703.8  517.02  4800.9  515.34  4859.1  515.56  4899.5  513.80  4940.9  512.97
  4960.1  511.67  4973.4  509.97  4980.4  509.28  4997.6  509.16  4998.1  508.36
  5003.1  508.36  5003.6  509.16  5020.8  509.68  5064.4  509.21  5083.7  509.97
  5093.9  511.40  5104.1  511.37  5109.6  511.88  5138.1  512.05  5148.9  511.57
  5161.1  512.31  5214.9  512.94  5247.7  512.80  5304.7  514.79  5322.2  514.64
  5390.8  516.02  5434.8  517.76  5511.7  518.71  5555.7  520.35  5577.7  521.77
#Mann=3,-1,0
  4703.8    0.05       0  4997.6    0.03       0  5003.6    0.05       0
Bank Sta=4973.4,5083.7
Exp/Cntr=0.3,0.1

Type RM Length L Ch R = 1,1303,551,551,551
BEGIN DESCRIPTION:
UNT 083 in Running Cr Watershed 2.0
END DESCRIPTION:
XS GIS Cut Line= 3
      2900724.98      7075724.99      2900341.88      7075568.34
      2899875.69      7075779.29
#Sta/Elev= 30
  4517.4  516.59  4556.1  515.38  4561.5  515.88  4609.5  514.59  4663.0  514.14
  4722.7  512.30  4863.1  509.88  4900.7  507.38  4905.5  506.00  4924.7  504.97
  4949.8  504.85  4971.8  504.95  4986.0  505.91  4993.7  505.64  5006.2  503.99
  5006.7  503.19  5011.7  503.19  5012.2  503.99  5015.7  505.91  5018.2  506.00
  5055.4  506.95  5092.5  509.76  5124.7  510.09  5213.3  512.51  5235.2  511.07
  5290.1  511.10  5297.4  511.75  5372.2  513.90  5395.3  513.19  5443.0  514.37
#Mann=3,-1,0
  4517.4    0.05       0  5006.2    0.03       0  5012.2    0.05       0
Bank Sta=4905.5,5018.2
Exp/Cntr=0.3,0.1

Type RM Length L Ch R = 1,752,0,0,0
BEGIN DESCRIPTION:
UNT 083 in Running Cr Watershed 1.0
END DESCRIPTION:
XS GIS Cut Line= 3
      2900774.98      7075324.99      2900177.81      7075079.62
      2899795.86      7075628.24
#Sta/Elev= 30
  4440.2  517.78  4455.7  517.01  4609.5  512.26  4745.5  509.74  4840.2  506.19
  4929.5  504.82  4944.4  504.03  4998.4  502.42  4998.9  501.62  5003.9  501.62
  5004.4  502.42  5029.7  504.03  5128.7  506.55  5372.6  507.03  5516.1  509.22
  5531.0  509.14  5537.1  508.44  5543.2  509.52  5558.4  510.24  5579.8  510.47
  5587.7  509.22  5593.8  509.75  5602.5  508.56  5608.6  510.46  5631.6  511.00
  5644.4  510.40  5659.3  511.42  5695.0  511.46  5724.7  512.87  5754.3  513.17
#Mann=6,-1,0
  4440.2    0.08       0  4455.7    0.05       0  4998.4    0.03       0
  5004.4    0.05       0  5558.4    0.16       0  5631.6    0.05       0
Bank Sta=4944.4,5029.7
Exp/Cntr=0.3,0.1

Chan Stop Cuts=-1