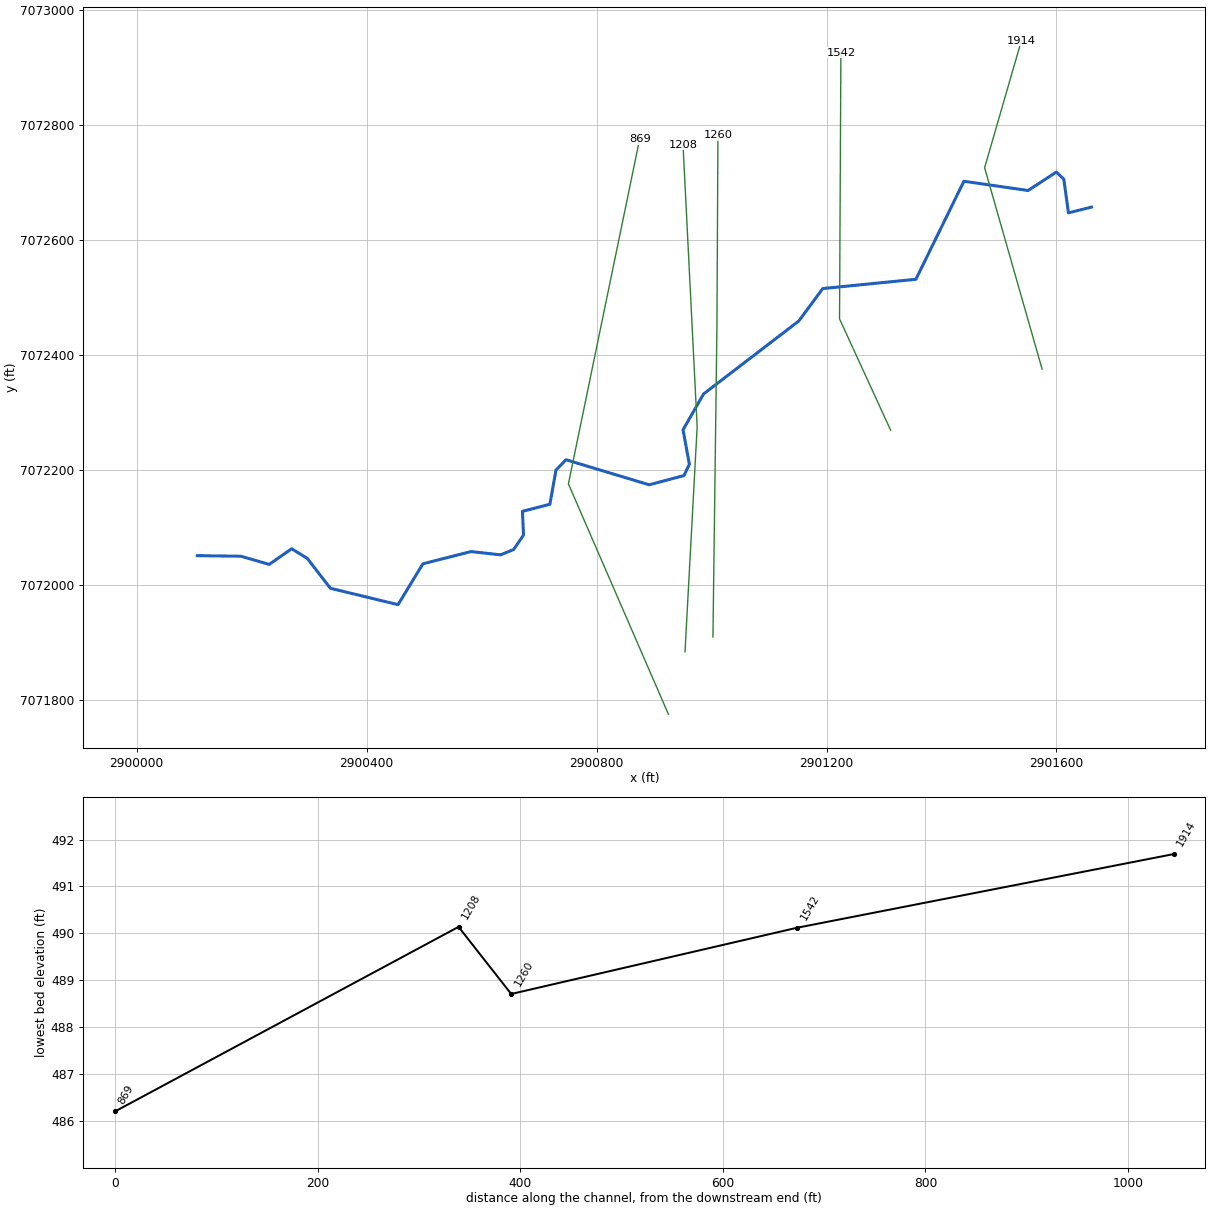
--- UNT 084 in Running Cr Watershed.prj (project) ---

Proj Title=UNT 084 in Running Cr Watershed Base Level Engineering
Current Plan=p01
Default Exp/Contr=0.3,0.1
English Units
Geom File=g01
Flow File=f01
Plan File=p01
BEGIN DESCRIPTION:
UNT 084 in Running Cr Watershed
END DESCRIPTION:

--- UNT 084 in Running Cr Watershed.p01 (plan) ---

Plan Title=Multiple Run
Short Identifier=Multiple
Geom File=g01
Flow File=f01
Subcritical Flow
K Sum by GR= 0
Std Step Tol= 0.01
Critical Tol= 0.01
Num of Std Step Trials= 20
Max Error Tol= 0.3
Flow Tol Ratio= 0.001
Split Flow NTrial= 30
Split Flow Tol= 0.02
Split Flow Ratio= 0.02
Log Output Level= 0
Friction Slope Method= 1
Unsteady Friction Slope Method= 2
Unsteady Bridges Friction Slope Method= 1
Parabolic Critical Depth
Global Vel Dist=  1 , 1 , 1
Global Log Level= 0
CheckData=True
Encroach Param= -1, 0, 0, 0
BEGIN DESCRIPTION:
Multiple Run
END DESCRIPTION:

--- UNT 084 in Running Cr Watershed.f01 (steady flow) ---

Flow Title=Multiple
Number of Profiles=7
Profile Names=10-year,25-year,50-year,1pct_min,100-year,1pct_plu,500-year
River Rch & RM= UNT 084 in Runni,Reach-1,1914
     406     524     616     360     718    1432     971
Boundary for River Rch & Prof#=UNT 084 in Runni,Reach-1,1
Up Type=0
Dn Type=3
Dn Slope=0.005
Boundary for River Rch & Prof#=UNT 084 in Runni,Reach-1,2
Up Type=0
Dn Type=3
Dn Slope=0.005
Boundary for River Rch & Prof#=UNT 084 in Runni,Reach-1,3
Up Type=0
Dn Type=3
Dn Slope=0.005
Boundary for River Rch & Prof#=UNT 084 in Runni,Reach-1,4
Up Type=0
Dn Type=3
Dn Slope=0.005
Boundary for River Rch & Prof#=UNT 084 in Runni,Reach-1,5
Up Type=0
Dn Type=3
Dn Slope=0.005
Boundary for River Rch & Prof#=UNT 084 in Runni,Reach-1,6
Up Type=0
Dn Type=3
Dn Slope=0.005
Boundary for River Rch & Prof#=UNT 084 in Runni,Reach-1,7
Up Type=0
Dn Type=3
Dn Slope=0.005

--- UNT 084 in Running Cr Watershed.g01 (geometry) ---

Geom Title=Existing Conditions

River Reach=UNT 084 in Runni,Reach-1
Reach XY= 30
      2901660.93      7072656.65      2901620.80      7072646.62
      2901612.79      7072705.00      2901599.87      7072717.63
      2901550.60      7072685.49      2901438.97      7072701.55
      2901355.50      7072531.17      2901193.44      7072515.04
      2901151.79      7072458.64      2900986.28      7072331.92
      2900950.43      7072269.61      2900961.46      7072209.60
      2900952.14      7072189.99      2900891.53      7072173.87
      2900746.89      7072217.43      2900729.46      7072199.58
      2900718.80      7072140.03      2900671.06      7072127.73
      2900673.00      7072086.50      2900655.66      7072061.23
      2900633.03      7072052.11      2900581.63      7072057.82
      2900497.95      7072036.52      2900454.69      7071965.51
      2900336.95      7071994.02      2900296.91      7072045.89
      2900269.70      7072062.69      2900230.62      7072035.49
      2900181.33      7072049.70      2900105.59      7072050.71

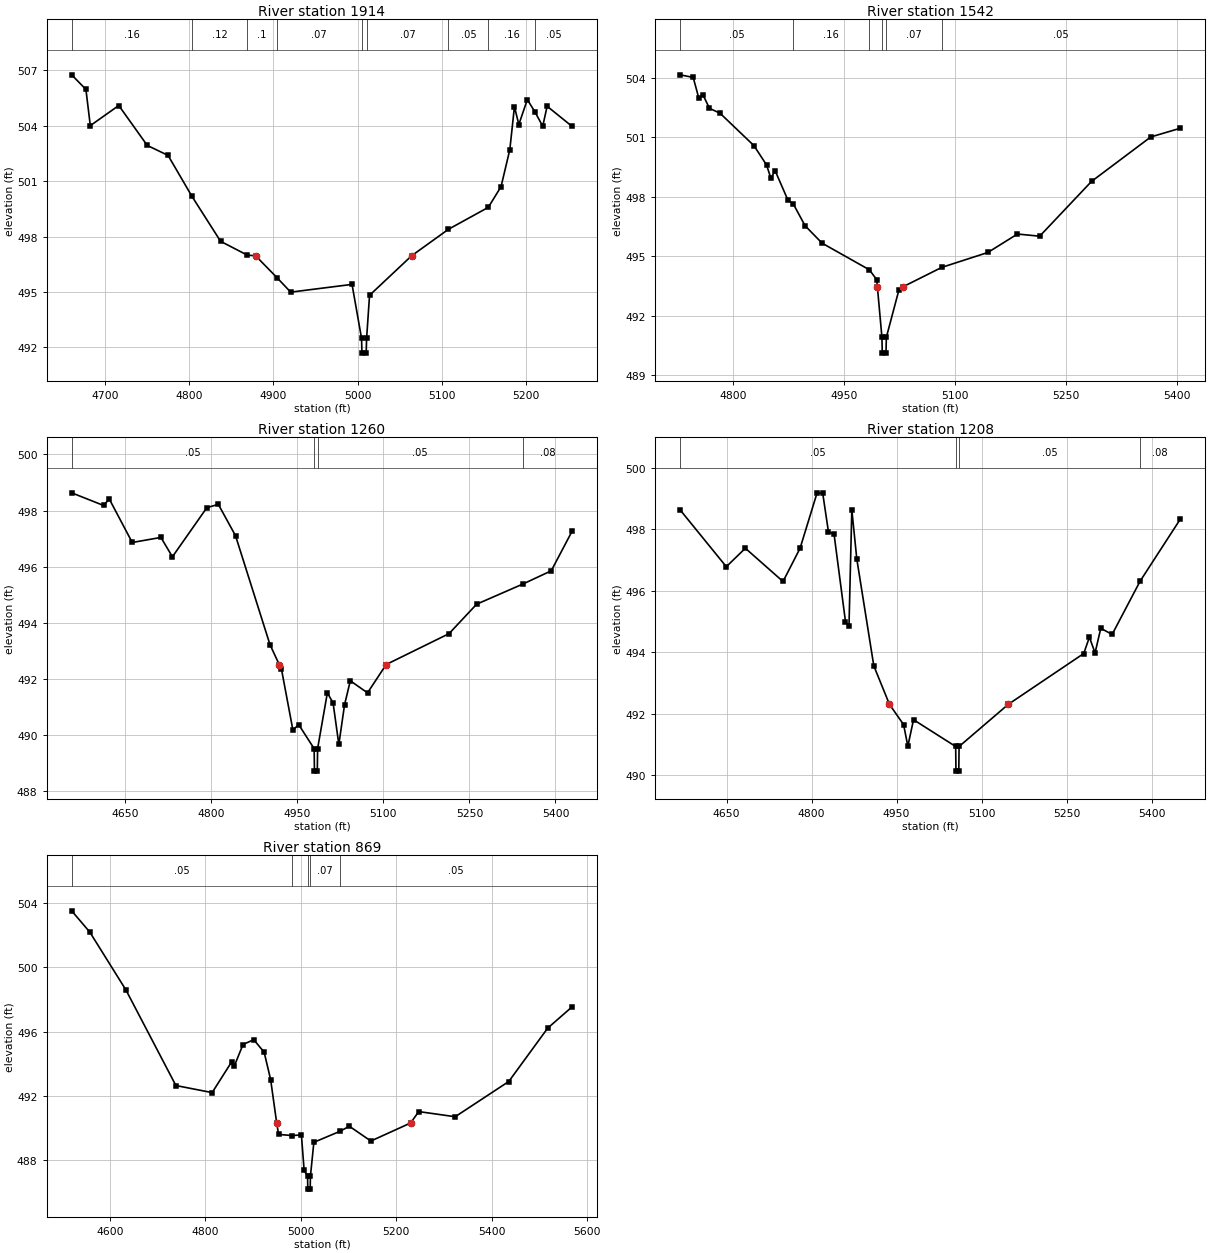
Type RM Length L Ch R = 1,1914,372,372,372
BEGIN DESCRIPTION:
UNT 084 in Running Cr Watershed 4.0
END DESCRIPTION:
XS GIS Cut Line= 3
      2901574.99      7072375.04      2901475.00      7072725.00
      2901538.93      7072945.97
#Sta/Elev= 30
  4660.5  506.75  4677.4  505.96  4682.6  504.00  4716.4  505.09  4750.2  502.93
  4774.9  502.39  4803.3  500.17  4837.3  497.74  4869.1  496.99  4878.8  496.96
  4904.3  495.77  4920.5  494.99  4993.3  495.41  5004.6  492.49  5005.1  491.69
  5010.1  491.69  5010.6  492.49  5014.1  494.82  5064.1  496.96  5107.7  498.39
  5155.1  499.58  5170.2  500.70  5180.6  502.70  5186.1  505.03  5191.3  504.06
  5201.4  505.41  5210.2  504.76  5219.7  503.97  5224.9  505.05  5254.5  503.96
#Mann=9,-1,0
  4660.5    0.16       0  4803.3    0.12       0  4869.1     0.1       0
  4904.3    0.07       0  5004.6    0.07       0  5010.6    0.07       0
  5107.7    0.05       0  5155.1    0.16       0  5210.2    0.05       0
Bank Sta=4878.8,5064.1
Exp/Cntr=0.3,0.1

Type RM Length L Ch R = 1,1542,282,282,282
BEGIN DESCRIPTION:
UNT 084 in Running Cr Watershed 3.0
END DESCRIPTION:
XS GIS Cut Line= 3
      2901311.49      7072268.86      2901222.66      7072462.28
      2901225.00      7072925.03
#Sta/Elev= 30
  4728.7  504.14  4746.5  504.01  4754.1  502.96  4759.6  503.14  4768.5  502.45
  4782.6  502.21  4828.6  500.57  4845.5  499.60  4851.5  498.92  4857.0  499.32
  4874.5  497.82  4881.6  497.64  4897.5  496.54  4920.5  495.66  4984.3  494.32
  4994.3  493.82  4995.2  493.45  5001.3  490.92  5001.8  490.12  5006.8  490.12
  5007.3  490.92  5024.3  493.31  5029.1  493.45  5082.1  494.44  5144.3  495.19
  5184.3  496.12  5214.3  496.01  5284.3  498.77  5364.3  501.01  5404.3  501.45
#Mann=6,-1,0
  4728.7    0.05       0  4881.6    0.16       0  4984.3    0.07       0
  5001.3    0.07       0  5007.3    0.07       0  5082.1    0.05       0
Bank Sta=4995.2,5029.1
Exp/Cntr=0.3,0.1

Type RM Length L Ch R = 1,1260,52,52,52
BEGIN DESCRIPTION:
Mapping XS f53cb45d
END DESCRIPTION:
XS GIS Cut Line= 3
      2901002.47      7071909.49      2901009.41      7072451.15
      2901011.14      7072781.35
#Sta/Elev= 30
  4557.0  498.63  4612.5  498.18  4622.5  498.41  4662.5  496.86  4712.5  497.04
  4732.5  496.35  4792.5  498.10  4812.5  498.22  4842.5  497.10  4902.5  493.22
  4918.6  492.51  4922.5  492.35  4942.5  490.17  4952.5  490.37  4979.5  489.51
  4980.0  488.71  4985.0  488.71  4985.5  489.51  5002.5  491.50  5012.5  491.14
  5022.5  489.66  5032.5  491.08  5042.5  491.93  5072.5  491.50  5105.0  492.51
  5214.5  493.61  5262.6  494.66  5343.3  495.38  5392.6  495.85  5428.9  497.26
#Mann=4,-1,0
  4557.0    0.05       0  4979.5    0.04       0  4985.5    0.05       0
  5343.3    0.08       0
Bank Sta=4918.6,5105
Exp/Cntr=0.3,0.1

Type RM Length L Ch R = 1,1208,339,339,339
BEGIN DESCRIPTION:
UNT 084 in Running Cr Watershed 2.0
END DESCRIPTION:
XS GIS Cut Line= 3
      2900953.86      7071883.45      2900975.00      7072275.00
      2900950.38      7072765.37
#Sta/Elev= 30
  4567.8  498.63  4649.5  496.78  4683.1  497.38  4749.6  496.30  4779.7  497.38
  4809.7  499.18  4819.7  499.16  4829.7  497.92  4839.7  497.83  4859.8  495.00
  4866.0  494.85  4871.0  498.63  4879.8  497.03  4909.8  493.56  4937.4  492.31
  4962.4  491.65  4969.9  490.95  4979.9  491.81  5054.3  490.94  5054.8  490.14
  5059.8  490.14  5060.3  490.94  5147.2  492.31  5280.3  493.96  5290.3  494.49
  5300.3  493.98  5310.4  494.78  5330.4  494.58  5379.8  496.31  5450.9  498.33
#Mann=4,-1,0
  4567.8    0.05       0  5054.3    0.04       0  5060.3    0.05       0
  5379.8    0.08       0
Bank Sta=4937.4,5147.2
Exp/Cntr=0.3,0.1

Type RM Length L Ch R = 1,869,0,0,0
BEGIN DESCRIPTION:
UNT 084 in Running Cr Watershed 1.0
END DESCRIPTION:
XS GIS Cut Line= 3
      2900925.00      7071775.00      2900751.04      7072175.49
      2900874.99      7072774.96
#Sta/Elev= 30
  4519.8  503.51  4557.7  502.19  4633.5  498.59  4738.2  492.65  4814.2  492.21
  4855.5  494.14  4860.9  493.88  4878.9  495.20  4901.4  495.50  4923.2  494.72
  4936.8  493.02  4949.5  490.32  4953.5  489.61  4982.2  489.54  5001.3  489.58
  5007.0  487.38  5014.2  487.01  5014.7  486.21  5019.7  486.21  5020.2  487.01
  5027.4  489.12  5082.6  489.81  5101.7  490.12  5146.9  489.20  5230.1  490.32
  5247.3  491.03  5323.6  490.71  5435.9  492.90  5517.6  496.22  5568.6  497.54
#Mann=5,-1,0
  4519.8    0.05       0  4982.2    0.07       0  5014.2    0.07       0
  5020.2    0.07       0  5082.6    0.05       0
Bank Sta=4949.5,5230.1
Exp/Cntr=0.3,0.1

Chan Stop Cuts=-1