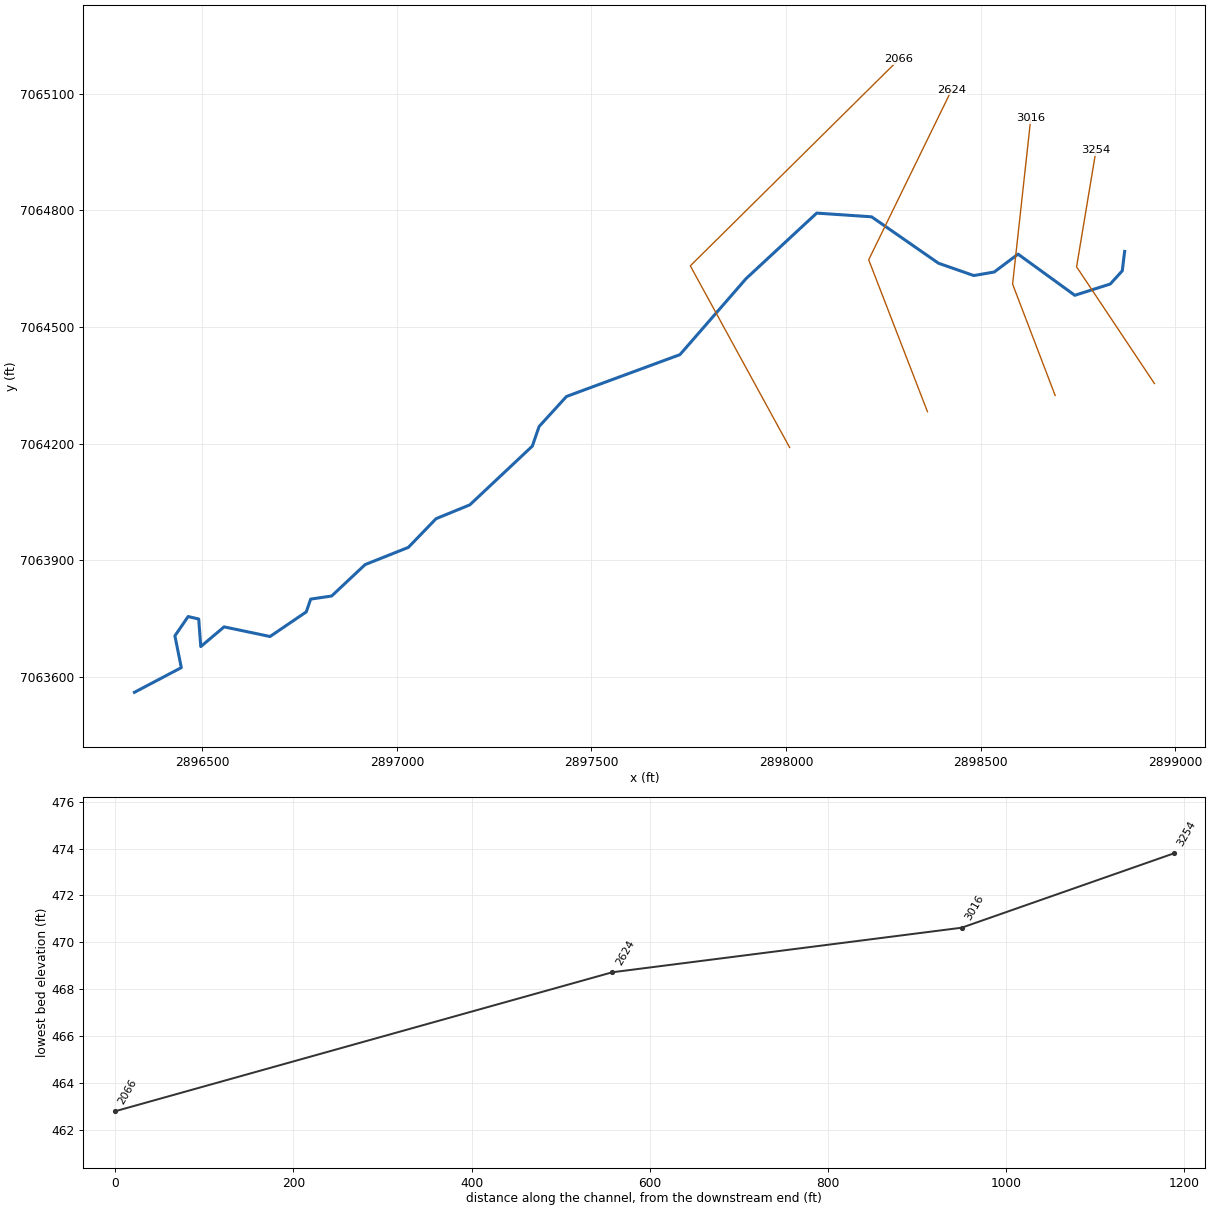
--- UNT 085 in Running Cr Watershed.prj (project) ---

Proj Title=UNT 085 in Running Cr Watershed Base Level Engineering
Current Plan=p01
Default Exp/Contr=0.3,0.1
English Units
Geom File=g01
Flow File=f01
Plan File=p01
BEGIN DESCRIPTION:
UNT 085 in Running Cr Watershed
END DESCRIPTION:

--- UNT 085 in Running Cr Watershed.p01 (plan) ---

Plan Title=Multiple Run
Short Identifier=Multiple
Geom File=g01
Flow File=f01
Subcritical Flow
K Sum by GR= 0
Std Step Tol= 0.01
Critical Tol= 0.01
Num of Std Step Trials= 20
Max Error Tol= 0.3
Flow Tol Ratio= 0.001
Split Flow NTrial= 30
Split Flow Tol= 0.02
Split Flow Ratio= 0.02
Log Output Level= 0
Friction Slope Method= 1
Unsteady Friction Slope Method= 2
Unsteady Bridges Friction Slope Method= 1
Parabolic Critical Depth
Global Vel Dist=  1 , 1 , 1
Global Log Level= 0
CheckData=True
Encroach Param= -1, 0, 0, 0
BEGIN DESCRIPTION:
Multiple Run
END DESCRIPTION:

--- UNT 085 in Running Cr Watershed.f01 (steady flow) ---

Flow Title=Multiple
Number of Profiles=7
Profile Names=10-year,25-year,50-year,1pct_min,100-year,1pct_plu,500-year
River Rch & RM= UNT 085 in Runni,Reach-1,3254
     195     239     272     155     309     616     393
Boundary for River Rch & Prof#=UNT 085 in Runni,Reach-1,1
Up Type=0
Dn Type=3
Dn Slope=0.005
Boundary for River Rch & Prof#=UNT 085 in Runni,Reach-1,2
Up Type=0
Dn Type=3
Dn Slope=0.005
Boundary for River Rch & Prof#=UNT 085 in Runni,Reach-1,3
Up Type=0
Dn Type=3
Dn Slope=0.005
Boundary for River Rch & Prof#=UNT 085 in Runni,Reach-1,4
Up Type=0
Dn Type=3
Dn Slope=0.005
Boundary for River Rch & Prof#=UNT 085 in Runni,Reach-1,5
Up Type=0
Dn Type=3
Dn Slope=0.005
Boundary for River Rch & Prof#=UNT 085 in Runni,Reach-1,6
Up Type=0
Dn Type=3
Dn Slope=0.005
Boundary for River Rch & Prof#=UNT 085 in Runni,Reach-1,7
Up Type=0
Dn Type=3
Dn Slope=0.005

--- UNT 085 in Running Cr Watershed.g01 (geometry) ---

Geom Title=Existing Conditions

River Reach=UNT 085 in Runni,Reach-1
Reach XY= 30
      2898870.01      7064694.44      2898863.93      7064644.52
      2898833.12      7064610.67      2898741.97      7064581.59
      2898596.14      7064687.49      2898534.94      7064641.48
      2898482.42      7064632.37      2898391.71      7064664.05
      2898219.84      7064783.41      2898078.78      7064792.96
      2897897.35      7064624.56      2897727.39      7064429.04
      2897435.72      7064321.40      2897365.41      7064244.15
      2897348.05      7064193.80      2897187.46      7064042.76
      2897100.65      7064007.17      2897029.47      7063933.38
      2896918.36      7063889.11      2896832.42      7063808.38
      2896778.52      7063800.40      2896767.09      7063767.48
      2896674.10      7063704.24      2896556.08      7063729.03
      2896496.11      7063678.35      2896490.81      7063749.15
      2896463.65      7063755.61      2896429.62      7063705.90
      2896446.08      7063624.20      2896325.59      7063560.71

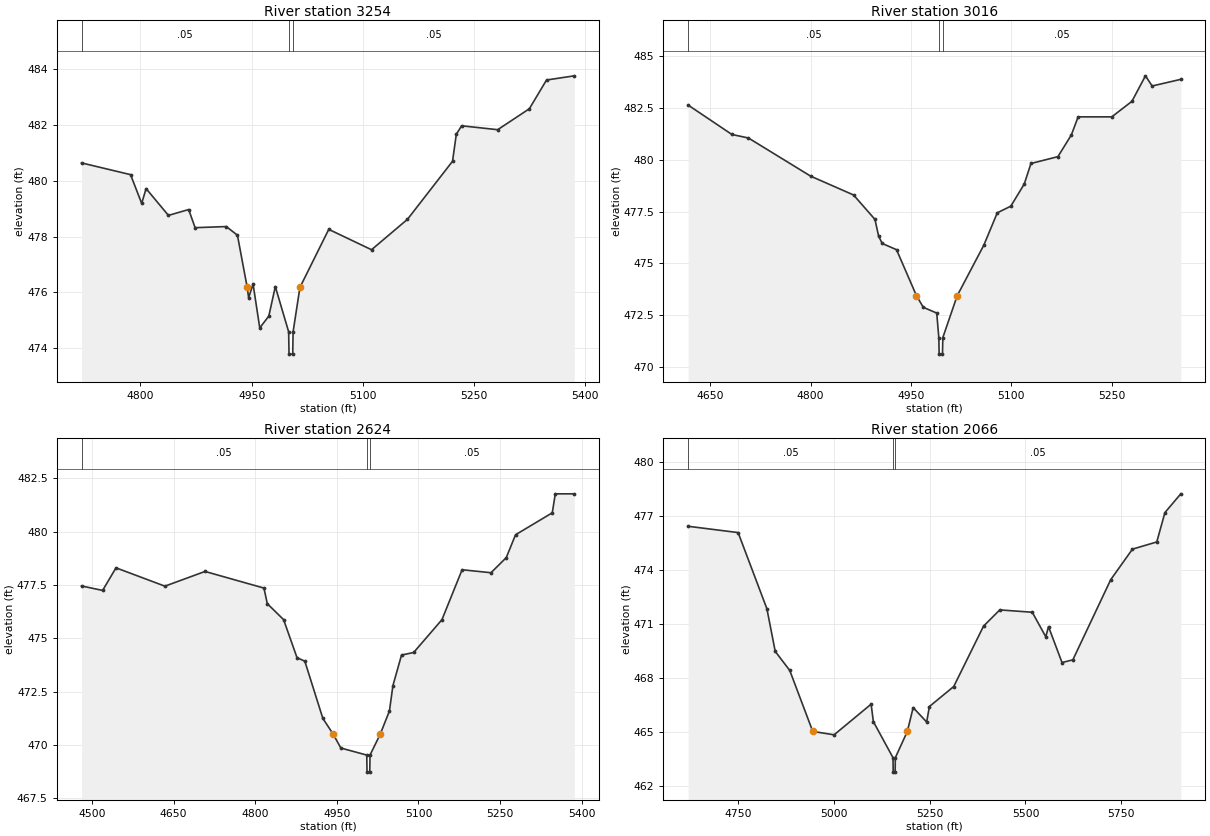
Type RM Length L Ch R = 1,3254,238,238,238
BEGIN DESCRIPTION:
UNT 085 in Running Cr Watershed 2.0
END DESCRIPTION:
XS GIS Cut Line= 3
      2898946.54      7064354.79      2898746.52      7064654.82
      2898796.51      7064954.79
#Sta/Elev= 30
  4720.5  480.64  4786.6  480.22  4801.6  479.19  4807.6  479.72  4837.7  478.76
  4865.0  478.97  4873.7  478.32  4915.8  478.36  4930.8  478.05  4944.0  476.18
  4945.9  475.81  4951.9  476.30  4960.9  474.73  4973.1  475.15  4981.9  476.21
  4999.9  474.59  5000.4  473.79  5005.4  473.79  5005.9  474.59  5015.1  476.18
  5054.0  478.26  5111.7  477.53  5160.2  478.62  5221.0  480.70  5226.1  481.67
  5233.3  481.97  5281.9  481.83  5324.6  482.58  5347.8  483.61  5385.2  483.76
#Mann=3,-1,0
  4720.5    0.05       0  4999.9    0.03       0  5005.9    0.05       0
Bank Sta=4944,5015.1
Exp/Cntr=0.3,0.1

Type RM Length L Ch R = 1,3016,392,392,392
BEGIN DESCRIPTION:
Mapping XS 6d9476cf
END DESCRIPTION:
XS GIS Cut Line= 3
      2898691.50      7064323.96      2898582.12      7064610.43
      2898629.00      7065037.53
#Sta/Elev= 30
  4616.9  482.64  4682.4  481.22  4707.1  481.05  4800.0  479.21  4864.2  478.30
  4896.2  477.12  4901.6  476.32  4907.0  475.96  4928.4  475.66  4958.2  473.44
  4968.4  472.88  4988.5  472.60  4991.6  471.42  4992.1  470.62  4997.1  470.62
  4997.6  471.42  5019.1  473.44  5058.9  475.88  5079.0  477.44  5099.2  477.76
  5119.3  478.83  5129.3  479.82  5169.6  480.15  5189.7  481.20  5199.8  482.07
  5250.1  482.07  5280.2  482.82  5300.4  484.05  5310.4  483.56  5353.2  483.88
#Mann=3,-1,0
  4616.9    0.05       0  4991.6    0.03       0  4997.6    0.05       0
Bank Sta=4958.2,5019.1
Exp/Cntr=0.3,0.1

Type RM Length L Ch R = 1,2624,558,558,558
BEGIN DESCRIPTION:
Mapping XS 773e61a4
END DESCRIPTION:
XS GIS Cut Line= 3
      2898363.37      7064282.31      2898212.33      7064672.93
      2898425.77      7065110.22
#Sta/Elev= 30
  4480.9  477.45  4519.6  477.24  4544.2  478.30  4634.1  477.44  4707.8  478.13
  4816.1  477.35  4822.2  476.62  4852.2  475.87  4876.8  474.09  4891.2  473.92
  4924.3  471.24  4943.3  470.50  4957.4  469.85  5005.0  469.52  5005.5  468.72
  5010.5  468.72  5011.0  469.52  5029.8  470.50  5046.7  471.59  5053.1  472.78
  5068.9  474.21  5091.2  474.33  5143.2  475.87  5180.2  478.21  5233.3  478.07
  5261.4  478.78  5278.4  479.85  5345.9  480.88  5351.5  481.77  5386.3  481.77
#Mann=3,-1,0
  4480.9    0.05       0  5005.0    0.03       0  5011.0    0.05       0
Bank Sta=4943.3,5029.8
Exp/Cntr=0.3,0.1

Type RM Length L Ch R = 1,2066,0,0,0
BEGIN DESCRIPTION:
UNT 085 in Running Cr Watershed 1.0
END DESCRIPTION:
XS GIS Cut Line= 3
      2898009.19      7064190.31      2897754.00      7064657.31
      2898290.26      7065188.36
#Sta/Elev= 30
  4618.7  476.43  4749.4  476.08  4824.5  471.86  4846.3  469.49  4884.3  468.43
  4944.3  465.05  5000.1  464.86  5096.8  466.56  5102.7  465.59  5154.0  463.59
  5154.5  462.79  5159.5  462.79  5160.0  463.59  5191.4  465.05  5206.6  466.37
  5241.9  465.57  5249.0  466.43  5312.6  467.54  5390.4  470.89  5432.8  471.79
  5517.7  471.66  5553.0  470.30  5560.1  470.86  5595.4  468.87  5623.7  469.02
  5722.7  473.47  5779.3  475.16  5842.9  475.56  5864.2  477.19  5905.6  478.23
#Mann=3,-1,0
  4618.7    0.05       0  5154.0    0.03       0  5160.0    0.05       0
Bank Sta=4944.3,5191.4
Exp/Cntr=0.3,0.1

Chan Stop Cuts=-1