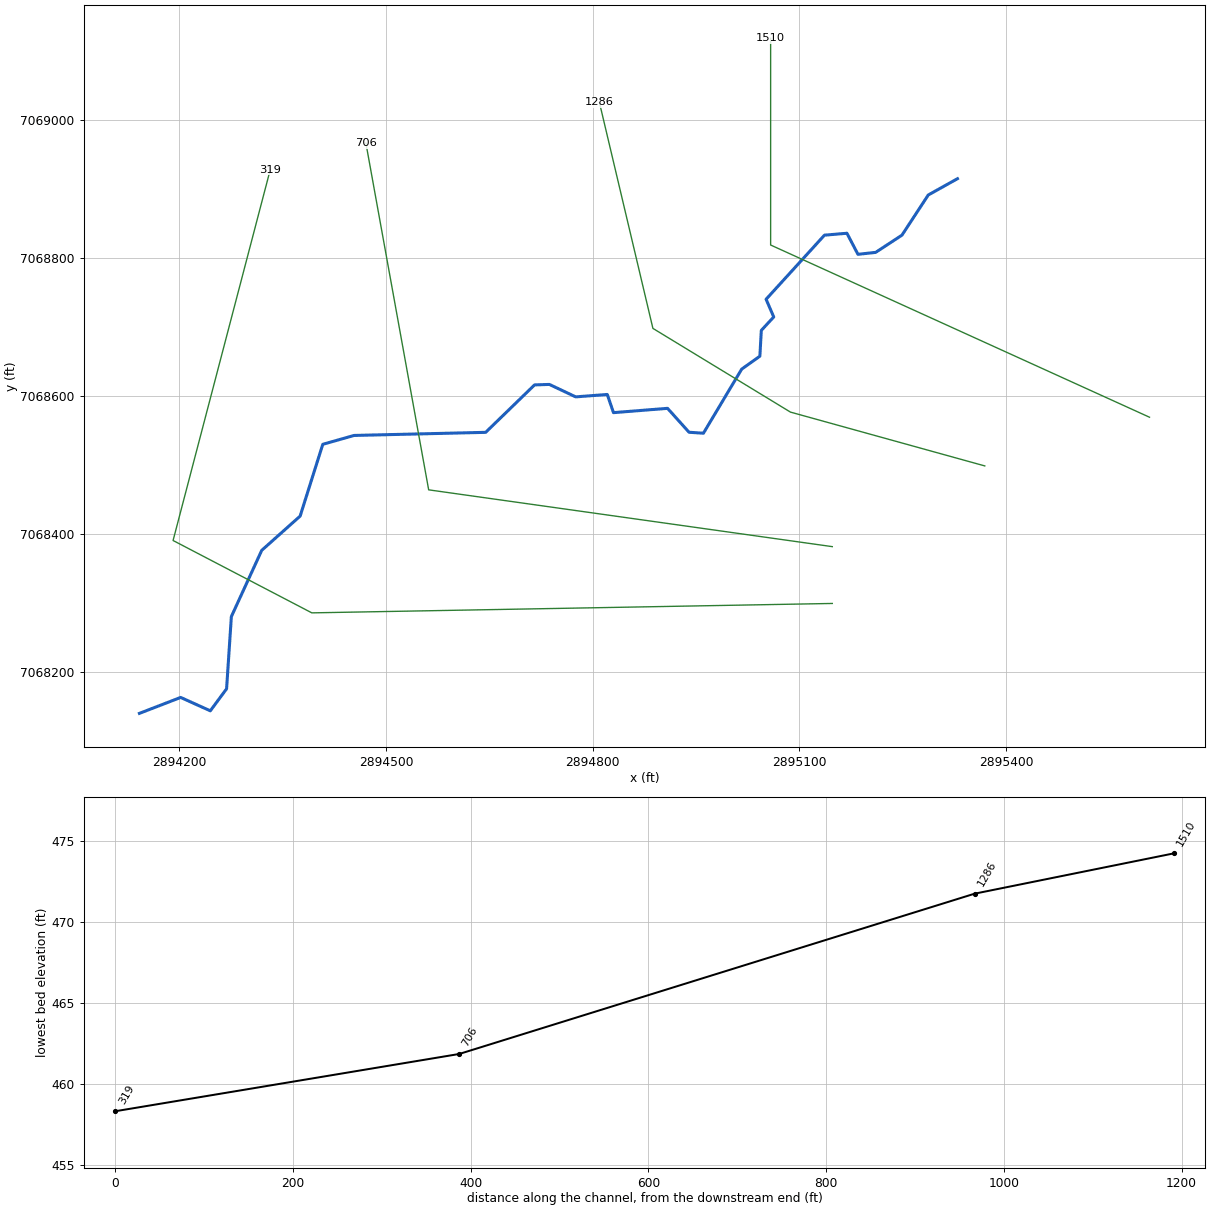
--- UNT 086 in Running Cr Watershed.prj (project) ---

Proj Title=UNT 086 in Running Cr Watershed Base Level Engineering
Current Plan=p01
Default Exp/Contr=0.3,0.1
English Units
Geom File=g01
Flow File=f01
Plan File=p01
BEGIN DESCRIPTION:
UNT 086 in Running Cr Watershed
END DESCRIPTION:

--- UNT 086 in Running Cr Watershed.p01 (plan) ---

Plan Title=Multiple Run
Short Identifier=Multiple
Geom File=g01
Flow File=f01
Subcritical Flow
K Sum by GR= 0
Std Step Tol= 0.01
Critical Tol= 0.01
Num of Std Step Trials= 20
Max Error Tol= 0.3
Flow Tol Ratio= 0.001
Split Flow NTrial= 30
Split Flow Tol= 0.02
Split Flow Ratio= 0.02
Log Output Level= 0
Friction Slope Method= 1
Unsteady Friction Slope Method= 2
Unsteady Bridges Friction Slope Method= 1
Parabolic Critical Depth
Global Vel Dist=  1 , 1 , 1
Global Log Level= 0
CheckData=True
Encroach Param= -1, 0, 0, 0
BEGIN DESCRIPTION:
Multiple Run
END DESCRIPTION:

--- UNT 086 in Running Cr Watershed.f01 (steady flow) ---

Flow Title=Multiple
Number of Profiles=7
Profile Names=10-year,25-year,50-year,1pct_min,100-year,1pct_plu,500-year
River Rch & RM= UNT 086 in Runni,Reach-1,1510
     131     156     173      97     193     385     236
Boundary for River Rch & Prof#=UNT 086 in Runni,Reach-1,1
Up Type=0
Dn Type=3
Dn Slope=0.005
Boundary for River Rch & Prof#=UNT 086 in Runni,Reach-1,2
Up Type=0
Dn Type=3
Dn Slope=0.005
Boundary for River Rch & Prof#=UNT 086 in Runni,Reach-1,3
Up Type=0
Dn Type=3
Dn Slope=0.005
Boundary for River Rch & Prof#=UNT 086 in Runni,Reach-1,4
Up Type=0
Dn Type=3
Dn Slope=0.005
Boundary for River Rch & Prof#=UNT 086 in Runni,Reach-1,5
Up Type=0
Dn Type=3
Dn Slope=0.005
Boundary for River Rch & Prof#=UNT 086 in Runni,Reach-1,6
Up Type=0
Dn Type=3
Dn Slope=0.005
Boundary for River Rch & Prof#=UNT 086 in Runni,Reach-1,7
Up Type=0
Dn Type=3
Dn Slope=0.005

--- UNT 086 in Running Cr Watershed.g01 (geometry) ---

Geom Title=Existing Conditions

River Reach=UNT 086 in Runni,Reach-1
Reach XY= 30
      2895329.43      7068915.36      2895287.07      7068891.75
      2895248.87      7068833.42      2895210.68      7068808.42
      2895184.98      7068805.64      2895169.01      7068836.19
      2895136.37      7068833.42      2895051.65      7068740.36
      2895062.76      7068714.67      2895044.71      7068695.22
      2895042.62      7068657.72      2895016.23      7068638.97
      2894960.68      7068545.92      2894939.85      7068547.30
      2894908.60      7068582.03      2894830.12      7068575.78
      2894821.10      7068602.17      2894775.26      7068598.69
      2894737.07      7068616.75      2894715.54      7068616.05
      2894644.59      7068547.19      2894453.62      7068542.68
      2894408.13      7068529.83      2894375.23      7068425.57
      2894319.50      7068375.92      2894275.41      7068279.74
      2894268.46      7068174.88      2894244.85      7068142.94
      2894201.80      7068162.38      2894141.97      7068139.23

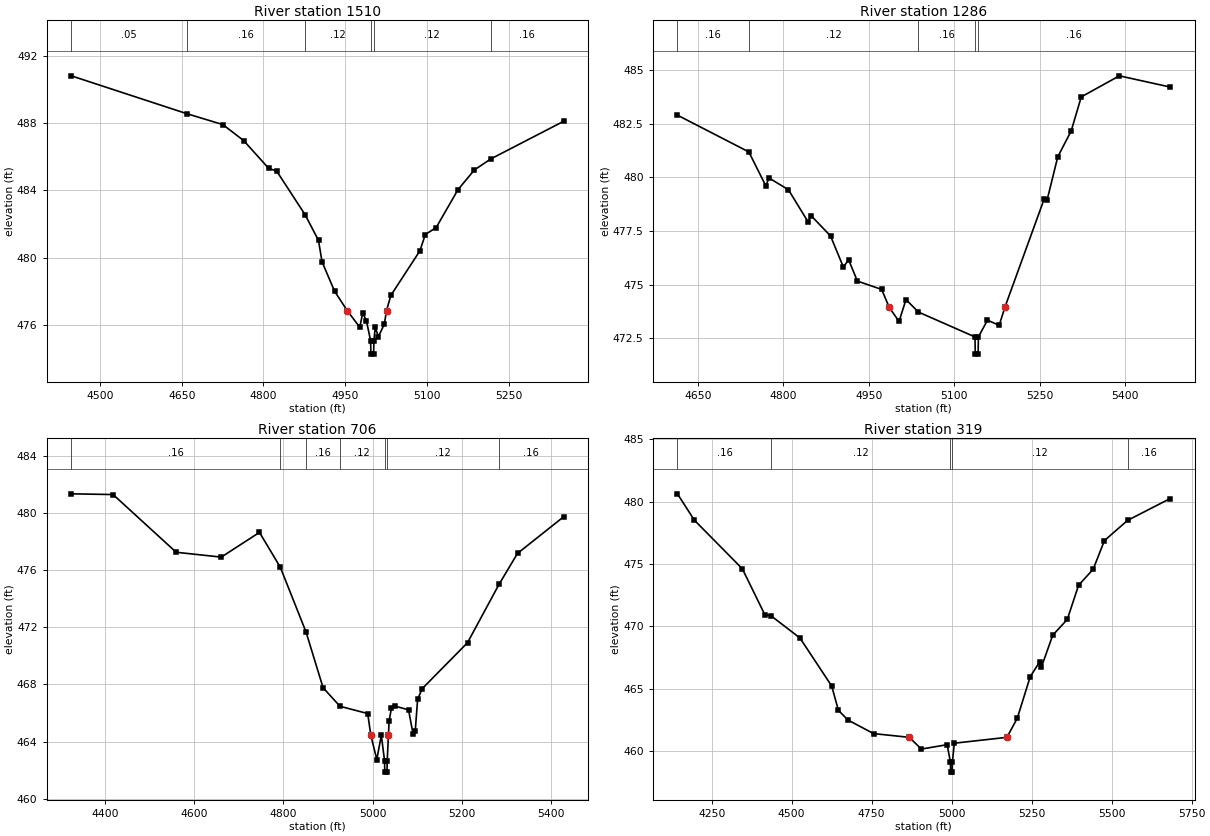
Type RM Length L Ch R = 1,1510,224,224,224
BEGIN DESCRIPTION:
UNT 086 in Running Cr Watershed 2.0
END DESCRIPTION:
XS GIS Cut Line= 3
      2895608.25      7068569.11      2895058.24      7068819.12
      2895058.24      7069119.15
#Sta/Elev= 30
  4447.1  490.81  4659.1  488.56  4725.3  487.91  4763.6  486.96  4809.7  485.30
  4824.1  485.15  4876.6  482.54  4901.0  481.02  4907.5  479.75  4930.5  478.00
  4953.7  476.85  4976.7  475.86  4982.2  476.70  4988.9  476.25  4996.7  475.06
  4997.2  474.26  5002.2  474.26  5002.7  475.06  5005.2  475.86  5010.9  475.29
  5021.9  476.05  5025.9  476.85  5033.8  477.75  5087.1  480.40  5097.1  481.37
  5117.1  481.79  5157.1  484.04  5187.1  485.21  5217.4  485.87  5351.3  488.11
#Mann=6,-1,0
  4447.1    0.05       0  4659.1    0.16       0  4876.6    0.12       0
  4996.7    0.07       0  5002.7    0.12       0  5217.4    0.16       0
Bank Sta=4953.7,5025.9
Exp/Cntr=0.3,0.1

Type RM Length L Ch R = 1,1286,580,580,580
BEGIN DESCRIPTION:
Mapping XS 8d566697
END DESCRIPTION:
XS GIS Cut Line= 4
      2895369.12      7068498.45      2895087.00      7068576.58
      2894887.35      7068698.10      2894809.61      7069026.36
#Sta/Elev= 30
  4614.2  482.89  4739.4  481.18  4769.4  479.59  4774.6  479.97  4808.9  479.42
  4843.2  477.93  4848.4  478.22  4882.7  477.27  4905.4  475.81  4914.3  476.17
  4929.8  475.17  4972.4  474.78  4985.8  473.94  5002.9  473.29  5015.1  474.31
  5036.7  473.73  5136.1  472.57  5136.6  471.77  5141.6  471.77  5142.1  472.57
  5158.0  473.35  5178.6  473.11  5188.4  473.94  5257.5  478.99  5262.6  478.94
  5281.3  480.95  5304.9  482.16  5322.5  483.74  5389.4  484.72  5478.0  484.20
#Mann=5,-1,0
  4614.2    0.16       0  4739.4    0.12       0  5036.7    0.16       0
  5136.1    0.07       0  5142.1    0.16       0
Bank Sta=4985.8,5188.4
Exp/Cntr=0.3,0.1

Type RM Length L Ch R = 1,706,387,387,387
BEGIN DESCRIPTION:
Mapping XS 30ed995e
END DESCRIPTION:
XS GIS Cut Line= 3
      2895147.73      7068381.27      2894561.83      7068463.73
      2894470.69      7068967.18
#Sta/Elev= 30
  4324.7  481.34  4418.3  481.29  4559.7  477.25  4660.7  476.91  4746.3  478.64
  4793.0  476.20  4850.7  471.66  4888.8  467.77  4926.6  466.47  4988.8  465.96
  4995.7  464.45  5009.1  462.74  5019.3  464.44  5026.5  462.66  5027.0  461.86
  5032.0  461.86  5032.5  462.66  5035.2  464.45  5036.7  465.41  5041.8  466.33
  5049.8  466.48  5080.3  466.22  5090.2  464.56  5095.3  464.75  5100.6  466.95
  5110.8  467.70  5212.4  470.92  5282.9  475.00  5324.4  477.17  5428.0  479.74
#Mann=7,-1,0
  4324.7    0.16       0  4793.0    0.12       0  4850.7    0.16       0
  4926.6    0.12       0  5026.5    0.07       0  5032.5    0.12       0
  5282.9    0.16       0
Bank Sta=4995.7,5035.2
Exp/Cntr=0.3,0.1

Type RM Length L Ch R = 1,319,0,0,0
BEGIN DESCRIPTION:
UNT 086 in Running Cr Watershed 1.0
END DESCRIPTION:
XS GIS Cut Line= 4
      2895147.77      7068298.80      2894392.22      7068285.14
      2894190.80      7068390.19      2894331.80      7068928.17
#Sta/Elev= 30
  4143.0  480.64  4195.8  478.53  4345.8  474.63  4415.8  470.96  4436.4  470.84
  4525.8  469.08  4625.2  465.22  4645.9  463.28  4675.9  462.50  4755.9  461.41
  4867.6  461.11  4905.2  460.17  4985.8  460.52  4996.2  459.12  4996.7  458.32
  5001.7  458.32  5002.2  459.12  5008.3  460.64  5172.6  461.11  5205.0  462.64
  5245.4  465.97  5275.4  467.18  5280.6  466.75  5315.8  469.30  5361.4  470.57
  5396.6  473.31  5442.2  474.59  5477.4  476.89  5549.7  478.51  5682.0  480.25
#Mann=5,-1,0
  4143.0    0.16       0  4436.4    0.12       0  4996.2    0.07       0
  5002.2    0.12       0  5549.7    0.16       0
Bank Sta=4867.6,5172.6
Exp/Cntr=0.3,0.1

Chan Stop Cuts=-1