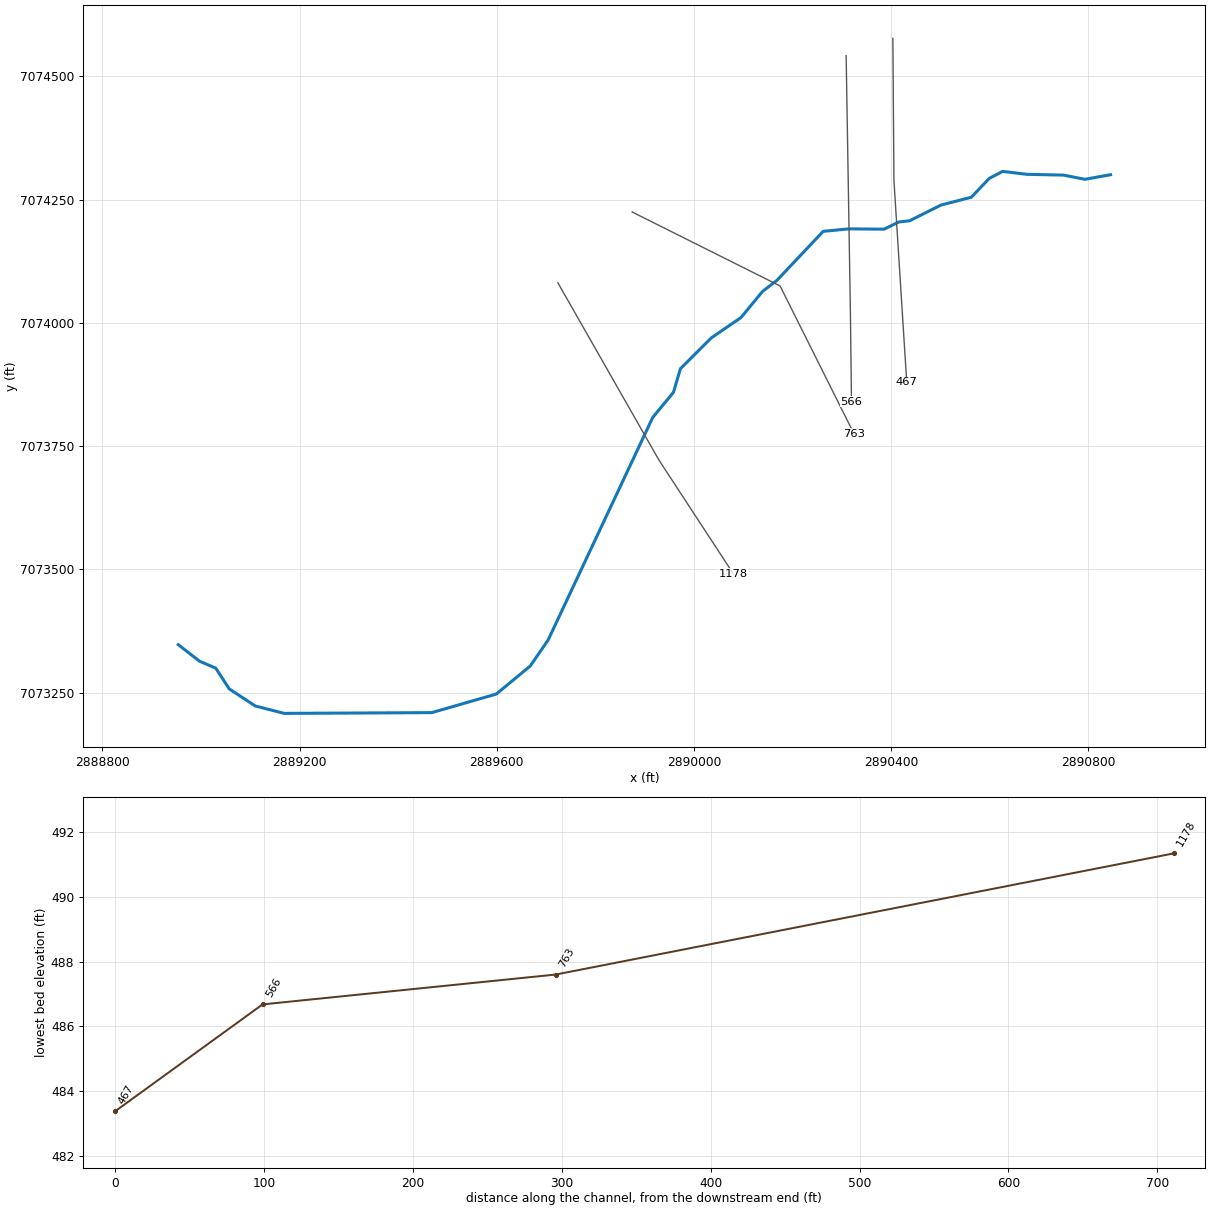
--- UNT 087 in Running Cr Watershed.prj (project) ---

Proj Title=UNT 087 in Running Cr Watershed Base Level Engineering
Current Plan=p01
Default Exp/Contr=0.3,0.1
English Units
Geom File=g01
Flow File=f01
Plan File=p01
BEGIN DESCRIPTION:
UNT 087 in Running Cr Watershed
END DESCRIPTION:

--- UNT 087 in Running Cr Watershed.p01 (plan) ---

Plan Title=Multiple Run
Short Identifier=Multiple
Geom File=g01
Flow File=f01
Subcritical Flow
K Sum by GR= 0
Std Step Tol= 0.01
Critical Tol= 0.01
Num of Std Step Trials= 20
Max Error Tol= 0.3
Flow Tol Ratio= 0.001
Split Flow NTrial= 30
Split Flow Tol= 0.02
Split Flow Ratio= 0.02
Log Output Level= 0
Friction Slope Method= 1
Unsteady Friction Slope Method= 2
Unsteady Bridges Friction Slope Method= 1
Parabolic Critical Depth
Global Vel Dist=  1 , 1 , 1
Global Log Level= 0
CheckData=True
Encroach Param= -1, 0, 0, 0
BEGIN DESCRIPTION:
Multiple Run
END DESCRIPTION:

--- UNT 087 in Running Cr Watershed.f01 (steady flow) ---

Flow Title=Multiple
Number of Profiles=7
Profile Names=10-year,25-year,50-year,1pct_min,100-year,1pct_plu,500-year
River Rch & RM= UNT 087 in Runni,Reach-1,1178
     360     462     542     317     632    1261     853
Boundary for River Rch & Prof#=UNT 087 in Runni,Reach-1,1
Up Type=0
Dn Type=3
Dn Slope=0.005
Boundary for River Rch & Prof#=UNT 087 in Runni,Reach-1,2
Up Type=0
Dn Type=3
Dn Slope=0.005
Boundary for River Rch & Prof#=UNT 087 in Runni,Reach-1,3
Up Type=0
Dn Type=3
Dn Slope=0.005
Boundary for River Rch & Prof#=UNT 087 in Runni,Reach-1,4
Up Type=0
Dn Type=3
Dn Slope=0.005
Boundary for River Rch & Prof#=UNT 087 in Runni,Reach-1,5
Up Type=0
Dn Type=3
Dn Slope=0.005
Boundary for River Rch & Prof#=UNT 087 in Runni,Reach-1,6
Up Type=0
Dn Type=3
Dn Slope=0.005
Boundary for River Rch & Prof#=UNT 087 in Runni,Reach-1,7
Up Type=0
Dn Type=3
Dn Slope=0.005

--- UNT 087 in Running Cr Watershed.g01 (geometry) ---

Geom Title=Existing Conditions

River Reach=UNT 087 in Runni,Reach-1
Reach XY= 30
      2888953.93      7073347.10      2888996.81      7073313.70
      2889030.04      7073299.39      2889057.36      7073257.36
      2889110.03      7073222.75      2889168.72      7073207.70
      2889468.17      7073209.21      2889599.09      7073246.83
      2889668.31      7073304.01      2889704.43      7073356.68
      2889916.60      7073808.12      2889958.74      7073859.28
      2889972.79      7073907.05      2890035.53      7073969.67
      2890095.64      7074010.73      2890139.37      7074063.85
      2890168.11      7074085.81      2890262.52      7074185.77
      2890314.52      7074190.84      2890386.18      7074190.21
      2890415.99      7074204.80      2890437.56      7074207.15
      2890501.27      7074239.03      2890563.20      7074255.04
      2890599.40      7074293.19      2890626.53      7074307.41
      2890675.65      7074301.52      2890750.30      7074299.90
      2890793.52      7074291.38      2890845.59      7074300.71

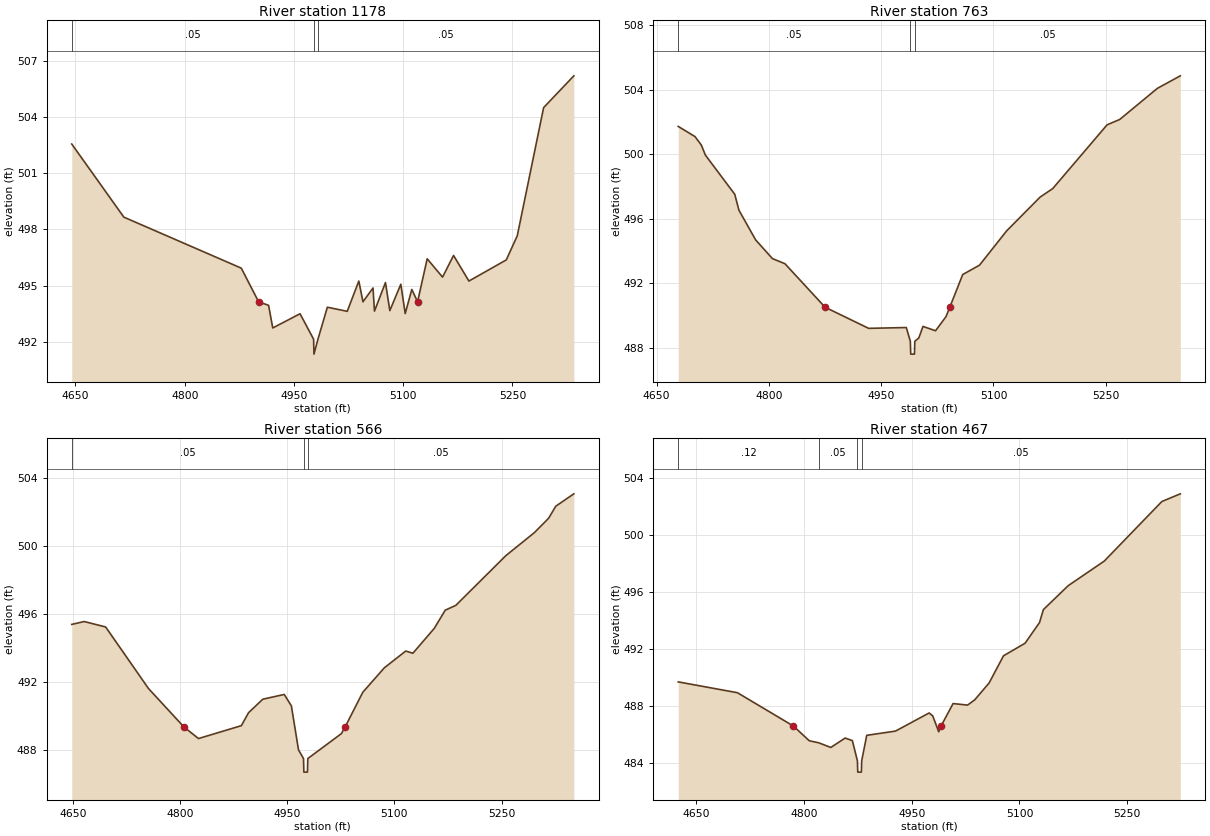
Type RM Length L Ch R = 1,1178,415,415,415
BEGIN DESCRIPTION:
UNT 087 in Running Cr Watershed 3.0
END DESCRIPTION:
XS GIS Cut Line= 3
      2889724.18      7074081.37      2889929.05      7073721.98
      2890080.04      7073491.16
#Sta/Elev= 30
  4644.9  502.57  4716.4  498.66  4877.7  495.93  4901.5  494.13  4915.2  493.94
  4920.9  492.73  4958.4  493.49  4977.0  492.13  4977.5  491.33  4983.0  492.13
  4995.9  493.84  5023.2  493.62  5039.1  495.24  5044.8  494.13  5058.6  494.87
  5060.6  493.63  5075.7  495.16  5081.7  493.66  5096.8  495.07  5102.8  493.50
  5111.9  494.79  5119.8  494.13  5133.0  496.43  5154.1  495.45  5169.2  496.61
  5190.3  495.24  5241.6  496.37  5256.7  497.66  5292.9  504.52  5334.4  506.22
#Mann=3,-1,0
  4644.9    0.05       0  4977.0    0.03       0  4983.0    0.05       0
Bank Sta=4901.5,5119.8
Exp/Cntr=0.3,0.1

Type RM Length L Ch R = 1,763,197,197,197
BEGIN DESCRIPTION:
UNT 087 in Running Cr Watershed 2.0
END DESCRIPTION:
XS GIS Cut Line= 3
      2889874.99      7074225.00      2890175.00      7074075.00
      2890324.99      7073775.02
#Sta/Elev= 30
  4678.8  501.73  4701.2  501.10  4709.6  500.58  4715.1  499.95  4754.3  497.52
  4759.9  496.53  4782.2  494.69  4804.6  493.53  4821.4  493.21  4875.0  490.51
  4933.2  489.20  4983.5  489.25  4988.9  488.40  4989.4  487.60  4994.4  487.60
  4994.9  488.40  5000.2  488.60  5005.8  489.32  5022.6  489.05  5036.6  489.93
  5041.6  490.51  5058.9  492.54  5081.3  493.12  5117.6  495.25  5162.4  497.35
  5179.1  497.87  5251.8  501.83  5268.6  502.16  5318.9  504.09  5349.6  504.87
#Mann=3,-1,0
  4678.8    0.05       0  4988.9    0.03       0  4994.9    0.05       0
Bank Sta=4875,5041.6
Exp/Cntr=0.3,0.1

Type RM Length L Ch R = 1,566,99,99,99
BEGIN DESCRIPTION:
Mapping XS 9aac886b
END DESCRIPTION:
XS GIS Cut Line= 3
      2890309.09      7074542.39      2890317.77      7074019.40
      2890319.94      7073839.68
#Sta/Elev= 30
  4648.4  495.39  4665.8  495.56  4695.8  495.24  4755.8  491.61  4805.5  489.34
  4825.8  488.66  4885.8  489.42  4895.8  490.18  4915.8  490.98  4945.8  491.26
  4955.8  490.59  4965.8  487.99  4972.8  487.48  4973.3  486.68  4978.3  486.68
  4978.8  487.48  5025.8  488.95  5031.0  489.34  5055.8  491.39  5085.9  492.83
  5115.9  493.82  5125.9  493.69  5155.9  495.16  5171.2  496.23  5185.9  496.51
  5255.9  499.44  5295.9  500.80  5315.9  501.65  5325.9  502.36  5351.2  503.09
#Mann=3,-1,0
  4648.4    0.05       0  4972.8    0.03       0  4978.8    0.05       0
Bank Sta=4805.5,5031
Exp/Cntr=0.3,0.1

Type RM Length L Ch R = 1,467,0,0,0
BEGIN DESCRIPTION:
UNT 087 in Running Cr Watershed 1.0
END DESCRIPTION:
XS GIS Cut Line= 3
      2890403.88      7074577.43      2890406.05      7074288.82
      2890432.05      7073879.36
#Sta/Elev= 30
  4625.0  489.72  4707.4  488.96  4785.4  486.62  4807.4  485.59  4820.4  485.45
  4837.4  485.12  4857.4  485.78  4867.4  485.60  4874.4  484.19  4874.9  483.39
  4879.9  483.39  4880.4  484.19  4887.4  485.97  4927.5  486.27  4974.3  487.54
  4979.3  487.33  4987.6  486.22  4990.8  486.62  5007.6  488.20  5027.7  488.09
  5037.7  488.46  5057.7  489.64  5077.8  491.55  5107.8  492.43  5127.9  493.88
  5133.3  494.79  5167.9  496.47  5218.0  498.19  5298.2  502.37  5323.9  502.91
#Mann=4,-1,0
  4625.0    0.12       0  4820.4    0.05       0  4874.4    0.03       0
  4880.4    0.05       0
Bank Sta=4785.4,4990.8
Exp/Cntr=0.3,0.1

Chan Stop Cuts=-1