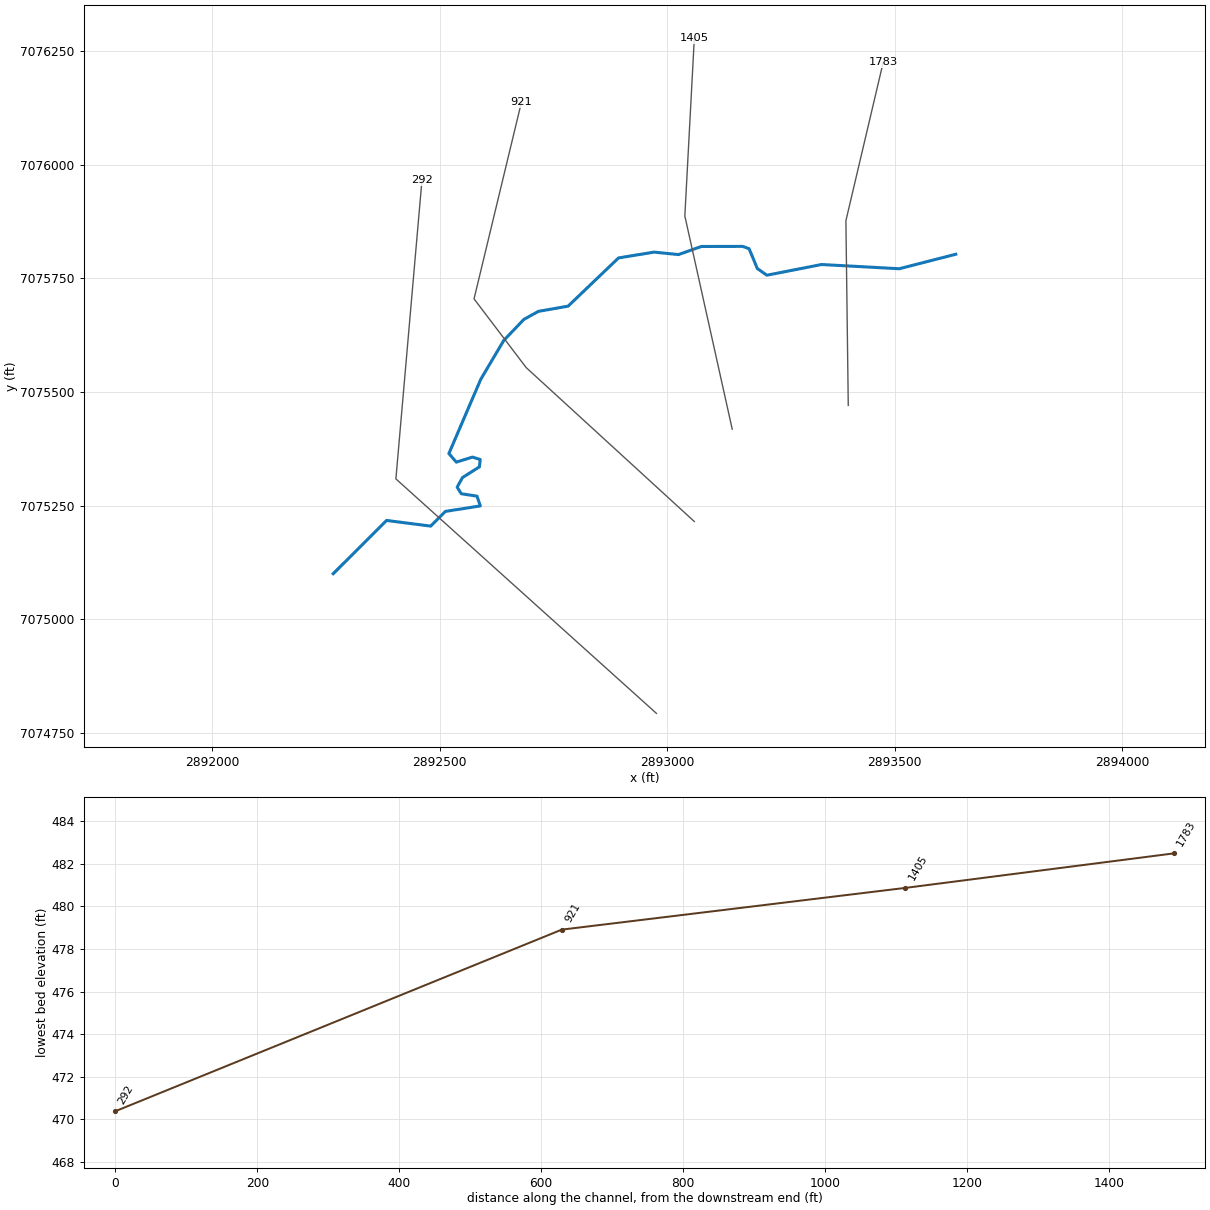
--- UNT 088 in Running Cr Watershed.prj (project) ---

Proj Title=UNT 088 in Running Cr Watershed Base Level Engineering
Current Plan=p01
Default Exp/Contr=0.3,0.1
English Units
Geom File=g01
Flow File=f01
Plan File=p01
BEGIN DESCRIPTION:
UNT 088 in Running Cr Watershed
END DESCRIPTION:

--- UNT 088 in Running Cr Watershed.p01 (plan) ---

Plan Title=Multiple Run
Short Identifier=Multiple
Geom File=g01
Flow File=f01
Subcritical Flow
K Sum by GR= 0
Std Step Tol= 0.01
Critical Tol= 0.01
Num of Std Step Trials= 20
Max Error Tol= 0.3
Flow Tol Ratio= 0.001
Split Flow NTrial= 30
Split Flow Tol= 0.02
Split Flow Ratio= 0.02
Log Output Level= 0
Friction Slope Method= 1
Unsteady Friction Slope Method= 2
Unsteady Bridges Friction Slope Method= 1
Parabolic Critical Depth
Global Vel Dist=  1 , 1 , 1
Global Log Level= 0
CheckData=True
Encroach Param= -1, 0, 0, 0
BEGIN DESCRIPTION:
Multiple Run
END DESCRIPTION:

--- UNT 088 in Running Cr Watershed.f01 (steady flow) ---

Flow Title=Multiple
Number of Profiles=7
Profile Names=10-year,25-year,50-year,1pct_min,100-year,1pct_plu,500-year
River Rch & RM= UNT 088 in Runni,Reach-1,1783
     453     585     688     402     802    1599    1084
Boundary for River Rch & Prof#=UNT 088 in Runni,Reach-1,1
Up Type=0
Dn Type=3
Dn Slope=0.005
Boundary for River Rch & Prof#=UNT 088 in Runni,Reach-1,2
Up Type=0
Dn Type=3
Dn Slope=0.005
Boundary for River Rch & Prof#=UNT 088 in Runni,Reach-1,3
Up Type=0
Dn Type=3
Dn Slope=0.005
Boundary for River Rch & Prof#=UNT 088 in Runni,Reach-1,4
Up Type=0
Dn Type=3
Dn Slope=0.005
Boundary for River Rch & Prof#=UNT 088 in Runni,Reach-1,5
Up Type=0
Dn Type=3
Dn Slope=0.005
Boundary for River Rch & Prof#=UNT 088 in Runni,Reach-1,6
Up Type=0
Dn Type=3
Dn Slope=0.005
Boundary for River Rch & Prof#=UNT 088 in Runni,Reach-1,7
Up Type=0
Dn Type=3
Dn Slope=0.005

--- UNT 088 in Running Cr Watershed.g01 (geometry) ---

Geom Title=Existing Conditions

River Reach=UNT 088 in Runni,Reach-1
Reach XY= 30
      2893634.62      7075803.17      2893510.29      7075771.31
      2893339.49      7075780.62      2893219.29      7075757.05
      2893198.22      7075771.79      2893180.20      7075815.34
      2893165.93      7075820.47      2893075.07      7075820.26
      2893024.92      7075802.44      2892971.10      7075807.88
      2892892.98      7075795.03      2892782.13      7075689.03
      2892716.86      7075677.58      2892684.96      7075659.92
      2892640.67      7075613.66      2892590.10      7075528.23
      2892520.03      7075364.98      2892536.28      7075346.11
      2892571.84      7075357.08      2892588.88      7075351.78
      2892587.15      7075335.64      2892549.78      7075312.01
      2892538.17      7075290.93      2892547.33      7075276.51
      2892581.77      7075271.25      2892589.06      7075249.76
      2892512.37      7075237.70      2892479.84      7075205.36
      2892383.01      7075217.79      2892265.59      7075100.71

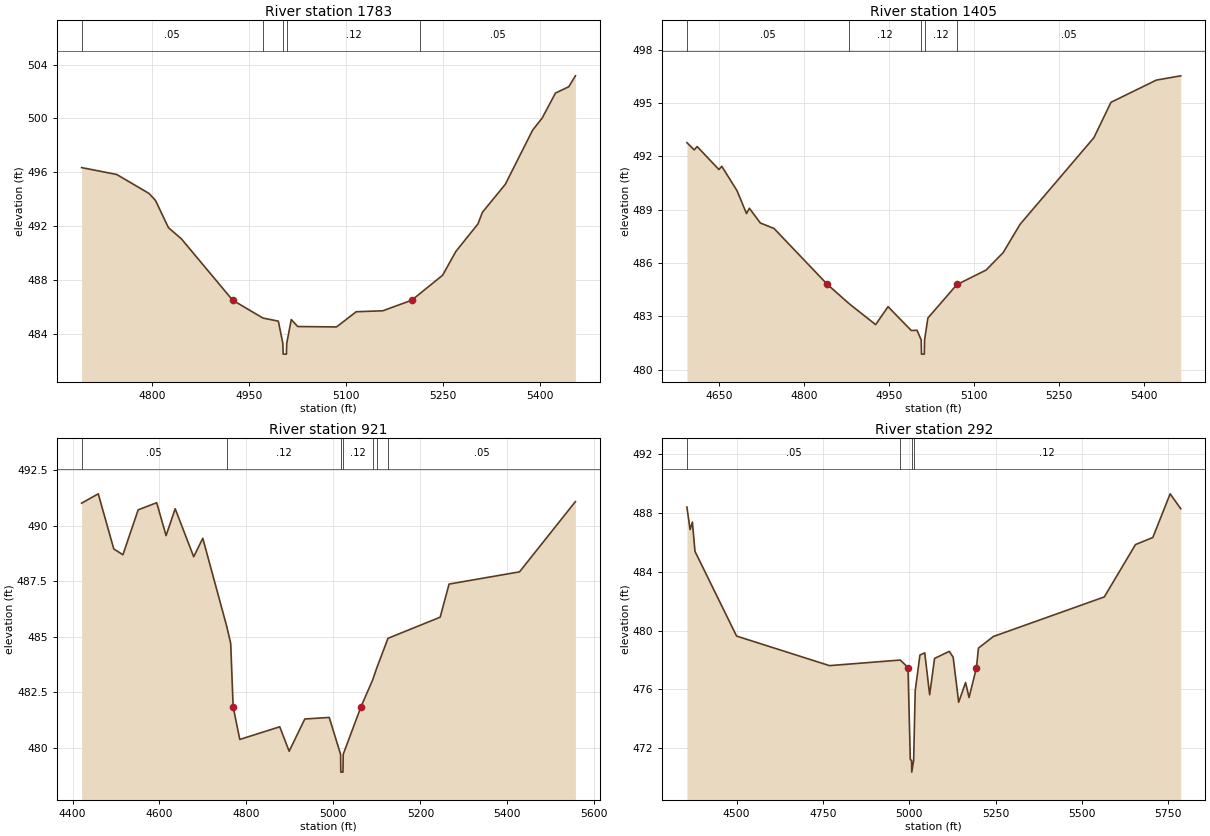
Type RM Length L Ch R = 1,1783,378,378,378
BEGIN DESCRIPTION:
UNT 088 in Running Cr Watershed 3.0
END DESCRIPTION:
XS GIS Cut Line= 3
      2893398.24      7075470.71      2893393.03      7075876.92
      2893474.99      7076224.95
#Sta/Elev= 30
  4690.7  496.35  4745.0  495.84  4795.0  494.43  4805.0  493.91  4825.0  491.89
  4845.0  491.06  4924.3  486.50  4971.2  485.17  4995.0  484.94  5002.0  483.29
  5002.5  482.49  5007.5  482.49  5008.0  483.29  5015.0  485.06  5025.0  484.54
  5085.0  484.51  5115.5  485.64  5156.6  485.71  5201.5  486.50  5214.3  487.00
  5249.1  488.35  5269.6  490.12  5303.7  492.16  5310.7  493.03  5346.1  495.11
  5388.4  499.14  5403.2  500.04  5423.7  501.89  5444.3  502.36  5454.5  503.17
#Mann=5,-1,0
  4690.7    0.05       0  4971.2    0.12       0  5002.0    0.07       0
  5008.0    0.12       0  5214.3    0.05       0
Bank Sta=4924.3,5201.5
Exp/Cntr=0.3,0.1

Type RM Length L Ch R = 1,1405,484,484,484
BEGIN DESCRIPTION:
UNT 088 in Running Cr Watershed 2.0
END DESCRIPTION:
XS GIS Cut Line= 3
      2893143.04      7075418.56      2893038.86      7075887.34
      2893059.70      7076277.97
#Sta/Elev= 30
  4593.2  492.77  4606.1  492.36  4611.2  492.55  4649.6  491.26  4654.7  491.44
  4681.7  490.06  4698.3  488.78  4703.4  489.08  4722.7  488.25  4746.9  487.94
  4841.1  484.79  4879.4  483.71  4926.2  482.53  4948.1  483.54  4989.1  482.20
  4999.3  482.21  5006.6  481.67  5007.1  480.87  5012.1  480.87  5012.6  481.67
  5018.4  482.90  5069.5  484.78  5070.2  484.79  5121.1  485.60  5151.2  486.58
  5181.2  488.18  5311.4  493.05  5341.5  495.04  5421.6  496.29  5464.6  496.53
#Mann=5,-1,0
  4593.2    0.05       0  4879.4    0.12       0  5006.6    0.07       0
  5012.6    0.12       0  5069.5    0.05       0
Bank Sta=4841.1,5070.2
Exp/Cntr=0.3,0.1

Type RM Length L Ch R = 1,921,629,629,629
BEGIN DESCRIPTION:
Mapping XS 1b9ca8af
END DESCRIPTION:
XS GIS Cut Line= 4
      2893059.66      7075215.49      2892689.90      7075554.01
      2892575.32      7075705.05      2892679.50      7076137.38
#Sta/Elev= 30
  4420.9  491.01  4459.2  491.43  4494.9  488.95  4515.9  488.69  4551.0  490.71
  4593.6  491.03  4615.2  489.55  4636.1  490.76  4678.7  488.60  4699.6  489.43
  4754.9  485.45  4763.8  484.70  4769.4  481.85  4784.7  480.38  4876.6  480.95
  4898.2  479.85  4934.2  481.30  4990.4  481.37  5016.5  479.71  5017.0  478.91
  5022.0  478.91  5022.5  479.71  5063.4  481.85  5090.3  483.06  5099.2  483.57
  5125.5  484.93  5245.5  485.88  5266.0  487.37  5428.0  487.92  5556.5  491.08
#Mann=7,-1,0
  4420.9    0.05       0  4754.9    0.12       0  5016.5    0.07       0
  5022.5    0.12       0  5090.3    0.05       0  5099.2    0.12       0
  5125.5    0.05       0
Bank Sta=4769.4,5063.4
Exp/Cntr=0.3,0.1

Type RM Length L Ch R = 1,292,0,0,0
BEGIN DESCRIPTION:
UNT 088 in Running Cr Watershed 1.0
END DESCRIPTION:
XS GIS Cut Line= 3
      2892976.40      7074793.56      2892403.45      7075309.21
      2892460.74      7075965.49
#Sta/Elev= 30
  4356.2  488.40  4365.3  486.87  4372.0  487.38  4379.5  485.39  4499.9  479.63
  4768.9  477.62  4974.0  478.00  4996.2  477.49  5002.9  471.23  5006.6  471.18
  5007.1  470.38  5012.6  471.18  5017.1  475.92  5030.8  478.34  5044.7  478.49
  5058.9  475.64  5073.1  478.11  5115.7  478.59  5127.0  478.19  5142.9  475.13
  5162.9  476.47  5173.0  475.45  5194.5  477.49  5200.2  478.81  5243.3  479.60
  5564.5  482.29  5654.8  485.85  5705.0  486.33  5755.2  489.30  5785.8  488.29
#Mann=4,-1,0
  4356.2    0.05       0  4974.0    0.12       0  5006.6    0.07       0
  5012.6    0.12       0
Bank Sta=4996.2,5194.5
Exp/Cntr=0.3,0.1

Chan Stop Cuts=-1