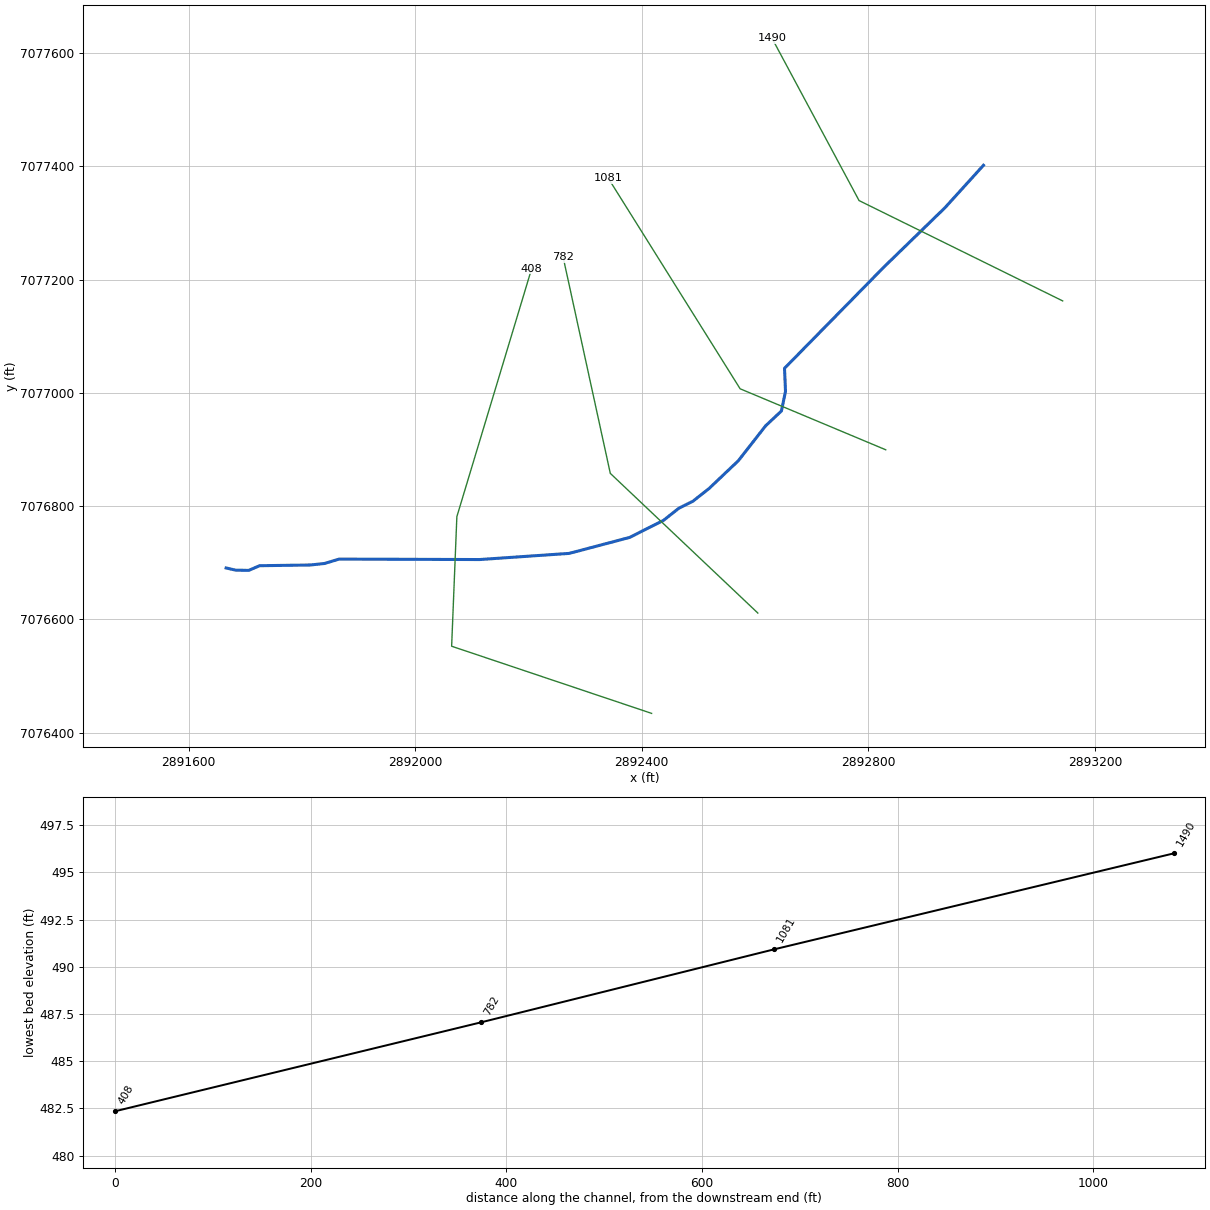
--- UNT 089 in Running Cr Watershed.prj (project) ---

Proj Title=UNT 089 in Running Cr Watershed Base Level Engineering
Current Plan=p01
Default Exp/Contr=0.3,0.1
English Units
Geom File=g01
Flow File=f01
Plan File=p01
BEGIN DESCRIPTION:
UNT 089 in Running Cr Watershed
END DESCRIPTION:

--- UNT 089 in Running Cr Watershed.p01 (plan) ---

Plan Title=Multiple Run
Short Identifier=Multiple
Geom File=g01
Flow File=f01
Subcritical Flow
K Sum by GR= 0
Std Step Tol= 0.01
Critical Tol= 0.01
Num of Std Step Trials= 20
Max Error Tol= 0.3
Flow Tol Ratio= 0.001
Split Flow NTrial= 30
Split Flow Tol= 0.02
Split Flow Ratio= 0.02
Log Output Level= 0
Friction Slope Method= 1
Unsteady Friction Slope Method= 2
Unsteady Bridges Friction Slope Method= 1
Parabolic Critical Depth
Global Vel Dist=  1 , 1 , 1
Global Log Level= 0
CheckData=True
Encroach Param= -1, 0, 0, 0
BEGIN DESCRIPTION:
Multiple Run
END DESCRIPTION:

--- UNT 089 in Running Cr Watershed.f01 (steady flow) ---

Flow Title=Multiple
Number of Profiles=7
Profile Names=10-year,25-year,50-year,1pct_min,100-year,1pct_plu,500-year
River Rch & RM= UNT 089 in Runni,Reach-1,1490
     151     181     203     114     228     454     282
Boundary for River Rch & Prof#=UNT 089 in Runni,Reach-1,1
Up Type=0
Dn Type=3
Dn Slope=0.005
Boundary for River Rch & Prof#=UNT 089 in Runni,Reach-1,2
Up Type=0
Dn Type=3
Dn Slope=0.005
Boundary for River Rch & Prof#=UNT 089 in Runni,Reach-1,3
Up Type=0
Dn Type=3
Dn Slope=0.005
Boundary for River Rch & Prof#=UNT 089 in Runni,Reach-1,4
Up Type=0
Dn Type=3
Dn Slope=0.005
Boundary for River Rch & Prof#=UNT 089 in Runni,Reach-1,5
Up Type=0
Dn Type=3
Dn Slope=0.005
Boundary for River Rch & Prof#=UNT 089 in Runni,Reach-1,6
Up Type=0
Dn Type=3
Dn Slope=0.005
Boundary for River Rch & Prof#=UNT 089 in Runni,Reach-1,7
Up Type=0
Dn Type=3
Dn Slope=0.005

--- UNT 089 in Running Cr Watershed.g01 (geometry) ---

Geom Title=Existing Conditions

River Reach=UNT 089 in Runni,Reach-1
Reach XY= 22
      2893003.05      7077401.60      2892935.34      7077326.95
      2892827.27      7077221.91      2892651.92      7077043.31
      2892653.65      7077002.51      2892646.41      7076967.88
      2892618.63      7076941.84      2892570.45      7076880.20
      2892518.80      7076831.16      2892490.16      7076808.59
      2892464.98      7076796.00      2892438.51      7076775.00
      2892378.61      7076744.79      2892271.84      7076716.58
      2892113.64      7076705.72      2891865.89      7076706.55
      2891839.85      7076698.74      2891815.11      7076696.13
      2891725.27      7076694.83      2891706.17      7076686.58
      2891683.17      7076687.02      2891666.38      7076690.85

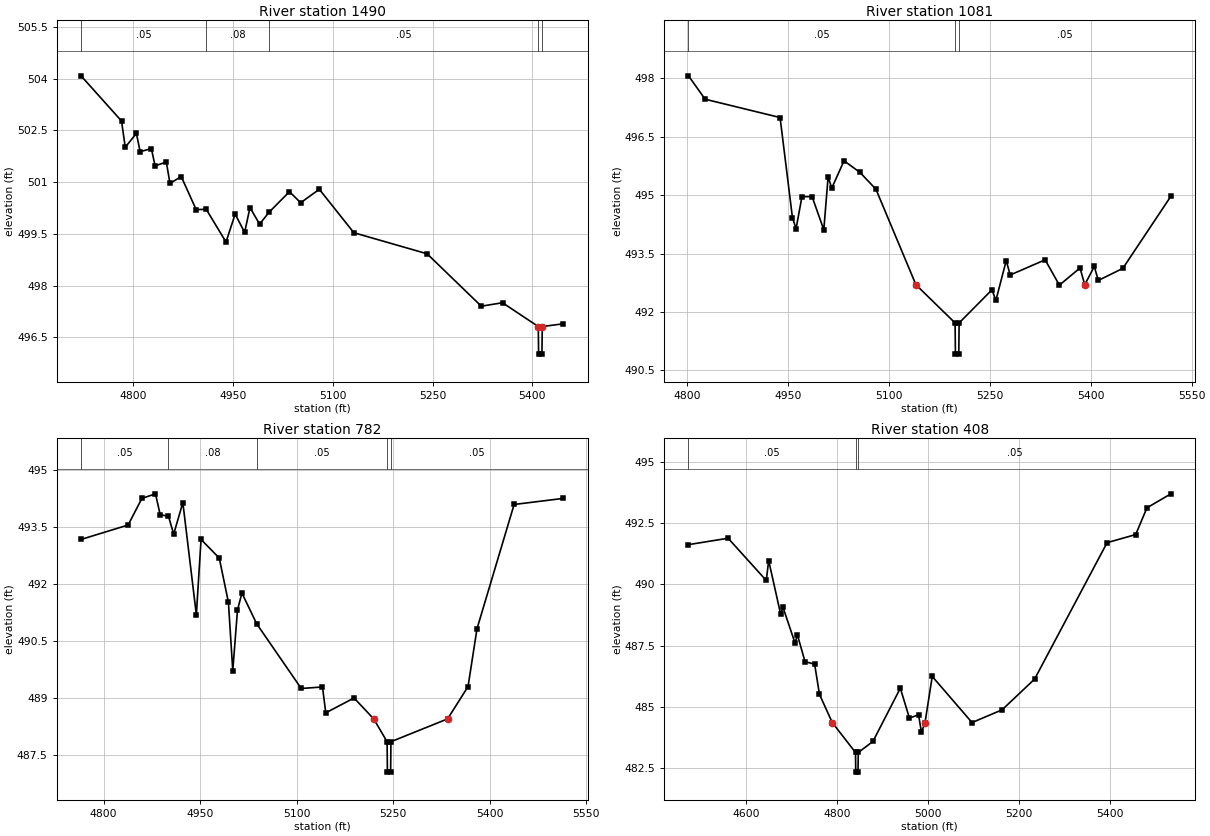
Type RM Length L Ch R = 1,1490,409,409,409
BEGIN DESCRIPTION:
UNT 089 in Running Cr Watershed 2.0
END DESCRIPTION:
XS GIS Cut Line= 3
      2893142.89      7077162.24      2892783.52      7077339.33
      2892629.91      7077625.70
#Sta/Elev= 30
  4721.1  504.08  4782.0  502.77  4787.6  502.01  4804.4  502.41  4810.0  501.88
  4826.9  501.97  4832.5  501.47  4849.4  501.58  4854.9  500.96  4871.8  501.16
  4894.3  500.20  4909.4  500.21  4939.2  499.26  4952.9  500.07  4967.2  499.54
  4975.2  500.26  4989.7  499.78  5004.2  500.13  5034.6  500.72  5051.5  500.40
  5079.5  500.79  5131.5  499.53  5241.6  498.92  5323.2  497.40  5355.1  497.50
  5408.9  496.81  5409.4  496.01  5414.4  496.01  5414.9  496.81  5446.7  496.89
#Mann=5,-1,0
  4721.1    0.05       0  4909.4    0.08       0  5004.2    0.05       0
  5408.9    0.07       0  5414.9    0.05       0
Bank Sta=5408.9,5414.9
Exp/Cntr=0.3,0.1

Type RM Length L Ch R = 1,1081,299,299,299
BEGIN DESCRIPTION:
Mapping XS 83f08b91
END DESCRIPTION:
XS GIS Cut Line= 3
      2892830.53      7076899.49      2892573.58      7077007.13
      2892340.96      7077378.63
#Sta/Elev= 30
  4802.2  498.06  4826.9  497.46  4938.3  496.99  4956.7  494.42  4962.1  494.14
  4970.8  494.96  4985.9  494.96  5003.3  494.11  5009.7  495.47  5015.1  495.18
  5033.4  495.88  5057.2  495.58  5080.8  495.15  5140.2  492.70  5198.4  491.72
  5198.9  490.92  5203.9  490.92  5204.4  491.72  5253.2  492.57  5259.1  492.30
  5274.4  493.32  5280.3  492.95  5332.2  493.34  5353.4  492.69  5384.1  493.13
  5391.1  492.70  5405.3  493.17  5411.2  492.81  5447.7  493.12  5519.1  494.97
#Mann=3,-1,0
  4802.2    0.05       0  5198.4    0.04       0  5204.4    0.05       0
Bank Sta=5140.2,5391.1
Exp/Cntr=0.3,0.1

Type RM Length L Ch R = 1,782,374,374,374
BEGIN DESCRIPTION:
Mapping XS e18d8064
END DESCRIPTION:
XS GIS Cut Line= 3
      2892604.86      7076611.27      2892344.42      7076857.83
      2892261.08      7077239.80
#Sta/Elev= 30
  4765.0  493.18  4838.2  493.56  4859.6  494.26  4880.7  494.38  4888.0  493.83
  4900.9  493.79  4909.0  493.32  4923.2  494.15  4944.2  491.20  4951.5  493.18
  4979.8  492.69  4994.0  491.53  5000.8  489.73  5008.1  491.32  5015.0  491.77
  5038.0  490.96  5107.2  489.26  5140.2  489.30  5145.3  488.62  5189.3  489.01
  5219.8  488.46  5240.6  487.86  5241.1  487.06  5246.1  487.06  5246.6  487.86
  5334.6  488.46  5366.4  489.31  5380.3  490.83  5438.0  494.10  5514.6  494.26
#Mann=5,-1,0
  4765.0    0.05       0  4900.9    0.08       0  5038.0    0.05       0
  5240.6    0.07       0  5246.6    0.05       0
Bank Sta=5219.8,5334.6
Exp/Cntr=0.3,0.1

Type RM Length L Ch R = 1,408,0,0,0
BEGIN DESCRIPTION:
UNT 089 in Running Cr Watershed 1.0
END DESCRIPTION:
XS GIS Cut Line= 4
      2892417.34      7076434.21      2892064.37      7076552.73
      2892073.58      7076781.44      2892205.53      7077218.94
#Sta/Elev= 30
  4474.4  491.62  4561.3  491.88  4645.0  490.16  4650.3  490.97  4676.5  488.79
  4681.8  489.06  4708.1  487.61  4713.4  487.94  4730.0  486.85  4751.1  486.75
  4761.7  485.52  4789.8  484.37  4840.8  483.15  4841.3  482.35  4846.3  482.35
  4846.8  483.15  4879.0  483.60  4939.1  485.77  4959.1  484.55  4979.1  484.69
  4985.4  483.97  4993.3  484.37  5009.1  486.25  5096.4  484.37  5162.4  484.89
  5233.6  486.14  5392.7  491.70  5455.4  492.03  5480.1  493.12  5532.6  493.69
#Mann=3,-1,0
  4474.4    0.05       0  4840.8    0.04       0  4846.8    0.05       0
Bank Sta=4789.8,4993.3
Exp/Cntr=0.3,0.1

Chan Stop Cuts=-1