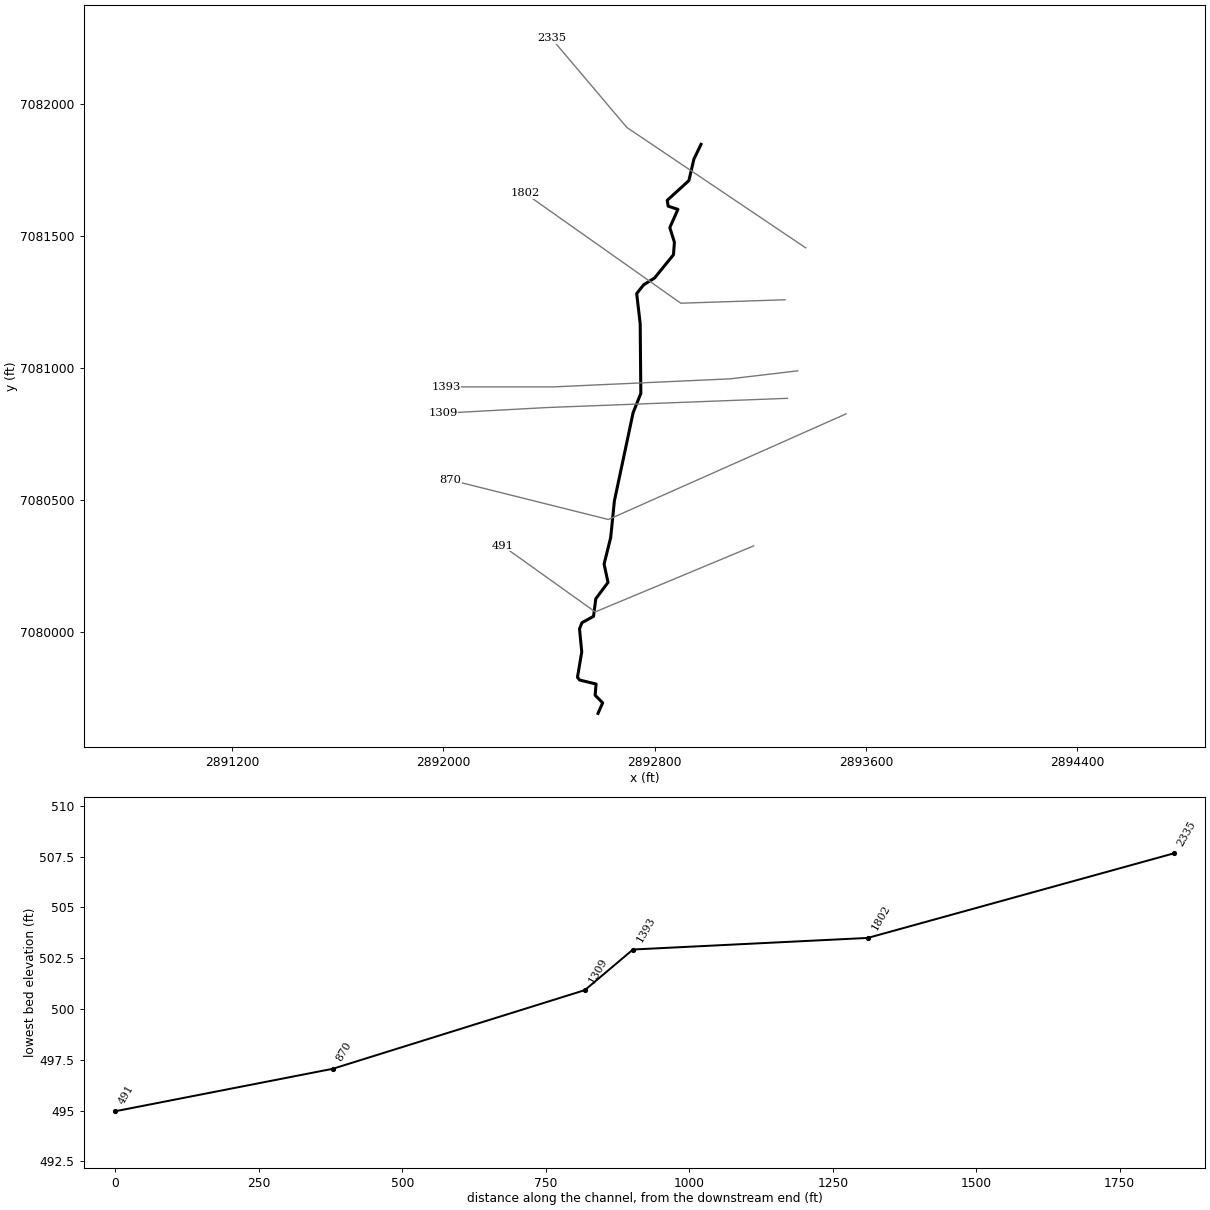
--- UNT 090 in Running Cr Watershed.prj (project) ---

Proj Title=UNT 090 in Running Cr Watershed Base Level Engineering
Current Plan=p01
Default Exp/Contr=0.3,0.1
English Units
Geom File=g01
Flow File=f01
Plan File=p01
BEGIN DESCRIPTION:
UNT 090 in Running Cr Watershed
END DESCRIPTION:

--- UNT 090 in Running Cr Watershed.p01 (plan) ---

Plan Title=Multiple Run
Short Identifier=Multiple
Geom File=g01
Flow File=f01
Subcritical Flow
K Sum by GR= 0
Std Step Tol= 0.01
Critical Tol= 0.01
Num of Std Step Trials= 20
Max Error Tol= 0.3
Flow Tol Ratio= 0.001
Split Flow NTrial= 30
Split Flow Tol= 0.02
Split Flow Ratio= 0.02
Log Output Level= 0
Friction Slope Method= 1
Unsteady Friction Slope Method= 2
Unsteady Bridges Friction Slope Method= 1
Parabolic Critical Depth
Global Vel Dist=  1 , 1 , 1
Global Log Level= 0
CheckData=True
Encroach Param= -1, 0, 0, 0
BEGIN DESCRIPTION:
Multiple Run
END DESCRIPTION:

--- UNT 090 in Running Cr Watershed.f01 (steady flow) ---

Flow Title=Multiple
Number of Profiles=7
Profile Names=10-year,25-year,50-year,1pct_min,100-year,1pct_plu,500-year
River Rch & RM= UNT 090 in Runni,Reach-1,2335
     324     411     477     276     551    1099     729
Boundary for River Rch & Prof#=UNT 090 in Runni,Reach-1,1
Up Type=0
Dn Type=3
Dn Slope=0.005
Boundary for River Rch & Prof#=UNT 090 in Runni,Reach-1,2
Up Type=0
Dn Type=3
Dn Slope=0.005
Boundary for River Rch & Prof#=UNT 090 in Runni,Reach-1,3
Up Type=0
Dn Type=3
Dn Slope=0.005
Boundary for River Rch & Prof#=UNT 090 in Runni,Reach-1,4
Up Type=0
Dn Type=3
Dn Slope=0.005
Boundary for River Rch & Prof#=UNT 090 in Runni,Reach-1,5
Up Type=0
Dn Type=3
Dn Slope=0.005
Boundary for River Rch & Prof#=UNT 090 in Runni,Reach-1,6
Up Type=0
Dn Type=3
Dn Slope=0.005
Boundary for River Rch & Prof#=UNT 090 in Runni,Reach-1,7
Up Type=0
Dn Type=3
Dn Slope=0.005

--- UNT 090 in Running Cr Watershed.g01 (geometry) ---

Geom Title=Existing Conditions

River Reach=UNT 090 in Runni,Reach-1
Reach XY= 30
      2892975.59      7081845.71      2892948.61      7081789.44
      2892929.74      7081708.53      2892847.79      7081633.86
      2892851.22      7081611.71      2892888.13      7081599.53
      2892857.51      7081530.44      2892874.93      7081475.27
      2892871.43      7081427.87      2892799.83      7081339.65
      2892758.52      7081313.88      2892732.09      7081280.60
      2892745.36      7081166.08      2892747.74      7080902.62
      2892718.52      7080829.51      2892647.52      7080494.91
      2892633.57      7080356.53      2892608.58      7080256.10
      2892623.46      7080186.73      2892577.18      7080124.92
      2892568.68      7080058.31      2892524.81      7080034.18
      2892515.51      7080010.81      2892523.97      7079923.66
      2892507.74      7079827.18      2892516.06      7079816.99
      2892578.28      7079801.81      2892574.66      7079759.31
      2892603.18      7079730.70      2892585.59      7079690.71

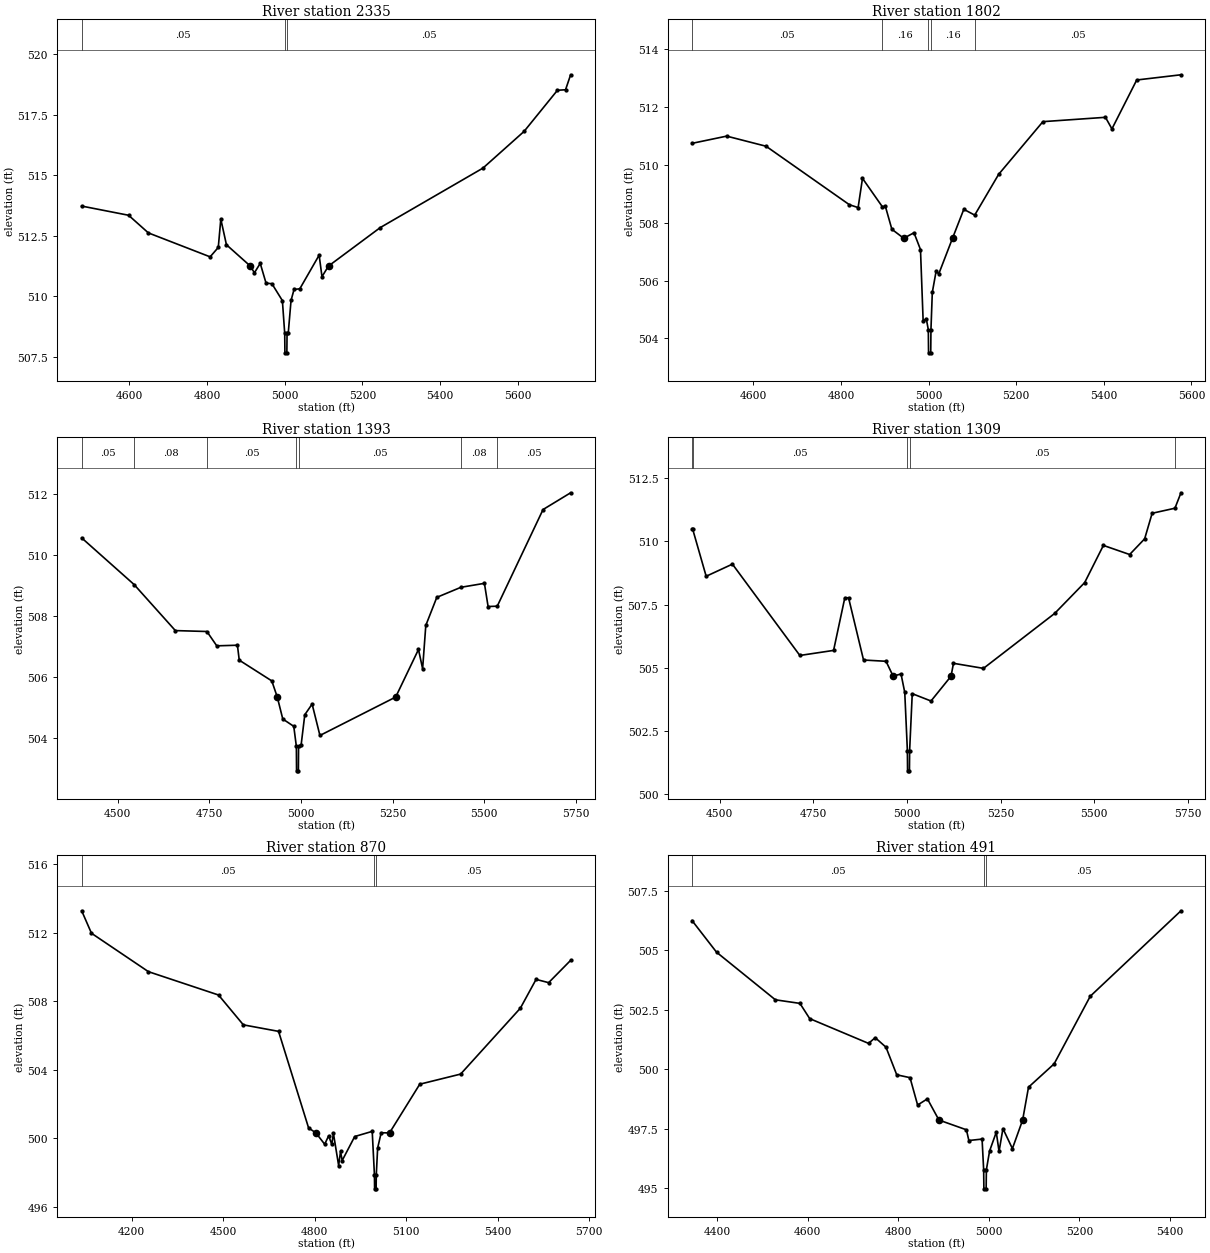
Type RM Length L Ch R = 1,2335,533,533,533
BEGIN DESCRIPTION:
UNT 090 in Running Cr Watershed 3.0
END DESCRIPTION:
XS GIS Cut Line= 3
      2893372.05      7081453.89      2892694.97      7081909.62
      2892409.25      7082247.29
#Sta/Elev= 30
  4477.3  513.73  4598.0  513.35  4649.0  512.62  4807.9  511.63  4828.9  512.02
  4835.4  513.19  4849.9  512.13  4911.3  511.25  4921.9  510.97  4936.9  511.36
  4951.9  510.54  4966.9  510.52  4993.9  509.82  4999.9  508.46  5000.4  507.66
  5005.4  507.66  5005.9  508.46  5008.9  508.46  5016.2  509.83  5023.9  510.28
  5038.8  510.31  5088.5  511.70  5095.8  510.81  5112.6  511.25  5245.8  512.84
  5510.1  515.30  5616.1  516.82  5701.9  518.52  5722.7  518.54  5735.8  519.16
#Mann=3,-1,0
  4477.3    0.05       0  4999.9    0.03       0  5005.9    0.05       0
Bank Sta=4911.3,5112.6
Exp/Cntr=0.3,0.1

Type RM Length L Ch R = 1,1802,409,409,409
BEGIN DESCRIPTION:
Mapping XS cf8cac86
END DESCRIPTION:
XS GIS Cut Line= 3
      2893294.04      7081257.13      2892899.11      7081244.11
      2892309.95      7081659.99
#Sta/Elev= 30
  4459.9  510.74  4539.0  510.99  4629.0  510.64  4819.1  508.62  4839.1  508.52
  4849.1  509.53  4894.4  508.55  4901.4  508.56  4916.2  507.77  4943.2  507.46
  4966.7  507.65  4981.5  507.07  4987.6  504.59  4994.7  504.68  4999.4  504.30
  4999.9  503.50  5004.9  503.50  5005.4  504.30  5008.5  505.59  5017.2  506.32
  5023.3  506.23  5054.6  507.46  5080.4  508.46  5105.3  508.26  5160.0  509.67
  5261.0  511.49  5403.8  511.64  5418.6  511.24  5475.2  512.93  5576.2  513.11
#Mann=5,-1,0
  4459.9    0.05       0  4894.4    0.16       0  4999.4    0.07       0
  5005.4    0.16       0  5105.3    0.05       0
Bank Sta=4943.2,5054.6
Exp/Cntr=0.3,0.1

Type RM Length L Ch R = 1,1393,84,84,84
BEGIN DESCRIPTION:
Mapping XS 59edeb14
END DESCRIPTION:
XS GIS Cut Line= 4
      2893341.81      7080988.03      2893085.74      7080957.65
      2892417.33      7080927.27      2892009.70      7080927.27
#Sta/Elev= 30
  4401.6  510.57  4544.7  509.04  4657.3  507.53  4743.4  507.50  4770.3  507.03
  4826.7  507.05  4831.7  506.56  4920.5  505.88  4935.5  505.35  4950.5  504.63
  4980.5  504.39  4987.6  503.73  4988.1  502.93  4993.1  502.93  4993.6  503.73
  5000.6  503.78  5010.6  504.77  5030.6  505.12  5051.9  504.09  5258.7  505.35
  5320.9  506.91  5332.2  506.28  5340.9  507.70  5370.9  508.62  5436.8  508.95
  5500.9  509.08  5510.9  508.32  5535.9  508.33  5660.9  511.50  5736.2  512.05
#Mann=7,-1,0
  4401.6    0.05       0  4544.7    0.08       0  4743.4    0.05       0
  4987.6    0.04       0  4993.6    0.05       0  5436.8    0.08       0
  5535.9    0.05       0
Bank Sta=4935.5,5258.7
Exp/Cntr=0.3,0.1

Type RM Length L Ch R = 1,1309,439,439,439
BEGIN DESCRIPTION:
Mapping XS c8d14f16
END DESCRIPTION:
XS GIS Cut Line= 3
      2893302.79      7080883.87      2892395.63      7080849.15
      2891998.14      7080827.54
#Sta/Elev= 30
  4426.0  510.50  4428.0  510.47  4463.8  508.62  4533.9  509.10  4714.0  505.49
  4804.1  505.69  4834.1  507.77  4844.1  507.77  4884.1  505.31  4944.2  505.26
  4963.2  504.67  4984.2  504.76  4994.2  504.03  5001.2  501.73  5001.7  500.93
  5006.7  500.93  5007.2  501.73  5014.2  503.98  5064.3  503.69  5117.8  504.67
  5124.3  505.18  5204.4  504.98  5394.5  507.15  5474.7  508.37  5524.7  509.84
  5594.8  509.48  5634.9  510.10  5654.9  511.11  5715.8  511.31  5731.9  511.92
#Mann=5,-1,0
  4426.0    0.08       0  4428.0    0.05       0  5001.2    0.03       0
  5007.2    0.05       0  5715.8    0.08       0
Bank Sta=4963.2,5117.8
Exp/Cntr=0.3,0.1

Type RM Length L Ch R = 1,870,379,379,379
BEGIN DESCRIPTION:
UNT 090 in Running Cr Watershed 2.0
END DESCRIPTION:
XS GIS Cut Line= 3
      2893524.99      7080825.00      2892625.00      7080425.00
      2892025.04      7080574.99
#Sta/Elev= 30
  4036.3  513.27  4068.4  511.96  4255.2  509.72  4485.0  508.36  4566.4  506.62
  4681.9  506.24  4780.4  500.61  4804.4  500.32  4833.1  499.66  4846.1  500.15
  4856.3  499.66  4861.8  500.29  4878.9  498.42  4885.1  499.24  4890.5  498.71
  4931.6  500.11  4989.0  500.41  4996.3  497.86  4996.8  497.06  5001.8  497.06
  5002.3  497.86  5006.8  499.44  5018.4  500.33  5045.7  500.32  5144.9  503.16
  5278.9  503.75  5474.7  507.59  5526.3  509.27  5567.5  509.08  5639.6  510.38
#Mann=3,-1,0
  4036.3    0.05       0  4996.3    0.03       0  5002.3    0.05       0
Bank Sta=4804.4,5045.7
Exp/Cntr=0.3,0.1

Type RM Length L Ch R = 1,491,0,0,0
BEGIN DESCRIPTION:
UNT 090 in Running Cr Watershed 1.0
END DESCRIPTION:
XS GIS Cut Line= 3
      2893175.03      7080325.01      2892575.00      7080075.00
      2892224.96      7080325.03
#Sta/Elev= 30
  4344.2  506.24  4398.4  504.91  4528.4  502.91  4582.6  502.76  4604.2  502.12
  4734.2  501.08  4748.9  501.32  4772.7  500.92  4796.5  499.76  4825.8  499.64
  4842.6  498.49  4864.2  498.75  4889.7  497.86  4950.4  497.45  4955.8  497.00
  4985.0  497.06  4988.5  495.77  4989.0  494.97  4994.0  494.97  4994.5  495.77
  5001.6  496.56  5016.4  497.35  5022.5  496.54  5031.1  497.50  5052.0  496.66
  5074.6  497.86  5087.6  499.24  5144.2  500.22  5224.0  503.06  5424.4  506.65
#Mann=3,-1,0
  4344.2    0.05       0  4988.5    0.03       0  4994.5    0.05       0
Bank Sta=4889.7,5074.6
Exp/Cntr=0.3,0.1

Chan Stop Cuts=-1