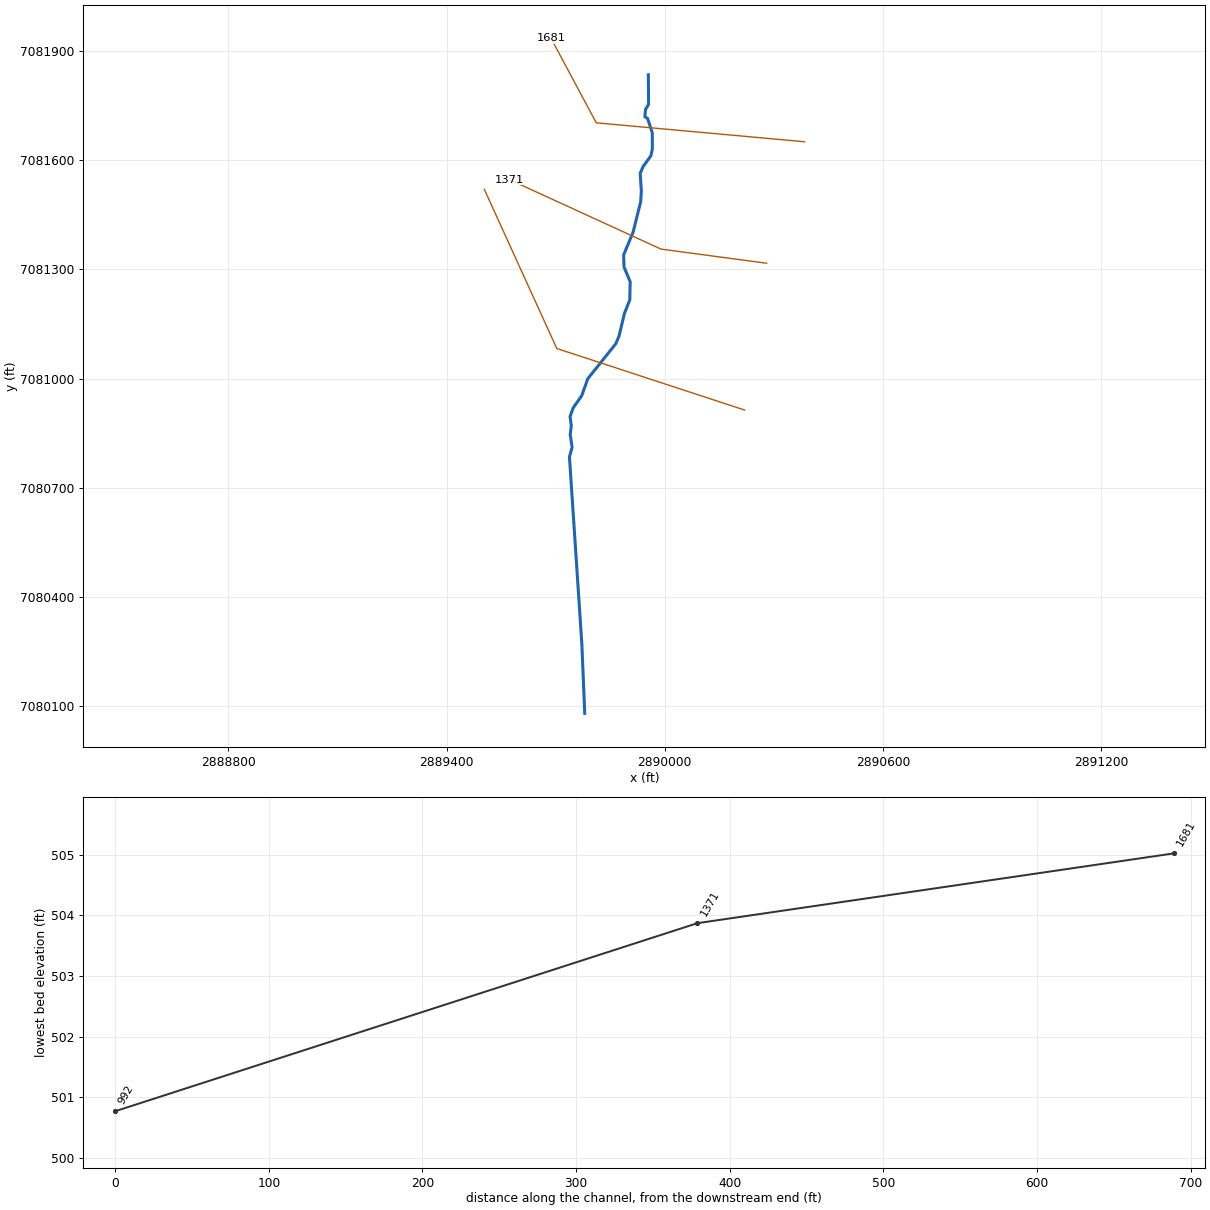
--- UNT 091 in Running Cr Watershed.prj (project) ---

Proj Title=UNT 091 in Running Cr Watershed Base Level Engineering
Current Plan=p01
Default Exp/Contr=0.3,0.1
English Units
Geom File=g01
Flow File=f01
Plan File=p01
BEGIN DESCRIPTION:
UNT 091 in Running Cr Watershed
END DESCRIPTION:

--- UNT 091 in Running Cr Watershed.p01 (plan) ---

Plan Title=Multiple Run
Short Identifier=Multiple
Geom File=g01
Flow File=f01
Subcritical Flow
K Sum by GR= 0
Std Step Tol= 0.01
Critical Tol= 0.01
Num of Std Step Trials= 20
Max Error Tol= 0.3
Flow Tol Ratio= 0.001
Split Flow NTrial= 30
Split Flow Tol= 0.02
Split Flow Ratio= 0.02
Log Output Level= 0
Friction Slope Method= 1
Unsteady Friction Slope Method= 2
Unsteady Bridges Friction Slope Method= 1
Parabolic Critical Depth
Global Vel Dist=  1 , 1 , 1
Global Log Level= 0
CheckData=True
Encroach Param= -1, 0, 0, 0
BEGIN DESCRIPTION:
Multiple Run
END DESCRIPTION:

--- UNT 091 in Running Cr Watershed.f01 (steady flow) ---

Flow Title=Multiple
Number of Profiles=7
Profile Names=10-year,25-year,50-year,1pct_min,100-year,1pct_plu,500-year
River Rch & RM= UNT 091 in Runni,Reach-1,1681
     213     262     299     170     339     677     433
Boundary for River Rch & Prof#=UNT 091 in Runni,Reach-1,1
Up Type=0
Dn Type=3
Dn Slope=0.005
Boundary for River Rch & Prof#=UNT 091 in Runni,Reach-1,2
Up Type=0
Dn Type=3
Dn Slope=0.005
Boundary for River Rch & Prof#=UNT 091 in Runni,Reach-1,3
Up Type=0
Dn Type=3
Dn Slope=0.005
Boundary for River Rch & Prof#=UNT 091 in Runni,Reach-1,4
Up Type=0
Dn Type=3
Dn Slope=0.005
Boundary for River Rch & Prof#=UNT 091 in Runni,Reach-1,5
Up Type=0
Dn Type=3
Dn Slope=0.005
Boundary for River Rch & Prof#=UNT 091 in Runni,Reach-1,6
Up Type=0
Dn Type=3
Dn Slope=0.005
Boundary for River Rch & Prof#=UNT 091 in Runni,Reach-1,7
Up Type=0
Dn Type=3
Dn Slope=0.005

--- UNT 091 in Running Cr Watershed.g01 (geometry) ---

Geom Title=Existing Conditions

River Reach=UNT 091 in Runni,Reach-1
Reach XY= 30
      2889954.71      7081835.40      2889955.41      7081754.15
      2889947.07      7081740.26      2889944.99      7081720.12
      2889952.63      7081715.26      2889965.59      7081675.71
      2889965.66      7081631.05      2889961.62      7081612.22
      2889940.56      7081583.40      2889932.27      7081564.38
      2889935.46      7081515.80      2889933.73      7081486.57
      2889912.62      7081401.91      2889886.75      7081340.04
      2889887.86      7081306.87      2889904.74      7081266.24
      2889903.71      7081216.31      2889889.05      7081179.31
      2889873.97      7081116.38      2889865.27      7081095.84
      2889788.26      7080999.59      2889771.30      7080952.41
      2889748.16      7080919.58      2889739.44      7080895.70
      2889742.73      7080870.78      2889739.88      7080845.69
      2889745.07      7080810.57      2889737.73      7080784.58
      2889771.84      7080270.00      2889779.80      7080079.09

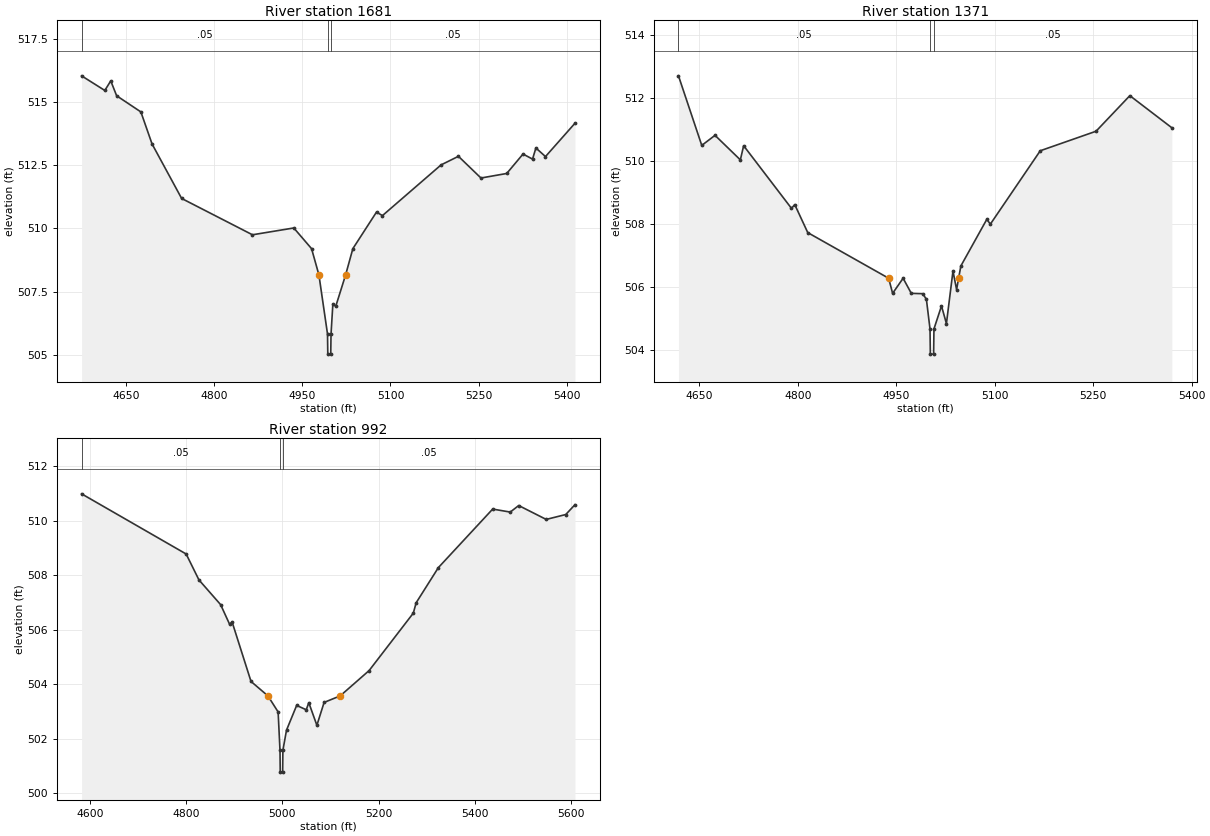
Type RM Length L Ch R = 1,1681,310,310,310
BEGIN DESCRIPTION:
UNT 091 in Running Cr Watershed 2.0
END DESCRIPTION:
XS GIS Cut Line= 3
      2890384.35      7081651.23      2889811.43      7081703.31
      2889687.15      7081935.68
#Sta/Elev= 30
  4574.9  516.05  4614.4  515.47  4624.5  515.85  4634.5  515.26  4675.7  514.62
  4694.7  513.35  4745.0  511.19  4865.4  509.75  4935.7  510.02  4965.9  509.20
  4978.4  508.16  4993.0  505.82  4993.5  505.02  4998.5  505.02  4999.0  505.82
  5002.1  507.00  5007.1  506.92  5023.8  508.16  5036.1  509.20  5076.3  510.65
  5086.4  510.51  5186.1  512.52  5215.6  512.86  5253.9  512.00  5297.7  512.18
  5325.4  512.95  5341.6  512.75  5347.3  513.19  5363.6  512.85  5413.7  514.17
#Mann=3,-1,0
  4574.9    0.05       0  4993.0    0.03       0  4999.0    0.05       0
Bank Sta=4978.4,5023.8
Exp/Cntr=0.3,0.1

Type RM Length L Ch R = 1,1371,379,379,379
BEGIN DESCRIPTION:
Mapping XS bb88a6b1
END DESCRIPTION:
XS GIS Cut Line= 3
      2890280.22      7081317.02      2889989.38      7081356.09
      2889572.72      7081547.06
#Sta/Elev= 30
  4618.0  512.71  4653.5  510.50  4673.7  510.82  4712.3  510.04  4717.3  510.49
  4790.2  508.50  4795.2  508.62  4815.0  507.73  4938.3  506.28  4944.3  505.80
  4960.3  506.28  4972.8  505.80  4990.3  505.79  4995.8  505.61  5001.3  504.67
  5001.8  503.87  5006.8  503.87  5007.3  504.67  5018.8  505.40  5026.3  504.84
  5036.3  506.51  5041.8  505.92  5044.9  506.28  5048.3  506.67  5087.8  508.15
  5093.3  508.00  5169.3  510.33  5254.3  510.95  5305.8  512.08  5369.8  511.06
#Mann=3,-1,0
  4618.0    0.05       0  5001.3    0.03       0  5007.3    0.05       0
Bank Sta=4938.3,5044.9
Exp/Cntr=0.3,0.1

Type RM Length L Ch R = 1,992,0,0,0
BEGIN DESCRIPTION:
UNT 091 in Running Cr Watershed 1.0
END DESCRIPTION:
XS GIS Cut Line= 3
      2890219.44      7080913.37      2889702.92      7081082.65
      2889503.50      7081520.53
#Sta/Elev= 30
  4583.0  510.99  4800.2  508.78  4826.7  507.83  4871.8  506.92  4890.4  506.20
  4895.7  506.28  4934.9  504.10  4970.0  503.57  4991.2  502.98  4995.1  501.57
  4995.6  500.77  5000.6  500.77  5001.1  501.57  5008.6  502.31  5029.7  503.22
  5049.6  503.06  5054.9  503.32  5071.7  502.49  5086.7  503.33  5120.1  503.57
  5180.2  504.50  5272.0  506.61  5277.9  506.99  5324.0  508.28  5436.8  510.43
  5473.3  510.32  5490.9  510.56  5548.0  510.05  5588.6  510.23  5607.7  510.59
#Mann=3,-1,0
  4583.0    0.05       0  4995.1    0.03       0  5001.1    0.05       0
Bank Sta=4970,5120.1
Exp/Cntr=0.3,0.1

Chan Stop Cuts=-1