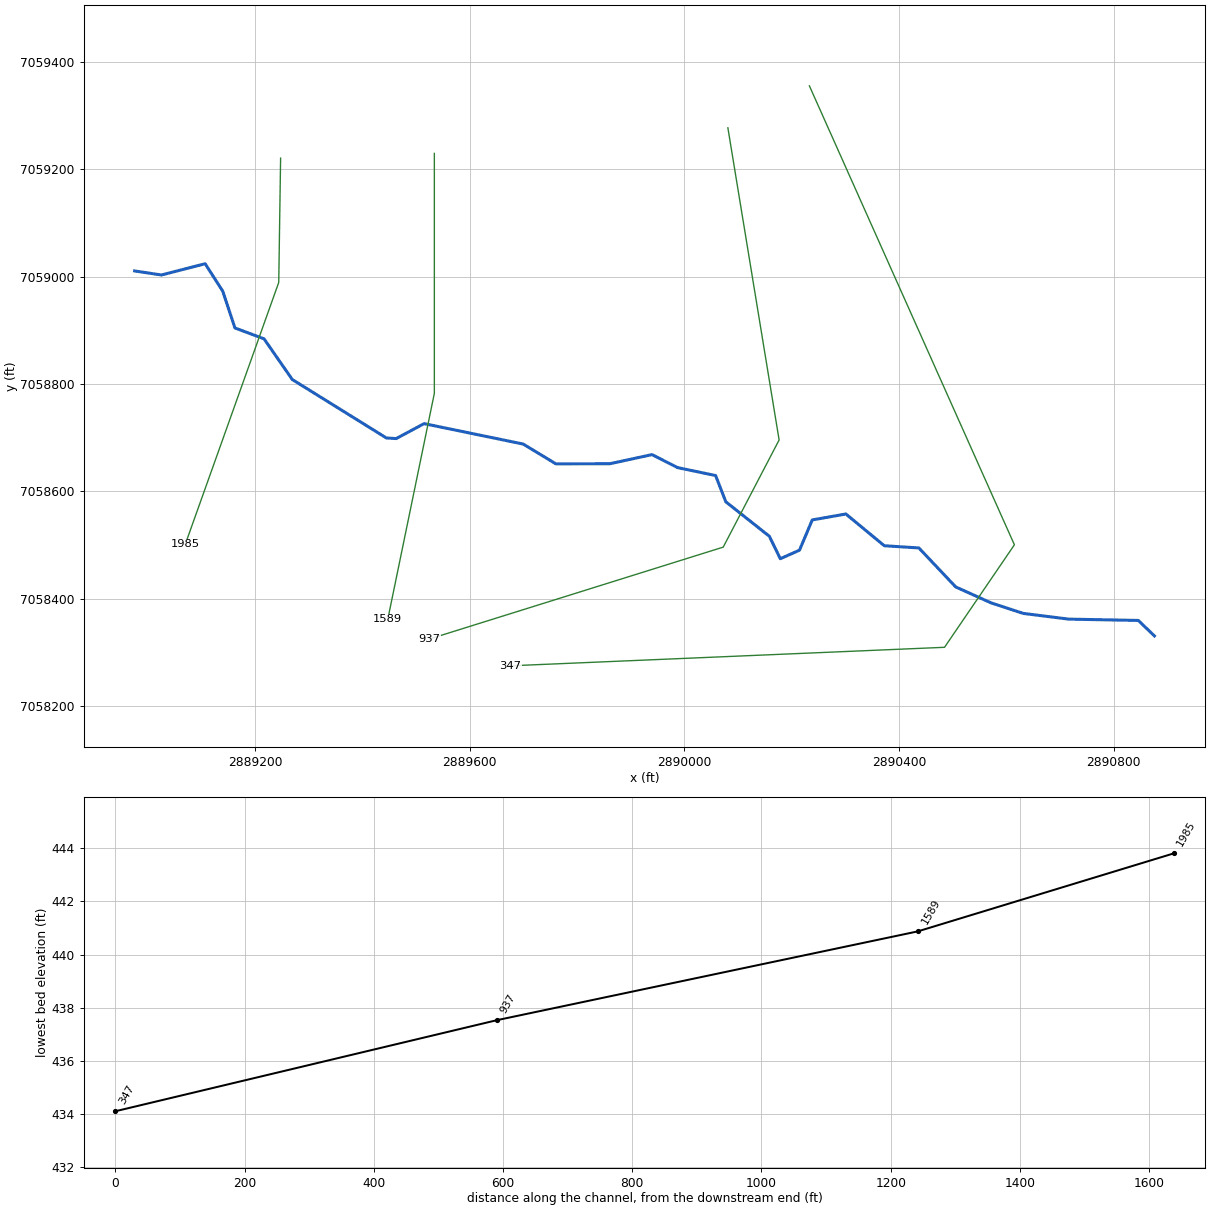
--- UNT 092 in Running Cr Watershed.prj (project) ---

Proj Title=UNT 092 in Running Cr Watershed Base Level Engineering
Current Plan=p01
Default Exp/Contr=0.3,0.1
English Units
Geom File=g01
Flow File=f01
Plan File=p01
BEGIN DESCRIPTION:
UNT 092 in Running Cr Watershed
END DESCRIPTION:

--- UNT 092 in Running Cr Watershed.p01 (plan) ---

Plan Title=Multiple Run
Short Identifier=Multiple
Geom File=g01
Flow File=f01
Subcritical Flow
K Sum by GR= 0
Std Step Tol= 0.01
Critical Tol= 0.01
Num of Std Step Trials= 20
Max Error Tol= 0.3
Flow Tol Ratio= 0.001
Split Flow NTrial= 30
Split Flow Tol= 0.02
Split Flow Ratio= 0.02
Log Output Level= 0
Friction Slope Method= 1
Unsteady Friction Slope Method= 2
Unsteady Bridges Friction Slope Method= 1
Parabolic Critical Depth
Global Vel Dist=  1 , 1 , 1
Global Log Level= 0
CheckData=True
Encroach Param= -1, 0, 0, 0
BEGIN DESCRIPTION:
Multiple Run
END DESCRIPTION:

--- UNT 092 in Running Cr Watershed.f01 (steady flow) ---

Flow Title=Multiple
Number of Profiles=7
Profile Names=10-year,25-year,50-year,1pct_min,100-year,1pct_plu,500-year
River Rch & RM= UNT 092 in Runni,Reach-1,1985
     537     709     847     503    1004    2003    1407
Boundary for River Rch & Prof#=UNT 092 in Runni,Reach-1,1
Up Type=0
Dn Type=3
Dn Slope=0.005
Boundary for River Rch & Prof#=UNT 092 in Runni,Reach-1,2
Up Type=0
Dn Type=3
Dn Slope=0.005
Boundary for River Rch & Prof#=UNT 092 in Runni,Reach-1,3
Up Type=0
Dn Type=3
Dn Slope=0.005
Boundary for River Rch & Prof#=UNT 092 in Runni,Reach-1,4
Up Type=0
Dn Type=3
Dn Slope=0.005
Boundary for River Rch & Prof#=UNT 092 in Runni,Reach-1,5
Up Type=0
Dn Type=3
Dn Slope=0.005
Boundary for River Rch & Prof#=UNT 092 in Runni,Reach-1,6
Up Type=0
Dn Type=3
Dn Slope=0.005
Boundary for River Rch & Prof#=UNT 092 in Runni,Reach-1,7
Up Type=0
Dn Type=3
Dn Slope=0.005

--- UNT 092 in Running Cr Watershed.g01 (geometry) ---

Geom Title=Existing Conditions

River Reach=UNT 092 in Runni,Reach-1
Reach XY= 30
      2888975.59      7059010.71      2889025.58      7059003.19
      2889106.94      7059024.12      2889139.63      7058973.19
      2889162.49      7058904.47      2889216.65      7058884.25
      2889269.25      7058808.44      2889444.64      7058699.51
      2889462.84      7058698.39      2889514.84      7058726.21
      2889699.54      7058688.17      2889760.32      7058651.34
      2889860.85      7058651.51      2889939.54      7058668.50
      2889987.13      7058644.32      2890057.99      7058629.50
      2890077.03      7058580.58      2890158.15      7058516.35
      2890178.56      7058474.53      2890214.32      7058490.45
      2890238.06      7058546.79      2890300.69      7058557.88
      2890372.29      7058498.73      2890436.72      7058494.62
      2890505.35      7058421.95      2890571.24      7058392.28
      2890631.37      7058372.60      2890715.80      7058362.00
      2890845.51      7058359.55      2890875.59      7058330.71

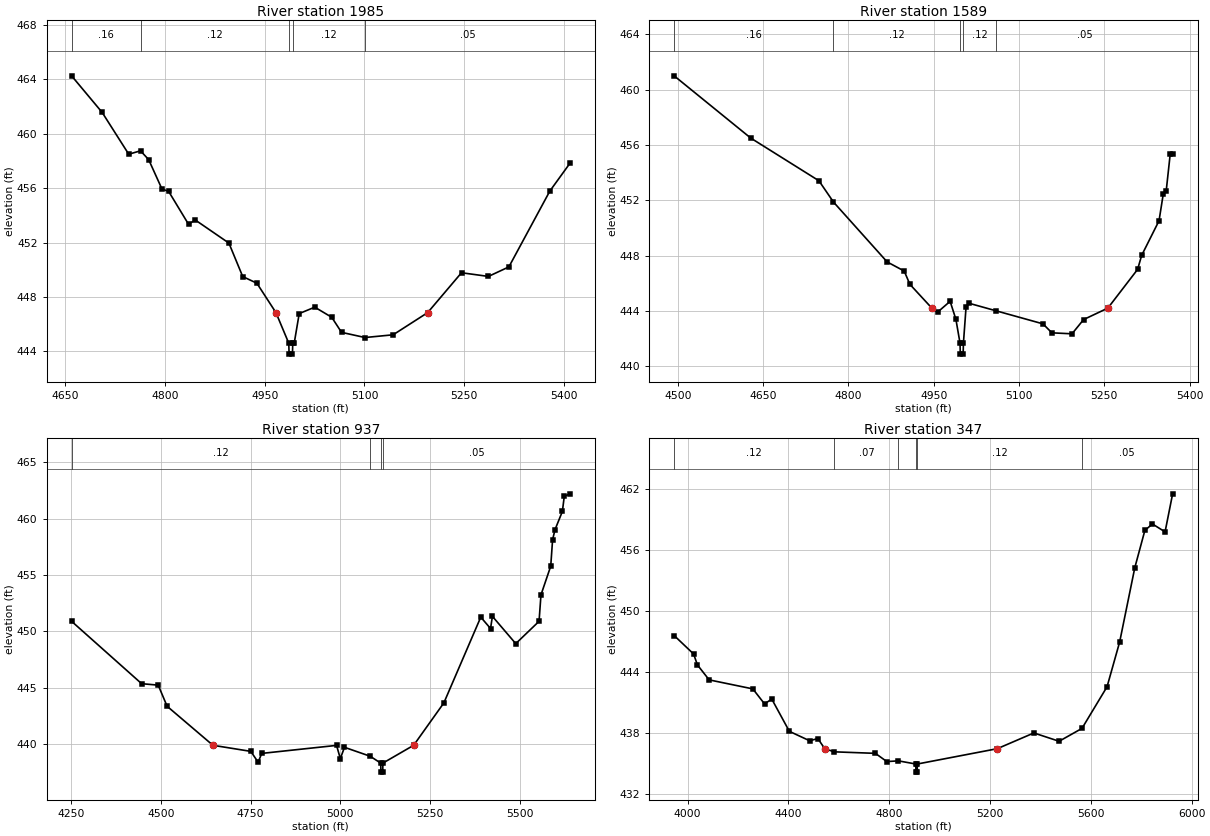
Type RM Length L Ch R = 1,1985,396,396,396
BEGIN DESCRIPTION:
UNT 092 in Running Cr Watershed 3.0
END DESCRIPTION:
XS GIS Cut Line= 3
      2889247.51      7059221.01      2889244.06      7058989.33
      2889069.79      7058501.10
#Sta/Elev= 30
  4659.3  464.25  4705.3  461.56  4745.3  458.49  4763.0  458.74  4775.3  458.09
  4795.3  455.93  4805.3  455.76  4835.3  453.34  4845.3  453.66  4896.0  451.96
  4916.8  449.50  4938.1  449.01  4966.8  446.85  4986.1  444.60  4986.6  443.80
  4991.6  443.80  4992.1  444.60  4994.4  444.64  5001.8  446.78  5025.2  447.25
  5050.7  446.51  5065.5  445.40  5100.8  445.02  5143.1  445.22  5195.1  446.85
  5246.0  449.78  5286.5  449.51  5317.3  450.21  5378.9  455.78  5409.4  457.84
#Mann=5,-1,0
  4659.3    0.16       0  4763.0    0.12       0  4986.1    0.07       0
  4992.1    0.12       0  5100.8    0.05       0
Bank Sta=4966.8,5195.1
Exp/Cntr=0.3,0.1

Type RM Length L Ch R = 1,1589,652,652,652
BEGIN DESCRIPTION:
Mapping XS fbd551ad
END DESCRIPTION:
XS GIS Cut Line= 3
      2889533.97      7059229.68      2889533.97      7058782.59
      2889447.18      7058361.63
#Sta/Elev= 30
  4493.3  461.00  4628.0  456.50  4748.0  453.41  4773.6  451.87  4868.0  447.54
  4898.0  446.88  4908.0  445.92  4946.6  444.20  4956.6  443.90  4978.8  444.69
  4989.0  443.38  4996.2  441.67  4996.7  440.87  5001.7  440.87  5002.2  441.67
  5006.9  444.31  5012.0  444.55  5059.9  444.00  5142.1  443.06  5157.8  442.41
  5193.2  442.34  5213.6  443.37  5256.3  444.20  5308.6  447.00  5315.7  448.01
  5346.3  450.52  5353.8  452.47  5358.9  452.68  5365.9  455.32  5370.2  455.32
#Mann=5,-1,0
  4493.3    0.16       0  4773.6    0.12       0  4996.2    0.07       0
  5002.2    0.12       0  5059.9    0.05       0
Bank Sta=4946.6,5256.3
Exp/Cntr=0.3,0.1

Type RM Length L Ch R = 1,937,590,590,590
BEGIN DESCRIPTION:
UNT 092 in Running Cr Watershed 2.0
END DESCRIPTION:
XS GIS Cut Line= 4
      2890080.84      7059277.43      2890176.33      7058695.79
      2890072.17      7058496.14      2889525.02      7058325.01
#Sta/Elev= 30
  4251.5  450.90  4446.5  445.37  4492.7  445.24  4517.4  443.37  4645.0  439.91
  4750.5  439.37  4770.8  438.41  4780.9  439.19  4989.2  439.90  4999.7  438.73
  5011.3  439.73  5082.7  438.94  5112.2  438.33  5112.7  437.53  5117.7  437.53
  5118.2  438.33  5203.9  439.91  5288.0  443.67  5390.7  451.27  5417.9  450.26
  5423.1  451.34  5488.1  448.92  5553.0  450.90  5558.3  453.24  5585.5  455.79
  5590.7  458.14  5597.5  459.03  5617.9  460.64  5623.2  461.98  5639.4  462.20
#Mann=4,-1,0
  4251.5    0.12       0  5082.7    0.05       0  5112.2    0.07       0
  5118.2    0.05       0
Bank Sta=4645,5203.9
Exp/Cntr=0.3,0.1

Type RM Length L Ch R = 1,347,0,0,0
BEGIN DESCRIPTION:
UNT 092 in Running Cr Watershed 1.0
END DESCRIPTION:
XS GIS Cut Line= 4
      2890232.76      7059355.50      2890614.70      7058500.48
      2890484.49      7058309.50      2889675.02      7058275.00
#Sta/Elev= 30
  3946.7  447.57  4023.9  445.75  4039.2  444.67  4085.6  443.20  4259.0  442.31
  4305.5  440.83  4334.1  441.31  4403.8  438.13  4484.4  437.20  4516.8  437.42
  4544.3  436.42  4582.0  436.11  4745.2  435.96  4790.6  435.15  4836.4  435.22
  4905.6  434.91  4906.1  434.11  4911.1  434.11  4911.6  434.91  5228.9  436.42
  5374.0  437.97  5474.1  437.15  5564.9  438.42  5664.3  442.52  5714.3  446.93
  5774.4  454.25  5814.4  457.93  5844.4  458.56  5894.5  457.78  5924.5  461.53
#Mann=6,-1,0
  3946.7    0.12       0  4582.0    0.07       0  4836.4    0.12       0
  4905.6    0.07       0  4911.6    0.12       0  5564.9    0.05       0
Bank Sta=4544.3,5228.9
Exp/Cntr=0.3,0.1

Chan Stop Cuts=-1