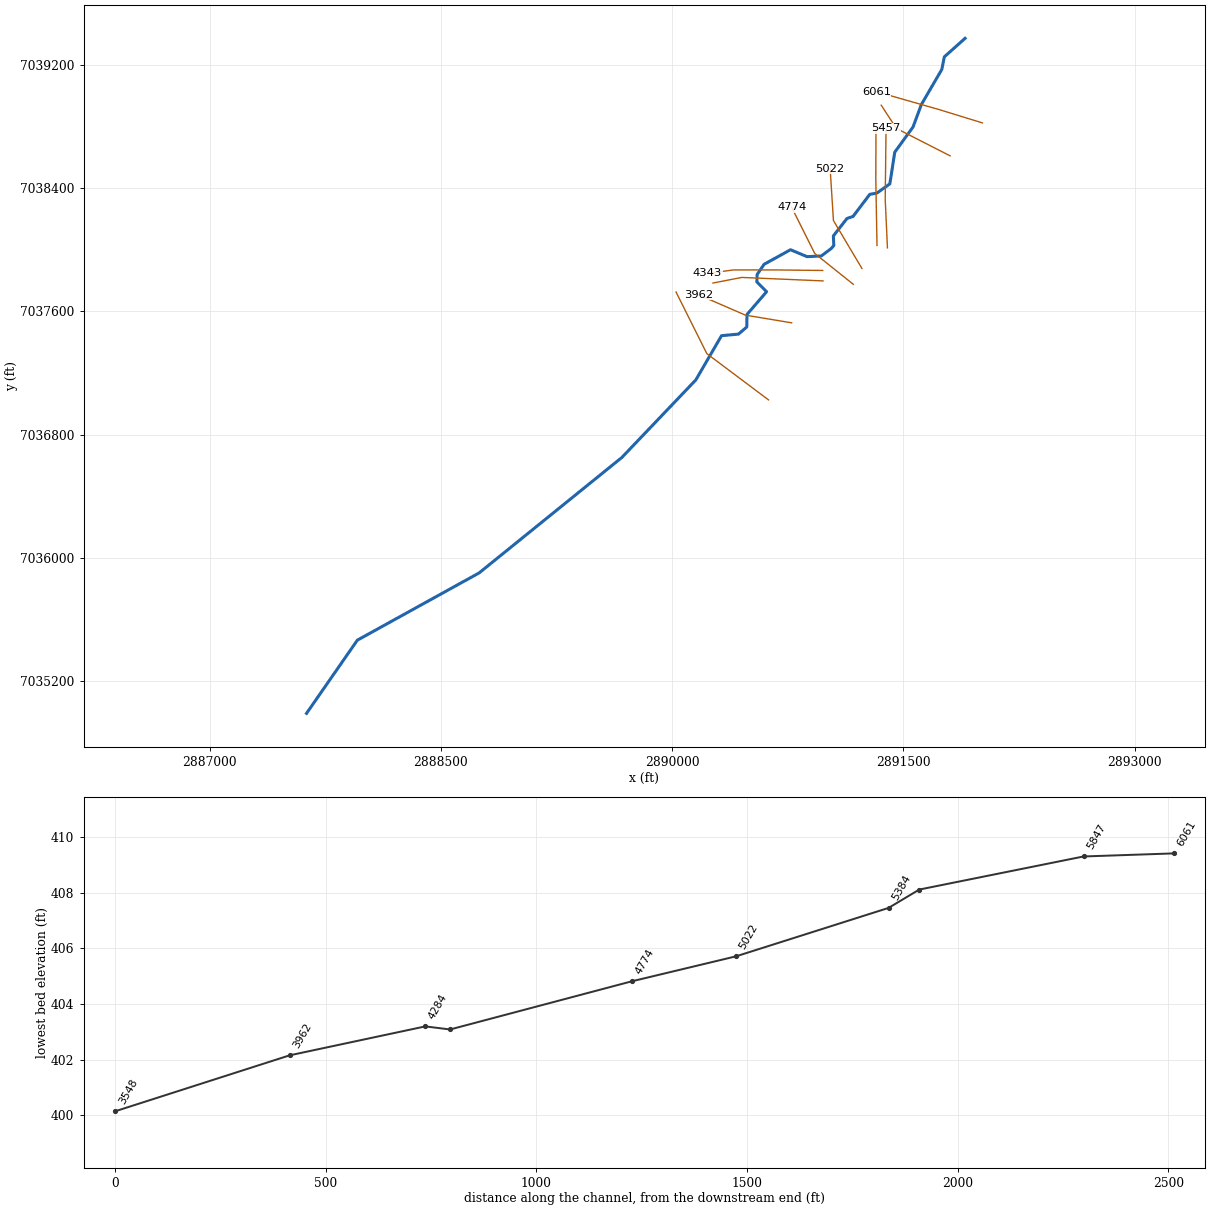
--- UNT 093 in Running Cr Watershed.prj (project) ---

Proj Title=UNT 093 in Running Cr Watershed Base Level Engineering
Current Plan=p01
Default Exp/Contr=0.3,0.1
English Units
Geom File=g01
Flow File=f01
Plan File=p01
BEGIN DESCRIPTION:
UNT 093 in Running Cr Watershed
END DESCRIPTION:

--- UNT 093 in Running Cr Watershed.p01 (plan) ---

Plan Title=Multiple Run
Short Identifier=Multiple
Geom File=g01
Flow File=f01
Subcritical Flow
K Sum by GR= 0
Std Step Tol= 0.01
Critical Tol= 0.01
Num of Std Step Trials= 20
Max Error Tol= 0.3
Flow Tol Ratio= 0.001
Split Flow NTrial= 30
Split Flow Tol= 0.02
Split Flow Ratio= 0.02
Log Output Level= 0
Friction Slope Method= 1
Unsteady Friction Slope Method= 2
Unsteady Bridges Friction Slope Method= 1
Parabolic Critical Depth
Global Vel Dist=  1 , 1 , 1
Global Log Level= 0
CheckData=True
Encroach Param= -1, 0, 0, 0
BEGIN DESCRIPTION:
Multiple Run
END DESCRIPTION:

--- UNT 093 in Running Cr Watershed.f01 (steady flow) ---

Flow Title=Multiple
Number of Profiles=7
Profile Names=10-year,25-year,50-year,1pct_min,100-year,1pct_plu,500-year
River Rch & RM= UNT 093 in Runni,Reach-1,6061
     396     511     601     351     701    1398     954
Boundary for River Rch & Prof#=UNT 093 in Runni,Reach-1,1
Up Type=0
Dn Type=3
Dn Slope=0.005
Boundary for River Rch & Prof#=UNT 093 in Runni,Reach-1,2
Up Type=0
Dn Type=3
Dn Slope=0.005
Boundary for River Rch & Prof#=UNT 093 in Runni,Reach-1,3
Up Type=0
Dn Type=3
Dn Slope=0.005
Boundary for River Rch & Prof#=UNT 093 in Runni,Reach-1,4
Up Type=0
Dn Type=3
Dn Slope=0.005
Boundary for River Rch & Prof#=UNT 093 in Runni,Reach-1,5
Up Type=0
Dn Type=3
Dn Slope=0.005
Boundary for River Rch & Prof#=UNT 093 in Runni,Reach-1,6
Up Type=0
Dn Type=3
Dn Slope=0.005
Boundary for River Rch & Prof#=UNT 093 in Runni,Reach-1,7
Up Type=0
Dn Type=3
Dn Slope=0.005

--- UNT 093 in Running Cr Watershed.g01 (geometry) ---

Geom Title=Existing Conditions

River Reach=UNT 093 in Runni,Reach-1
Reach XY= 30
      2891900.46      7039370.88      2891765.76      7039250.67
      2891749.82      7039169.55      2891616.57      7038940.71
      2891562.98      7038795.87      2891444.21      7038632.20
      2891412.35      7038426.52      2891328.34      7038367.14
      2891281.99      7038358.45      2891173.36      7038215.05
      2891134.25      7038202.02      2891045.90      7038089.04
      2891048.79      7038026.76      2891032.86      7038007.93
      2890967.68      7037958.69      2890874.99      7037954.34
      2890767.80      7037999.24      2890596.37      7037904.65
      2890551.23      7037838.68      2890549.49      7037790.06
      2890612.82      7037726.94      2890485.36      7037579.20
      2890483.92      7037498.09      2890430.32      7037451.74
      2890320.25      7037441.60      2890153.68      7037154.82
      2889673.62      7036651.40      2888747.54      7035902.28
      2887957.13      7035465.79      2887627.57      7034990.91

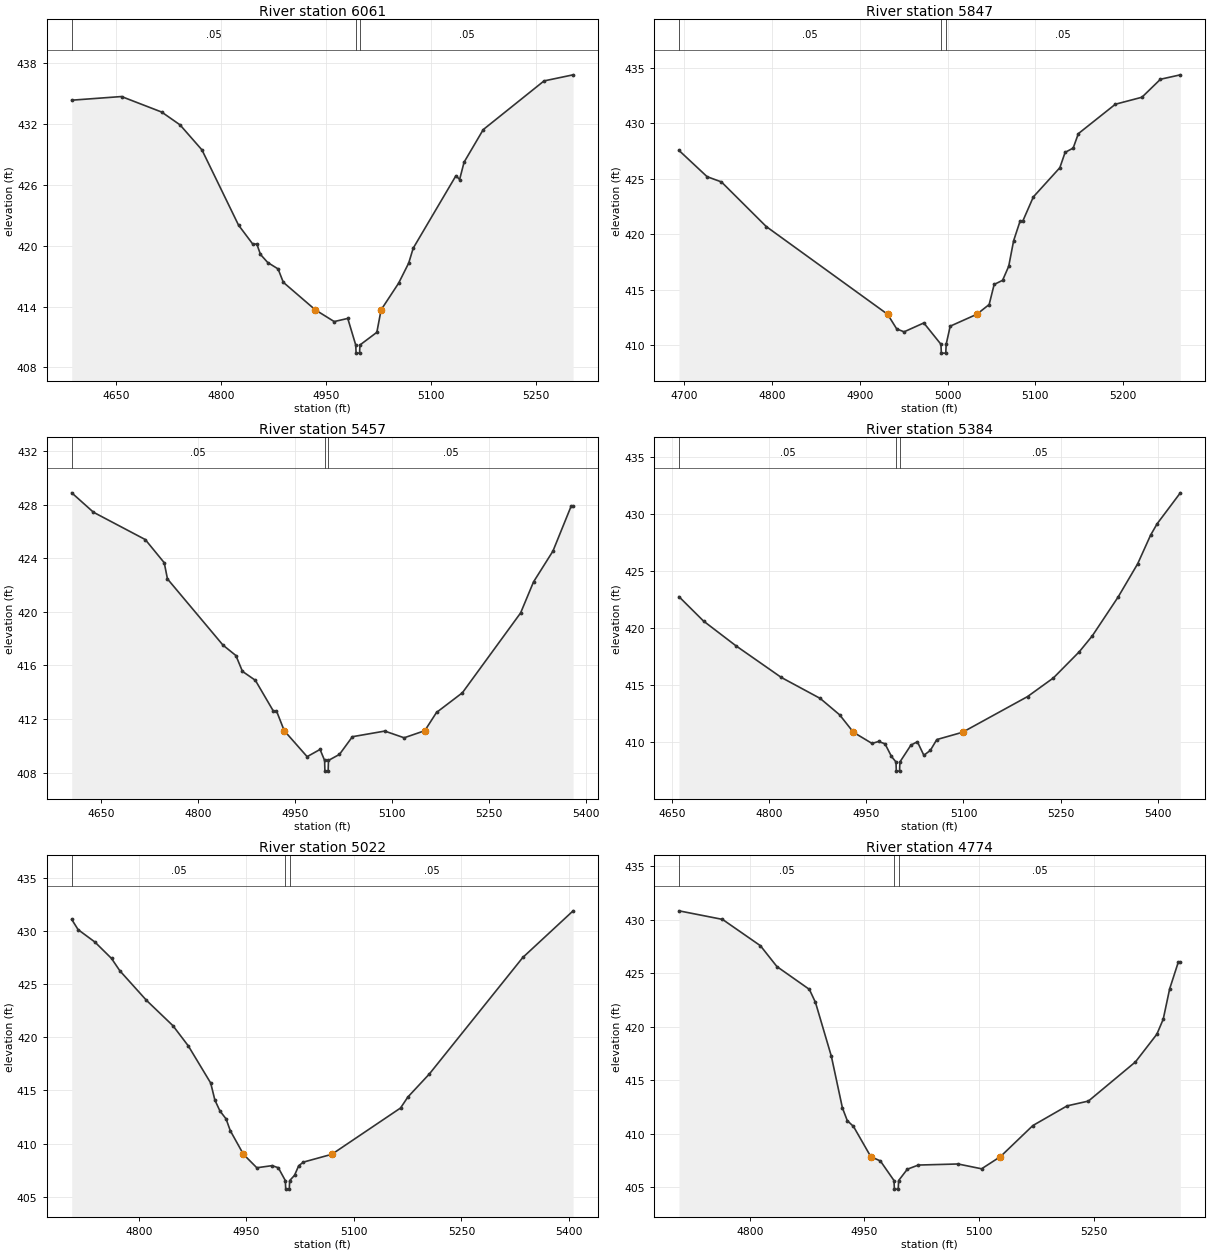
Type RM Length L Ch R = 1,6061,214,214,214
BEGIN DESCRIPTION:
UNT 093 in Running Cr Watershed 8.0
END DESCRIPTION:
XS GIS Cut Line= 3
      2892013.03      7038822.18      2891730.91      7038908.99
      2891325.04      7039024.99
#Sta/Elev= 30
  4586.4  434.34  4657.6  434.70  4715.1  433.17  4741.3  431.91  4772.7  429.44
  4825.0  422.03  4845.8  420.12  4851.1  420.18  4856.4  419.14  4866.8  418.34
  4881.6  417.71  4889.1  416.39  4934.8  413.68  4961.9  412.52  4981.3  412.83
  4992.7  410.21  4993.2  409.41  4998.2  409.41  4998.7  410.21  5022.9  411.46
  5029.0  413.68  5054.1  416.31  5068.5  418.29  5074.9  419.75  5136.1  426.90
  5141.3  426.52  5147.7  428.23  5175.1  431.44  5262.1  436.24  5303.7  436.84
#Mann=3,-1,0
  4586.4    0.05       0  4992.7    0.03       0  4998.7    0.05       0
Bank Sta=4934.8,5029
Exp/Cntr=0.3,0.1

Type RM Length L Ch R = 1,5847,390,390,390
BEGIN DESCRIPTION:
UNT 093 in Running Cr Watershed 7.0
END DESCRIPTION:
XS GIS Cut Line= 3
      2891803.59      7038608.26      2891454.47      7038786.76
      2891356.36      7038937.19
#Sta/Elev= 30
  4693.7  427.57  4725.8  425.20  4742.1  424.73  4793.2  420.71  4931.6  412.80
  4942.0  411.48  4950.4  411.22  4972.9  412.02  4992.4  410.10  4992.9  409.30
  4997.9  409.30  4998.4  410.10  5003.0  411.73  5033.3  412.80  5047.4  413.68
  5053.1  415.49  5062.7  415.86  5069.7  417.13  5075.3  419.43  5082.7  421.21
  5085.8  421.21  5097.8  423.38  5128.0  426.01  5134.0  427.39  5143.2  427.78
  5149.1  429.08  5191.3  431.73  5221.6  432.36  5242.7  433.98  5265.4  434.38
#Mann=3,-1,0
  4693.7    0.05       0  4992.4    0.03       0  4998.4    0.05       0
Bank Sta=4931.6,5033.3
Exp/Cntr=0.3,0.1

Type RM Length L Ch R = 1,5457,73,73,73
BEGIN DESCRIPTION:
UNT 093 in Running Cr Watershed 6.0
END DESCRIPTION:
XS GIS Cut Line= 3
      2891396.71      7038011.42      2891382.39      7038325.22
      2891387.60      7038786.17
#Sta/Elev= 30
  4605.1  428.89  4638.7  427.44  4718.8  425.40  4748.1  423.67  4753.1  422.46
  4838.9  417.52  4858.9  416.74  4869.0  415.56  4889.0  414.89  4916.6  412.61
  4921.6  412.61  4933.6  411.13  4969.0  409.19  4989.0  409.73  4996.0  408.91
  4996.5  408.11  5001.5  408.11  5002.0  408.91  5019.0  409.36  5039.0  410.68
  5089.0  411.10  5119.0  410.60  5150.9  411.13  5169.0  412.49  5209.0  413.96
  5299.0  419.92  5319.0  422.24  5349.0  424.54  5377.1  427.89  5380.2  427.89
#Mann=3,-1,0
  4605.1    0.05       0  4996.0    0.03       0  5002.0    0.05       0
Bank Sta=4933.6,5150.9
Exp/Cntr=0.3,0.1

Type RM Length L Ch R = 1,5384,362,362,362
BEGIN DESCRIPTION:
Mapping XS 38f8a59e
END DESCRIPTION:
XS GIS Cut Line= 3
      2891329.00      7038027.07      2891321.19      7038459.34
      2891322.49      7038800.90
#Sta/Elev= 30
  4660.9  422.76  4698.8  420.62  4748.8  418.45  4818.9  415.67  4878.9  413.83
  4908.9  412.39  4930.2  410.86  4958.9  409.88  4968.9  410.05  4978.9  409.85
  4988.9  408.74  4995.9  408.25  4996.4  407.45  5001.4  407.45  5001.9  408.25
  5018.9  409.73  5028.9  410.03  5038.9  408.84  5048.9  409.27  5058.9  410.22
  5098.6  410.86  5198.9  413.99  5238.9  415.63  5278.9  417.93  5298.9  419.32
  5338.9  422.74  5368.9  425.64  5388.9  428.16  5398.9  429.15  5434.8  431.87
#Mann=3,-1,0
  4660.9    0.05       0  4995.9    0.03       0  5001.9    0.05       0
Bank Sta=4930.2,5098.6
Exp/Cntr=0.3,0.1

Type RM Length L Ch R = 1,5022,248,248,248
BEGIN DESCRIPTION:
UNT 093 in Running Cr Watershed 5.0
END DESCRIPTION:
XS GIS Cut Line= 3
      2891231.35      7037877.31      2891046.45      7038188.50
      2891025.00      7038525.04
#Sta/Elev= 30
  4706.5  431.08  4715.4  430.12  4738.7  428.96  4762.0  427.41  4773.6  426.25
  4810.7  423.47  4847.7  421.08  4869.1  419.18  4900.3  415.69  4906.1  414.09
  4913.2  413.06  4921.7  412.32  4927.6  411.21  4945.9  408.99  4964.6  407.72
  4986.0  407.92  4994.6  407.72  5004.4  406.51  5004.9  405.71  5009.9  405.71
  5010.4  406.51  5017.2  407.01  5023.0  407.91  5029.5  408.25  5069.3  408.99
  5165.0  413.34  5175.2  414.37  5205.3  416.55  5335.5  427.50  5405.7  431.89
#Mann=3,-1,0
  4706.5    0.05       0  5004.4    0.03       0  5010.4    0.05       0
Bank Sta=4945.9,5069.3
Exp/Cntr=0.3,0.1

Type RM Length L Ch R = 1,4774,431,431,431
BEGIN DESCRIPTION:
UNT 093 in Running Cr Watershed 4.0
END DESCRIPTION:
XS GIS Cut Line= 3
      2891175.03      7037774.98      2890925.00      7037975.00
      2890775.00      7038275.00
#Sta/Elev= 30
  4707.5  430.82  4764.4  430.02  4814.0  427.56  4835.6  425.61  4878.0  423.48
  4886.0  422.26  4906.8  417.22  4921.2  412.41  4927.6  411.21  4935.7  410.67
  4958.3  407.85  4970.9  407.44  4988.7  405.61  4989.2  404.81  4994.2  404.81
  4994.7  405.61  5006.1  406.67  5020.5  407.06  5072.4  407.16  5103.2  406.71
  5127.9  407.85  5170.2  410.75  5215.0  412.59  5242.9  413.04  5304.4  416.70
  5332.4  419.29  5340.7  420.69  5349.1  423.52  5360.3  426.00  5363.1  426.00
#Mann=3,-1,0
  4707.5    0.05       0  4988.7    0.03       0  4994.7    0.05       0
Bank Sta=4958.3,5127.9
Exp/Cntr=0.3,0.1

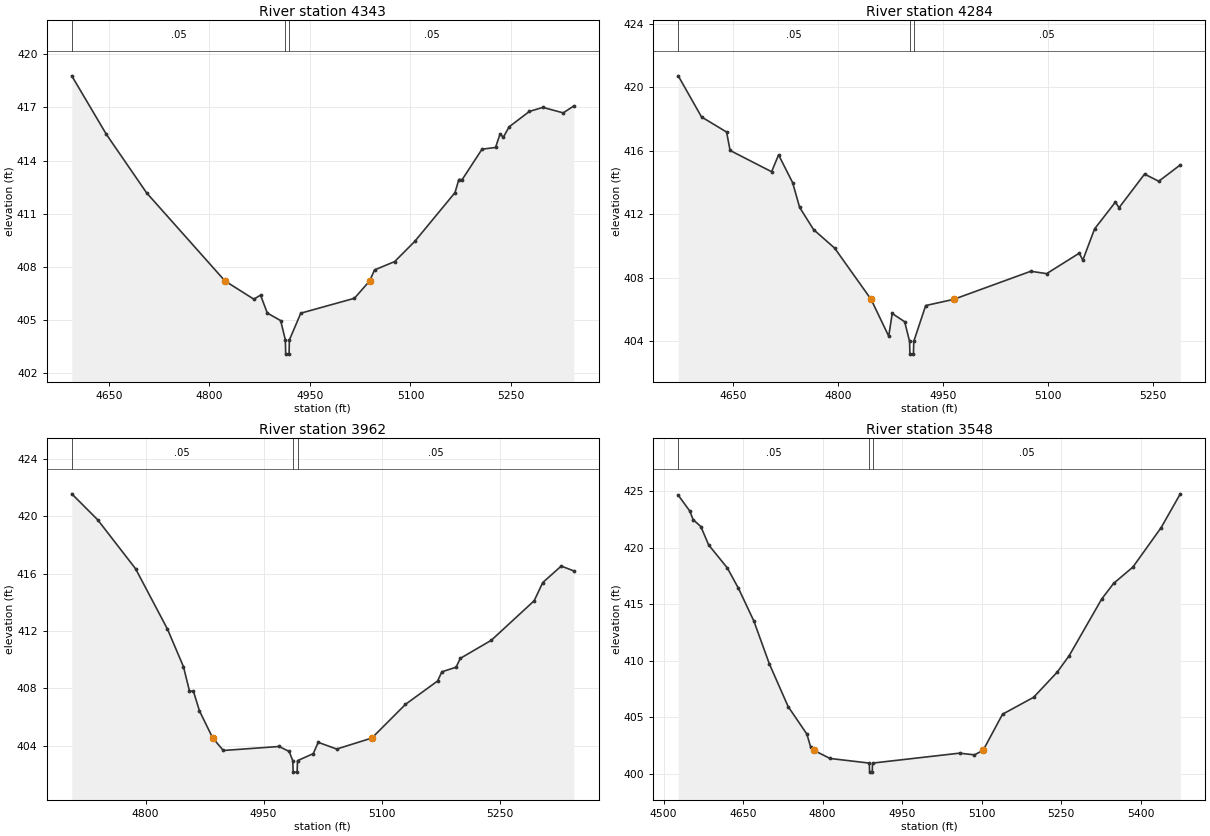
Type RM Length L Ch R = 1,4343,59,59,59
BEGIN DESCRIPTION:
Mapping XS b95cca0f
END DESCRIPTION:
XS GIS Cut Line= 4
      2890976.60      7037864.72      2890671.02      7037868.19
      2890398.45      7037868.19      2890229.20      7037845.74
#Sta/Elev= 30
  4594.8  418.78  4646.4  415.48  4706.4  412.18  4823.3  407.21  4866.4  406.18
  4876.4  406.41  4886.4  405.40  4906.4  404.97  4913.4  403.88  4913.9  403.08
  4918.9  403.08  4919.4  403.88  4936.4  405.39  5016.4  406.23  5039.1  407.21
  5046.4  407.83  5076.4  408.30  5106.4  409.44  5166.4  412.19  5172.2  412.93
  5177.2  412.93  5206.7  414.64  5226.9  414.74  5233.6  415.49  5238.6  415.32
  5247.1  415.90  5277.3  416.77  5297.5  417.00  5327.8  416.69  5343.7  417.08
#Mann=3,-1,0
  4594.8    0.05       0  4913.4    0.03       0  4919.4    0.05       0
Bank Sta=4823.3,5039.1
Exp/Cntr=0.3,0.1

Type RM Length L Ch R = 1,4284,322,322,322
BEGIN DESCRIPTION:
UNT 093 in Running Cr Watershed 3.0
END DESCRIPTION:
XS GIS Cut Line= 3
      2890978.30      7037797.01      2890452.27      7037819.58
      2890264.80      7037783.13
#Sta/Elev= 30
  4571.7  420.72  4605.0  418.13  4640.8  417.18  4645.8  416.02  4705.1  414.68
  4715.1  415.74  4735.2  413.99  4745.2  412.43  4765.2  411.03  4795.2  409.87
  4847.3  406.64  4872.5  404.32  4877.5  405.75  4895.3  405.23  4902.3  403.99
  4902.8  403.19  4907.8  403.19  4908.3  403.99  4925.3  406.25  4965.3  406.64
  5075.5  408.41  5098.2  408.26  5144.8  409.55  5149.9  409.11  5166.7  411.08
  5196.5  412.77  5201.6  412.41  5238.1  414.53  5258.4  414.08  5289.2  415.11
#Mann=3,-1,0
  4571.7    0.05       0  4902.3    0.03       0  4908.3    0.05       0
Bank Sta=4847.3,4965.3
Exp/Cntr=0.3,0.1

Type RM Length L Ch R = 1,3962,414,414,414
BEGIN DESCRIPTION:
UNT 093 in Running Cr Watershed 2.0
END DESCRIPTION:
XS GIS Cut Line= 3
      2890774.96      7037525.01      2890475.00      7037575.00
      2890168.81      7037707.92
#Sta/Elev= 30
  4706.3  421.57  4739.2  419.76  4787.4  416.34  4827.9  412.13  4848.2  409.51
  4855.8  407.82  4860.9  407.79  4868.5  406.43  4885.4  404.53  4898.9  403.66
  4969.8  403.94  4982.5  403.59  4987.1  402.95  4987.6  402.15  4992.6  402.15
  4993.1  402.95  5013.1  403.44  5019.4  404.23  5042.9  403.76  5087.6  404.53
  5130.3  406.88  5171.1  408.51  5176.5  409.15  5194.5  409.47  5200.0  410.09
  5239.3  411.35  5293.8  414.11  5304.7  415.38  5328.2  416.53  5344.2  416.19
#Mann=3,-1,0
  4706.3    0.05       0  4987.1    0.03       0  4993.1    0.05       0
Bank Sta=4885.4,5087.6
Exp/Cntr=0.3,0.1

Type RM Length L Ch R = 1,3548,0,0,0
BEGIN DESCRIPTION:
UNT 093 in Running Cr Watershed 1.0
END DESCRIPTION:
XS GIS Cut Line= 3
      2890624.98      7037025.01      2890225.00      7037325.00
      2890025.00      7037725.01
#Sta/Elev= 30
  4527.5  424.67  4549.4  423.26  4555.6  422.50  4570.2  421.89  4584.8  420.27
  4620.2  418.22  4641.0  416.43  4670.2  413.52  4699.4  409.73  4734.8  405.95
  4770.2  403.51  4777.5  402.33  4783.4  402.07  4813.9  401.35  4888.0  400.94
  4888.5  400.14  4893.5  400.14  4894.0  400.94  5058.2  401.82  5086.2  401.67
  5102.7  402.07  5139.3  405.27  5198.0  406.77  5242.7  409.01  5265.1  410.46
  5326.5  415.48  5348.9  416.86  5385.2  418.30  5438.4  421.79  5474.7  424.79
#Mann=3,-1,0
  4527.5    0.05       0  4888.0   0.033       0  4894.0    0.05       0
Bank Sta=4783.4,5102.7
Exp/Cntr=0.3,0.1

Chan Stop Cuts=-1