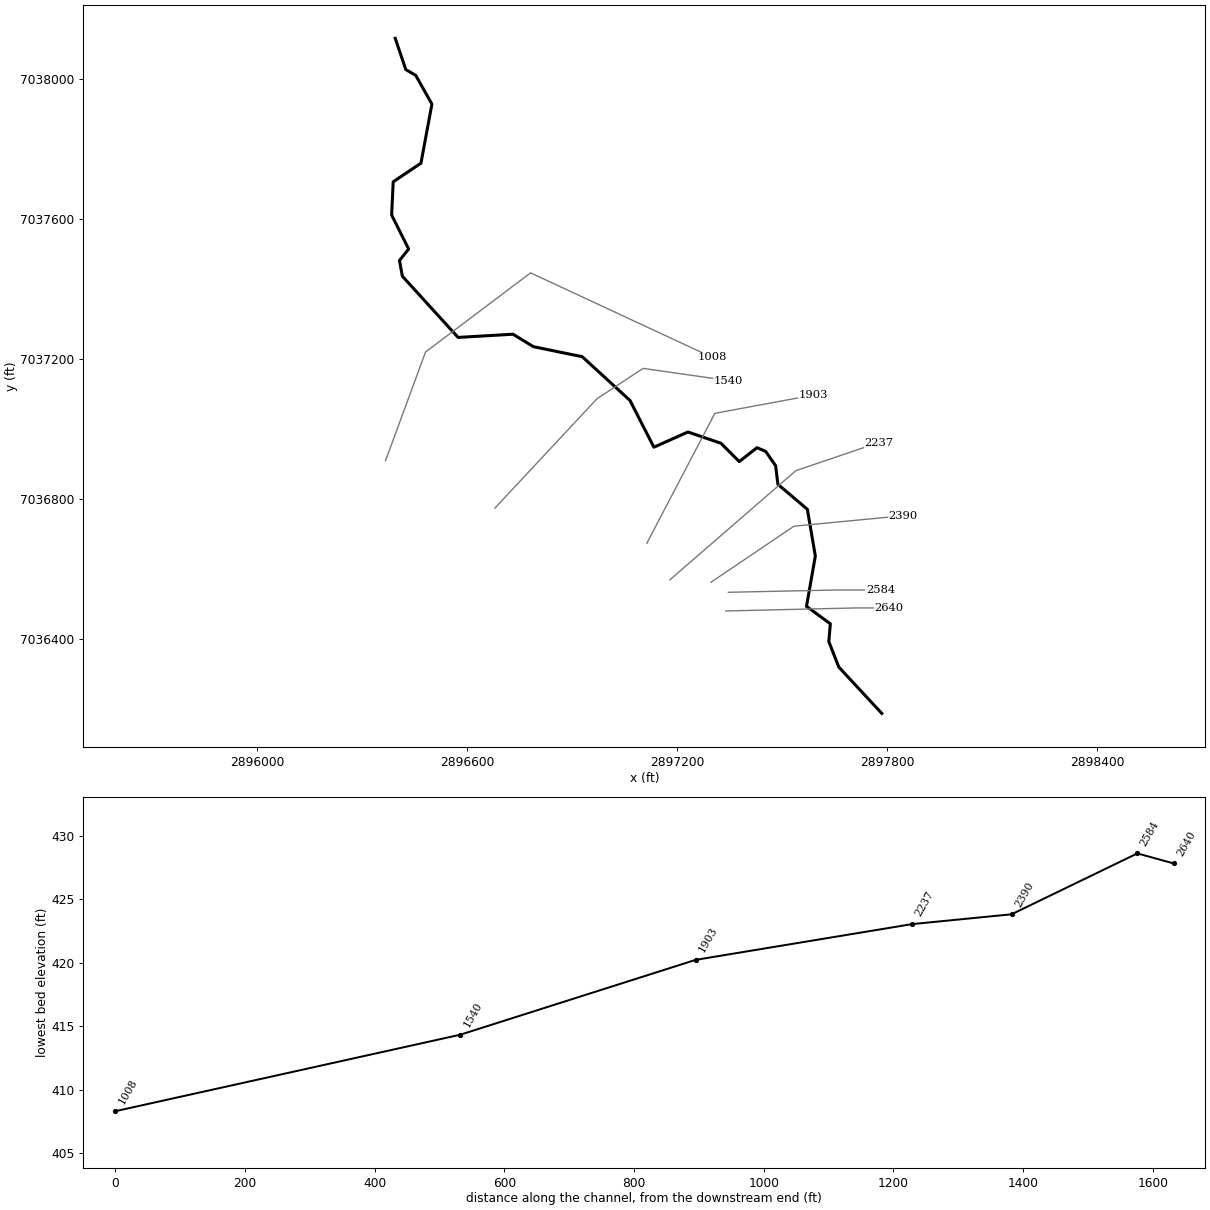
--- UNT 094 in Running Cr Watershed.prj (project) ---

Proj Title=UNT 094 in Running Cr Watershed Base Level Engineering
Current Plan=p01
Default Exp/Contr=0.3,0.1
English Units
Geom File=g01
Flow File=f01
Plan File=p01
BEGIN DESCRIPTION:
UNT 094 in Running Cr Watershed
END DESCRIPTION:

--- UNT 094 in Running Cr Watershed.p01 (plan) ---

Plan Title=Multiple Run
Short Identifier=Multiple
Geom File=g01
Flow File=f01
Subcritical Flow
K Sum by GR= 0
Std Step Tol= 0.01
Critical Tol= 0.01
Num of Std Step Trials= 20
Max Error Tol= 0.3
Flow Tol Ratio= 0.001
Split Flow NTrial= 30
Split Flow Tol= 0.02
Split Flow Ratio= 0.02
Log Output Level= 0
Friction Slope Method= 1
Unsteady Friction Slope Method= 2
Unsteady Bridges Friction Slope Method= 1
Parabolic Critical Depth
Global Vel Dist=  1 , 1 , 1
Global Log Level= 0
CheckData=True
Encroach Param= -1, 0, 0, 0
BEGIN DESCRIPTION:
Multiple Run
END DESCRIPTION:

--- UNT 094 in Running Cr Watershed.f01 (steady flow) ---

Flow Title=Multiple
Number of Profiles=7
Profile Names=10-year,25-year,50-year,1pct_min,100-year,1pct_plu,500-year
River Rch & RM= UNT 094 in Runni,Reach-1,2640
     221     281     328     191     382     762     516
Boundary for River Rch & Prof#=UNT 094 in Runni,Reach-1,1
Up Type=0
Dn Type=3
Dn Slope=0.005
Boundary for River Rch & Prof#=UNT 094 in Runni,Reach-1,2
Up Type=0
Dn Type=3
Dn Slope=0.005
Boundary for River Rch & Prof#=UNT 094 in Runni,Reach-1,3
Up Type=0
Dn Type=3
Dn Slope=0.005
Boundary for River Rch & Prof#=UNT 094 in Runni,Reach-1,4
Up Type=0
Dn Type=3
Dn Slope=0.005
Boundary for River Rch & Prof#=UNT 094 in Runni,Reach-1,5
Up Type=0
Dn Type=3
Dn Slope=0.005
Boundary for River Rch & Prof#=UNT 094 in Runni,Reach-1,6
Up Type=0
Dn Type=3
Dn Slope=0.005
Boundary for River Rch & Prof#=UNT 094 in Runni,Reach-1,7
Up Type=0
Dn Type=3
Dn Slope=0.005

--- UNT 094 in Running Cr Watershed.g01 (geometry) ---

Geom Title=Existing Conditions

River Reach=UNT 094 in Runni,Reach-1
Reach XY= 30
      2897784.11      7036186.24      2897661.38      7036318.44
      2897632.82      7036391.41      2897637.12      7036442.18
      2897569.04      7036491.98      2897594.28      7036635.78
      2897571.44      7036769.49      2897487.27      7036840.71
      2897480.85      7036893.72      2897452.41      7036934.75
      2897427.57      7036945.40      2897376.85      7036905.74
      2897324.63      7036958.03      2897230.25      7036990.26
      2897132.96      7036946.78      2897064.68      7037080.44
      2896928.28      7037205.34      2896788.82      7037234.02
      2896730.47      7037269.59      2896573.48      7037260.49
      2896414.28      7037435.38      2896406.06      7037480.23
      2896432.22      7037513.11      2896383.64      7037610.28
      2896388.13      7037705.20      2896467.35      7037758.26
      2896498.74      7037927.17      2896452.40      7038009.39
      2896424.00      7038025.83      2896393.92      7038115.06

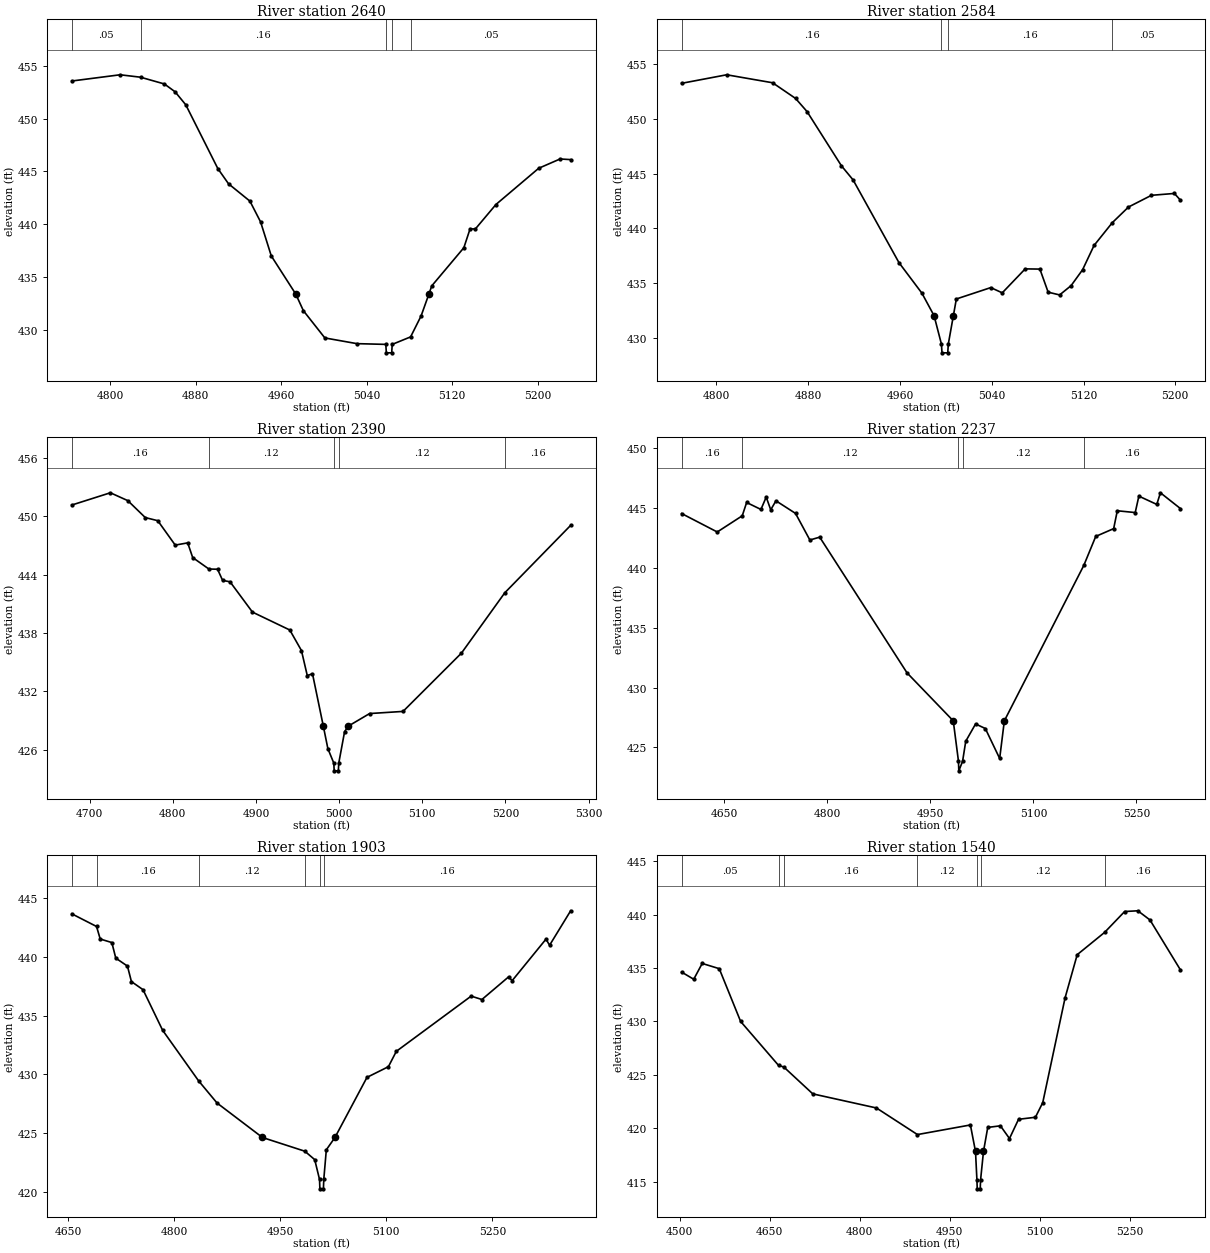
Type RM Length L Ch R = 1,2640,56,56,56
BEGIN DESCRIPTION:
UNT 094 in Running Cr Watershed 3.0
END DESCRIPTION:
XS GIS Cut Line= 3
      2897338.41      7036478.87      2897711.64      7036487.55
      2897804.91      7036487.55
#Sta/Elev= 30
  4764.2  453.56  4809.4  454.15  4828.5  453.92  4850.8  453.28  4860.8  452.54
  4870.8  451.31  4900.8  445.27  4910.8  443.83  4930.8  442.19  4940.8  440.22
  4950.8  437.00  4973.7  433.39  4980.8  431.82  5000.9  429.24  5030.9  428.70
  5057.9  428.63  5058.4  427.83  5063.4  427.83  5063.9  428.63  5081.1  429.34
  5090.9  431.32  5098.2  433.39  5100.9  434.17  5130.9  437.78  5136.7  439.56
  5141.7  439.56  5160.9  441.87  5200.9  445.30  5220.9  446.18  5230.8  446.12
#Mann=5,-1,0
  4764.2    0.05       0  4828.5    0.16       0  5057.9    0.07       0
  5063.9    0.16       0  5081.1    0.05       0
Bank Sta=4973.7,5098.2
Exp/Cntr=0.3,0.1

Type RM Length L Ch R = 1,2584,194,194,194
BEGIN DESCRIPTION:
Mapping XS 1d5496fa
END DESCRIPTION:
XS GIS Cut Line= 3
      2897345.68      7036532.25      2897655.54      7036538.76
      2897780.31      7036538.76
#Sta/Elev= 30
  4769.8  453.24  4809.1  454.02  4849.1  453.29  4869.1  451.86  4879.1  450.66
  4909.1  445.70  4919.2  444.42  4959.2  436.86  4979.2  434.07  4989.8  432.01
  4996.2  429.42  4996.7  428.62  5001.7  428.62  5002.2  429.42  5006.6  432.01
  5009.2  433.54  5039.2  434.58  5049.2  434.10  5069.2  436.29  5082.0  436.27
  5089.2  434.16  5099.2  433.91  5109.2  434.76  5119.2  436.21  5129.2  438.43
  5145.1  440.51  5159.2  441.94  5179.2  443.01  5199.2  443.18  5204.5  442.56
#Mann=4,-1,0
  4769.8    0.16       0  4996.2    0.07       0  5002.2    0.16       0
  5145.1    0.05       0
Bank Sta=4989.8,5006.6
Exp/Cntr=0.3,0.1

Type RM Length L Ch R = 1,2390,153,153,153
BEGIN DESCRIPTION:
Mapping XS 7b8e0a43
END DESCRIPTION:
XS GIS Cut Line= 3
      2897296.14      7036560.88      2897533.14      7036721.05
      2897845.66      7036751.00
#Sta/Elev= 30
  4678.5  451.15  4724.9  452.41  4745.9  451.60  4766.9  449.86  4781.9  449.54
  4802.9  447.03  4817.9  447.26  4823.9  445.75  4843.4  444.57  4853.8  444.55
  4859.9  443.40  4868.8  443.26  4895.8  440.14  4940.7  438.30  4954.7  436.19
  4961.7  433.62  4968.0  433.80  4981.0  428.42  4986.5  426.10  4993.6  424.62
  4994.1  423.82  4999.1  423.82  4999.6  424.62  5006.6  427.85  5011.1  428.42
  5036.7  429.71  5076.9  429.93  5147.2  435.93  5199.3  442.13  5278.5  449.06
#Mann=5,-1,0
  4678.5    0.16       0  4843.4    0.12       0  4993.6    0.07       0
  4999.6    0.12       0  5199.3    0.16       0
Bank Sta=4981,5011.1
Exp/Cntr=0.3,0.1

Type RM Length L Ch R = 1,2237,334,334,334
BEGIN DESCRIPTION:
UNT 094 in Running Cr Watershed 2.0
END DESCRIPTION:
XS GIS Cut Line= 3
      2897178.64      7036567.83      2897538.59      7036879.76
      2897775.54      7036960.09
#Sta/Elev= 30
  4587.7  444.51  4639.6  442.97  4676.0  444.32  4682.4  445.43  4703.2  444.85
  4710.9  445.88  4717.5  444.82  4725.1  445.57  4753.6  444.52  4774.5  442.30
  4788.8  442.54  4916.0  431.22  4983.3  427.22  4990.9  423.85  4991.4  423.05
  4996.9  423.85  5001.5  425.52  5015.8  426.96  5030.0  426.58  5050.9  424.08
  5057.7  427.22  5173.4  440.18  5190.8  442.60  5216.9  443.25  5222.2  444.74
  5248.3  444.59  5253.6  445.96  5279.7  445.27  5285.0  446.24  5314.2  444.92
#Mann=5,-1,0
  4587.7    0.16       0  4676.0    0.12       0  4990.9    0.07       0
  4996.9    0.12       0  5173.4    0.16       0
Bank Sta=4983.3,5057.7
Exp/Cntr=0.3,0.1

Type RM Length L Ch R = 1,1903,363,363,363
BEGIN DESCRIPTION:
Mapping XS ec2e4088
END DESCRIPTION:
XS GIS Cut Line= 3
      2897112.66      7036671.97      2897307.12      7037043.54
      2897588.36      7037095.62
#Sta/Elev= 30
  4655.2  443.69  4690.2  442.61  4695.4  441.54  4711.8  441.24  4717.4  439.91
  4733.9  439.23  4739.5  437.91  4755.9  437.22  4783.6  433.76  4834.4  429.45
  4860.6  427.55  4924.8  424.61  4984.7  423.44  4998.7  422.72  5005.5  421.03
  5006.0  420.23  5011.0  420.23  5011.5  421.03  5015.1  423.56  5027.3  424.61
  5072.6  429.74  5102.9  430.65  5114.1  431.96  5219.9  436.67  5235.1  436.38
  5272.8  438.31  5277.9  437.99  5325.7  441.53  5330.8  441.01  5360.6  443.95
#Mann=6,-1,0
  4655.2    0.12       0  4690.2    0.16       0  4834.4    0.12       0
  4984.7    0.16       0  5005.5    0.07       0  5011.5    0.16       0
Bank Sta=4924.8,5027.3
Exp/Cntr=0.3,0.1

Type RM Length L Ch R = 1,1540,532,532,532
BEGIN DESCRIPTION:
Mapping XS 4e6bef7a
END DESCRIPTION:
XS GIS Cut Line= 4
      2896678.64      7036772.69      2896970.32      7037085.20
      2897102.26      7037172.01      2897345.27      7037137.29
#Sta/Elev= 30
  4503.5  434.62  4523.7  433.95  4537.8  435.43  4566.2  434.94  4601.8  430.00
  4664.9  425.89  4673.8  425.73  4722.0  423.22  4828.0  421.90  4896.3  419.41
  4984.5  420.31  4993.0  417.83  4995.4  415.13  4995.9  414.33  5000.9  414.33
  5001.4  415.13  5006.3  417.83  5013.4  420.08  5034.5  420.23  5049.6  419.04
  5064.7  420.84  5092.8  421.03  5105.0  422.40  5142.2  432.21  5162.4  436.25
  5208.1  438.34  5241.4  440.29  5263.4  440.36  5283.6  439.50  5334.4  434.82
#Mann=7,-1,0
  4503.5    0.05       0  4664.9    0.08       0  4673.8    0.16       0
  4896.3    0.12       0  4995.4    0.07       0  5001.4    0.12       0
  5208.1    0.16       0
Bank Sta=4993,5006.3
Exp/Cntr=0.3,0.1

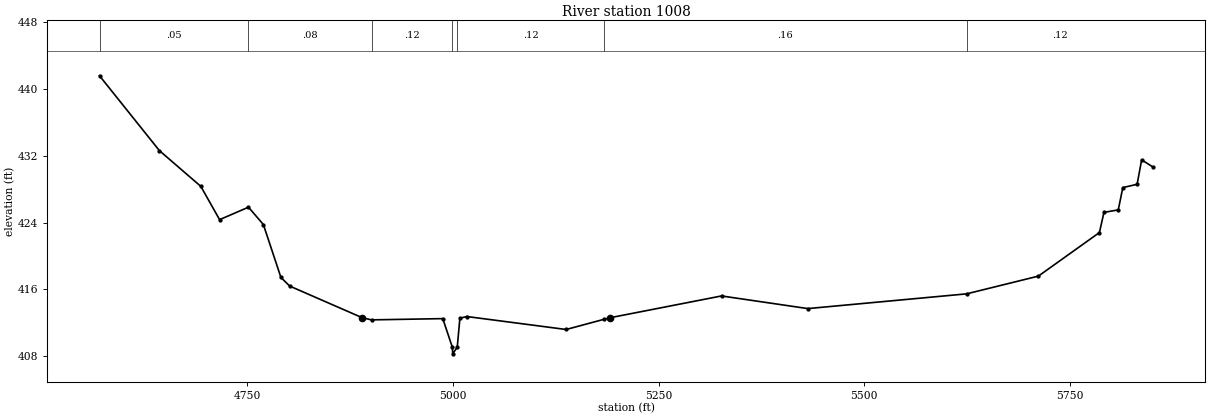
Type RM Length L Ch R = 1,1008,0,0,0
BEGIN DESCRIPTION:
UNT 094 in Running Cr Watershed 1.0
END DESCRIPTION:
XS GIS Cut Line= 4
      2896366.15      7036908.12      2896480.42      7037218.70
      2896780.60      7037444.95      2897300.11      7037203.29
#Sta/Elev= 30
  4570.7  441.54  4643.5  432.59  4693.8  428.32  4716.6  424.34  4751.7  425.83
  4769.8  423.76  4791.1  417.44  4801.8  416.40  4889.9  412.62  4901.2  412.36
  4987.8  412.51  4999.4  409.10  4999.9  408.30  5005.4  409.10  5008.6  412.56
  5017.0  412.76  5137.7  411.21  5183.8  412.43  5191.3  412.62  5326.5  415.22
  5431.4  413.71  5624.3  415.47  5711.5  417.59  5785.7  422.80  5791.2  425.21
  5808.6  425.51  5814.1  428.17  5831.5  428.57  5837.0  431.49  5850.5  430.65
#Mann=7,-1,0
  4570.7    0.05       0  4751.7    0.08       0  4901.2    0.12       0
  4999.4    0.07       0  5005.4    0.12       0  5183.8    0.16       0
  5624.3    0.12       0
Bank Sta=4889.9,5191.3
Exp/Cntr=0.3,0.1

Chan Stop Cuts=-1