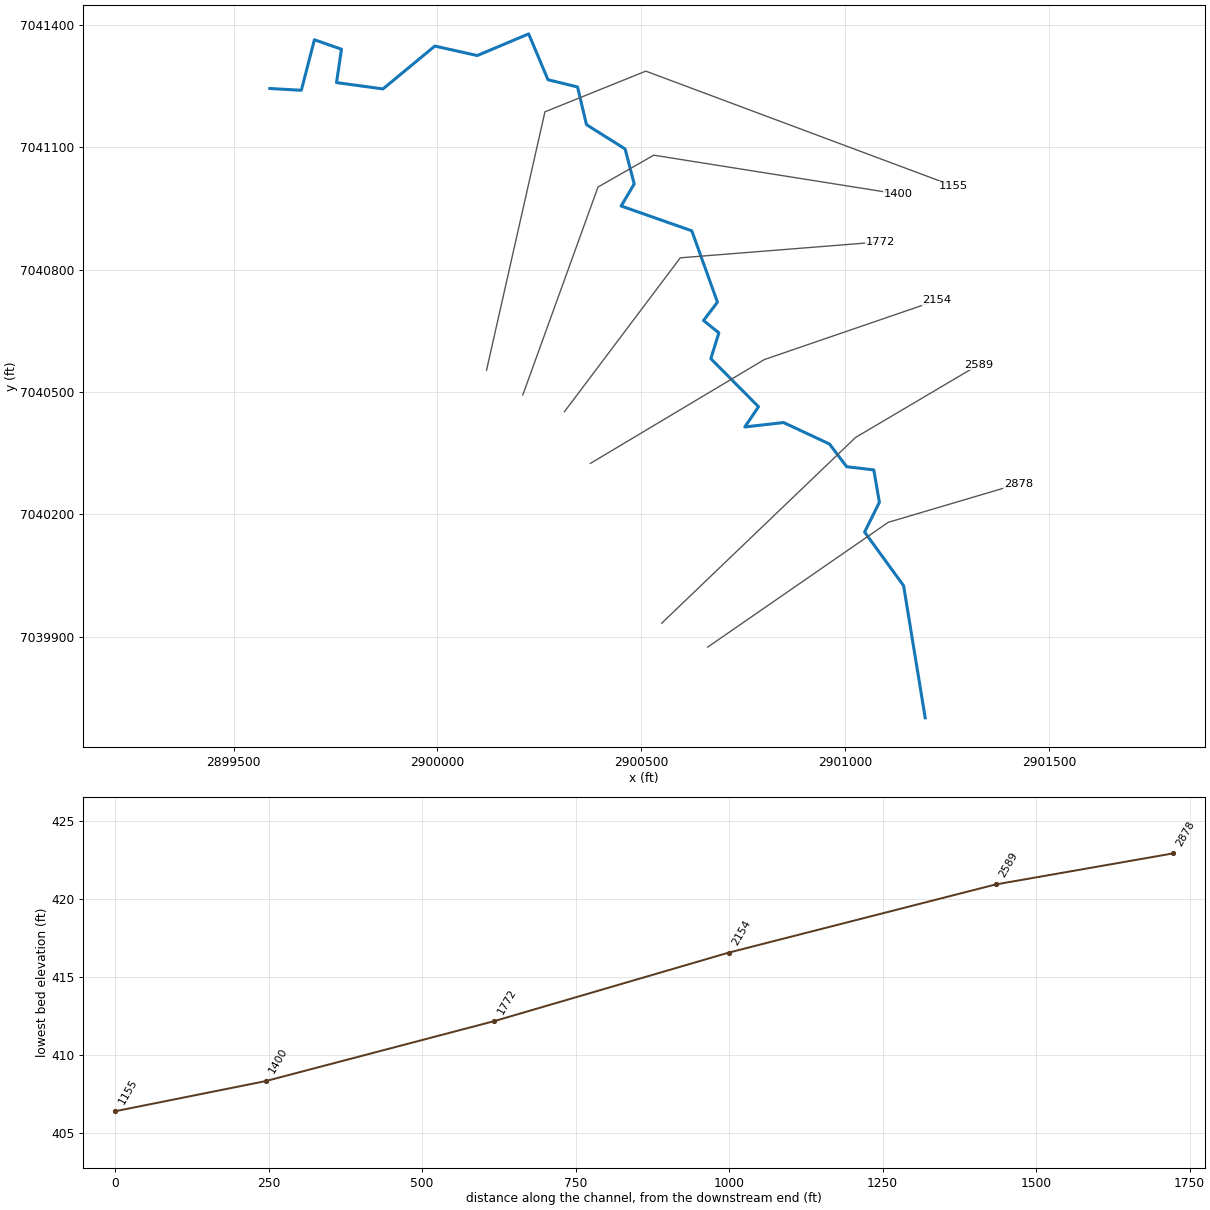
--- UNT 095 in Running Cr Watershed.prj (project) ---

Proj Title=UNT 095 in Running Cr Watershed Base Level Engineering
Current Plan=p01
Default Exp/Contr=0.3,0.1
English Units
Geom File=g01
Flow File=f01
Plan File=p01
BEGIN DESCRIPTION:
UNT 095 in Running Cr Watershed
END DESCRIPTION:

--- UNT 095 in Running Cr Watershed.p01 (plan) ---

Plan Title=Multiple Run
Short Identifier=Multiple
Geom File=g01
Flow File=f01
Subcritical Flow
K Sum by GR= 0
Std Step Tol= 0.01
Critical Tol= 0.01
Num of Std Step Trials= 20
Max Error Tol= 0.3
Flow Tol Ratio= 0.001
Split Flow NTrial= 30
Split Flow Tol= 0.02
Split Flow Ratio= 0.02
Log Output Level= 0
Friction Slope Method= 1
Unsteady Friction Slope Method= 2
Unsteady Bridges Friction Slope Method= 1
Parabolic Critical Depth
Global Vel Dist=  1 , 1 , 1
Global Log Level= 0
CheckData=True
Encroach Param= -1, 0, 0, 0
BEGIN DESCRIPTION:
Multiple Run
END DESCRIPTION:

--- UNT 095 in Running Cr Watershed.f01 (steady flow) ---

Flow Title=Multiple
Number of Profiles=7
Profile Names=10-year,25-year,50-year,1pct_min,100-year,1pct_plu,500-year
River Rch & RM= UNT 095 in Runni,Reach-1,2878
     435     578     694     415     829    1653    1181
Boundary for River Rch & Prof#=UNT 095 in Runni,Reach-1,1
Up Type=0
Dn Type=3
Dn Slope=0.005
Boundary for River Rch & Prof#=UNT 095 in Runni,Reach-1,2
Up Type=0
Dn Type=3
Dn Slope=0.005
Boundary for River Rch & Prof#=UNT 095 in Runni,Reach-1,3
Up Type=0
Dn Type=3
Dn Slope=0.005
Boundary for River Rch & Prof#=UNT 095 in Runni,Reach-1,4
Up Type=0
Dn Type=3
Dn Slope=0.005
Boundary for River Rch & Prof#=UNT 095 in Runni,Reach-1,5
Up Type=0
Dn Type=3
Dn Slope=0.005
Boundary for River Rch & Prof#=UNT 095 in Runni,Reach-1,6
Up Type=0
Dn Type=3
Dn Slope=0.005
Boundary for River Rch & Prof#=UNT 095 in Runni,Reach-1,7
Up Type=0
Dn Type=3
Dn Slope=0.005

--- UNT 095 in Running Cr Watershed.g01 (geometry) ---

Geom Title=Existing Conditions

River Reach=UNT 095 in Runni,Reach-1
Reach XY= 30
      2901196.30      7039700.99      2901143.37      7040024.95
      2901047.69      7040156.71      2901083.99      7040229.70
      2901070.19      7040309.10      2901003.64      7040316.93
      2900961.60      7040372.57      2900848.86      7040425.27
      2900753.86      7040414.44      2900787.49      7040463.97
      2900670.48      7040581.97      2900690.23      7040645.26
      2900652.59      7040675.47      2900686.73      7040720.59
      2900623.76      7040895.62      2900450.50      7040956.41
      2900482.50      7041010.53      2900460.22      7041096.41
      2900365.53      7041155.89      2900343.47      7041248.43
      2900271.04      7041266.15      2900223.61      7041378.58
      2900097.49      7041325.48      2899993.50      7041348.71
      2899866.27      7041243.61      2899752.32      7041259.10
      2899764.49      7041340.97      2899698.12      7041364.20
      2899666.03      7041240.29      2899588.70      7041244.70

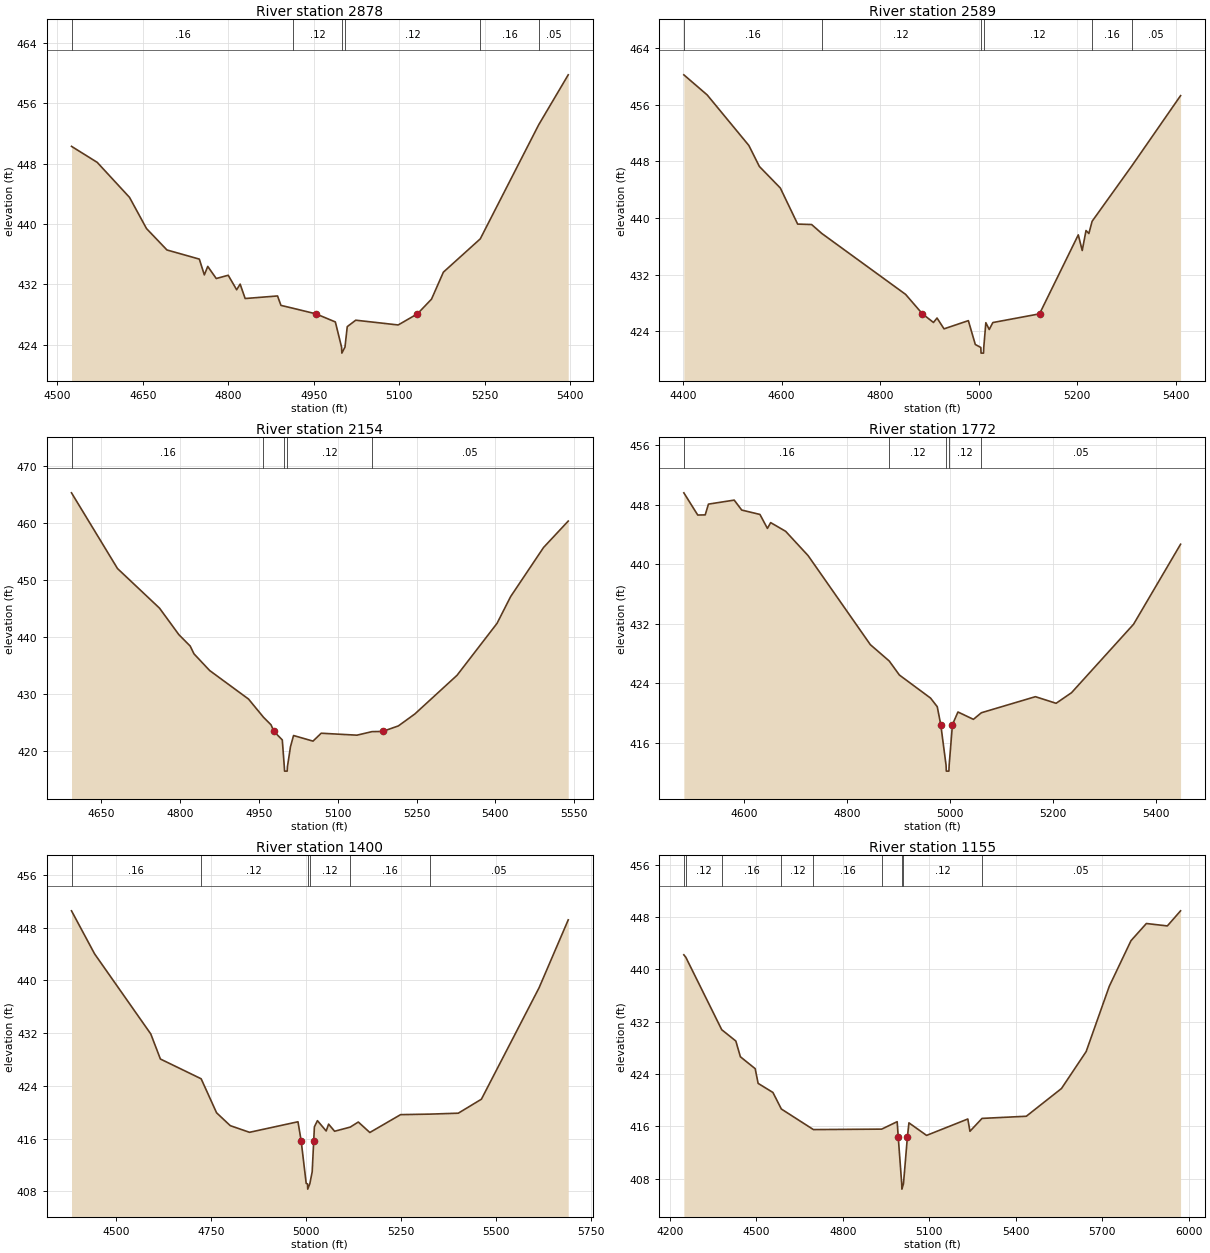
Type RM Length L Ch R = 1,2878,289,289,289
BEGIN DESCRIPTION:
UNT 095 in Running Cr Watershed 4.0
END DESCRIPTION:
XS GIS Cut Line= 3
      2900662.84      7039874.46      2901105.56      7040180.46
      2901424.98      7040274.99
#Sta/Elev= 30
  4525.1  450.29  4570.2  448.17  4626.9  443.53  4656.7  439.40  4692.5  436.57
  4749.3  435.36  4758.1  433.27  4764.1  434.39  4779.0  432.79  4800.0  433.22
  4814.8  431.30  4820.9  432.05  4829.7  430.14  4886.5  430.48  4892.5  429.23
  4914.3  428.84  4953.9  428.11  4987.9  427.04  4998.8  423.71  4999.3  422.91
  5004.8  423.71  5008.8  426.42  5023.7  427.27  5098.1  426.64  5131.9  428.11
  5156.6  430.06  5177.4  433.63  5242.1  438.04  5344.7  453.16  5396.4  459.76
#Mann=6,-1,0
  4525.1    0.16       0  4914.3    0.12       0  4998.8    0.07       0
  5004.8    0.12       0  5242.1    0.16       0  5344.7    0.05       0
Bank Sta=4953.9,5131.9
Exp/Cntr=0.3,0.1

Type RM Length L Ch R = 1,2589,435,435,435
BEGIN DESCRIPTION:
UNT 095 in Running Cr Watershed 3.0
END DESCRIPTION:
XS GIS Cut Line= 3
      2900550.03      7039933.08      2901025.50      7040388.70
      2901326.91      7040566.74
#Sta/Elev= 30
  4401.5  460.24  4448.9  457.40  4533.5  450.26  4554.9  447.29  4597.4  444.25
  4632.6  439.15  4660.9  439.09  4681.4  437.84  4851.8  429.22  4885.9  426.47
  4908.4  425.25  4915.6  425.88  4929.8  424.35  4979.2  425.51  4993.3  422.14
  5004.5  421.72  5005.0  420.92  5010.0  420.92  5010.5  421.72  5014.7  425.22
  5021.6  424.26  5028.9  425.24  5123.7  426.47  5202.4  437.63  5210.4  435.42
  5218.1  438.24  5223.9  437.82  5230.5  439.55  5311.5  447.41  5410.1  457.30
#Mann=6,-1,0
  4401.5    0.16       0  4681.4    0.12       0  5004.5    0.07       0
  5010.5    0.12       0  5230.5    0.16       0  5311.5    0.05       0
Bank Sta=4885.9,5123.7
Exp/Cntr=0.3,0.1

Type RM Length L Ch R = 1,2154,382,382,382
BEGIN DESCRIPTION:
UNT 095 in Running Cr Watershed 2.0
END DESCRIPTION:
XS GIS Cut Line= 3
      2900375.02      7040325.01      2900801.74      7040579.76
      2901225.03      7040725.01
#Sta/Elev= 30
  4594.0  465.24  4681.5  451.99  4761.3  445.07  4798.3  440.41  4819.7  438.43
  4826.9  437.07  4856.7  434.15  4930.6  429.16  4959.0  425.98  4973.4  424.65
  4979.0  423.49  4994.8  422.01  4998.6  417.35  4999.1  416.55  5004.1  416.55
  5004.6  417.35  5010.4  420.83  5016.2  422.78  5053.2  421.80  5068.8  423.18
  5136.7  422.84  5165.4  423.46  5185.5  423.49  5215.5  424.46  5246.7  426.54
  5327.0  433.31  5403.1  442.40  5429.0  447.09  5491.6  455.68  5538.5  460.30
#Mann=5,-1,0
  4594.0    0.16       0  4959.0    0.12       0  4998.6    0.07       0
  5004.6    0.12       0  5165.4    0.05       0
Bank Sta=4979,5185.5
Exp/Cntr=0.3,0.1

Type RM Length L Ch R = 1,1772,372,372,372
BEGIN DESCRIPTION:
Mapping XS 4e3b3768
END DESCRIPTION:
XS GIS Cut Line= 3
      2900311.30      7040451.74      2900595.58      7040829.33
      2901085.98      7040868.39
#Sta/Elev= 30
  4483.2  449.62  4510.2  446.63  4524.7  446.65  4531.0  448.10  4581.0  448.64
  4595.6  447.30  4631.0  446.71  4645.5  444.83  4651.8  445.61  4680.9  444.44
  4724.6  441.16  4845.4  429.18  4882.1  426.98  4901.7  425.10  4962.3  421.99
  4975.3  420.83  4982.1  418.42  4992.4  412.96  4992.9  412.16  4997.9  412.16
  4998.4  412.96  5004.8  418.42  5015.5  420.12  5045.5  419.13  5061.0  420.02
  5165.9  422.18  5206.1  421.29  5236.1  422.72  5356.5  431.93  5447.8  442.70
#Mann=5,-1,0
  4483.2    0.16       0  4882.1    0.12       0  4992.4    0.07       0
  4998.4    0.12       0  5061.0    0.05       0
Bank Sta=4982.1,5004.8
Exp/Cntr=0.3,0.1

Type RM Length L Ch R = 1,1400,245,245,245
BEGIN DESCRIPTION:
Mapping XS 9fa0000e
END DESCRIPTION:
XS GIS Cut Line= 4
      2900209.31      7040493.00      2900393.75      7041002.94
      2900530.47      7041081.07      2901130.81      7040985.71
#Sta/Elev= 30
  4382.3  450.54  4443.0  444.02  4591.0  431.86  4616.3  428.06  4723.6  425.06
  4764.2  419.90  4800.2  417.95  4850.9  416.94  4978.5  418.54  4986.8  415.67
  5000.1  409.18  5003.6  409.12  5004.1  408.32  5009.6  409.12  5015.9  410.96
  5019.9  415.67  5021.7  417.77  5029.7  418.71  5052.7  417.14  5059.1  418.18
  5074.9  417.10  5116.0  417.73  5137.3  418.50  5167.6  416.91  5248.6  419.62
  5327.0  419.70  5400.5  419.84  5461.3  421.96  5613.1  438.86  5689.9  449.17
#Mann=6,-1,0
  4382.3    0.16       0  4723.6    0.12       0  5003.6    0.07       0
  5009.6    0.12       0  5116.0    0.16       0  5327.0    0.05       0
Bank Sta=4986.8,5019.9
Exp/Cntr=0.3,0.1

Type RM Length L Ch R = 1,1155,0,0,0
BEGIN DESCRIPTION:
UNT 095 in Running Cr Watershed 1.0
END DESCRIPTION:
XS GIS Cut Line= 4
      2900120.32      7040553.73      2900263.55      7041187.40
      2900510.94      7041287.23      2901266.14      7041005.12
#Sta/Elev= 30
  4248.4  442.24  4255.3  441.86  4379.8  430.78  4428.7  429.05  4444.5  426.64
  4495.8  424.82  4506.0  422.57  4557.3  421.18  4586.5  418.65  4697.8  415.50
  4934.6  415.57  4988.2  416.71  4991.9  414.38  5004.0  407.19  5004.5  406.39
  5010.0  407.19  5023.7  414.38  5029.0  416.53  5090.2  414.61  5233.2  417.12
  5240.6  415.24  5282.5  417.21  5436.0  417.54  5557.9  421.78  5643.5  427.43
  5723.7  437.42  5799.0  444.40  5852.4  447.03  5925.1  446.66  5971.0  448.97
#Mann=9,-1,0
  4248.4    0.16       0  4255.3    0.12       0  4379.8    0.16       0
  4586.5    0.12       0  4697.8    0.16       0  4934.6    0.12       0
  5004.0    0.07       0  5010.0    0.12       0  5282.5    0.05       0
Bank Sta=4991.9,5023.7
Exp/Cntr=0.3,0.1

Chan Stop Cuts=-1