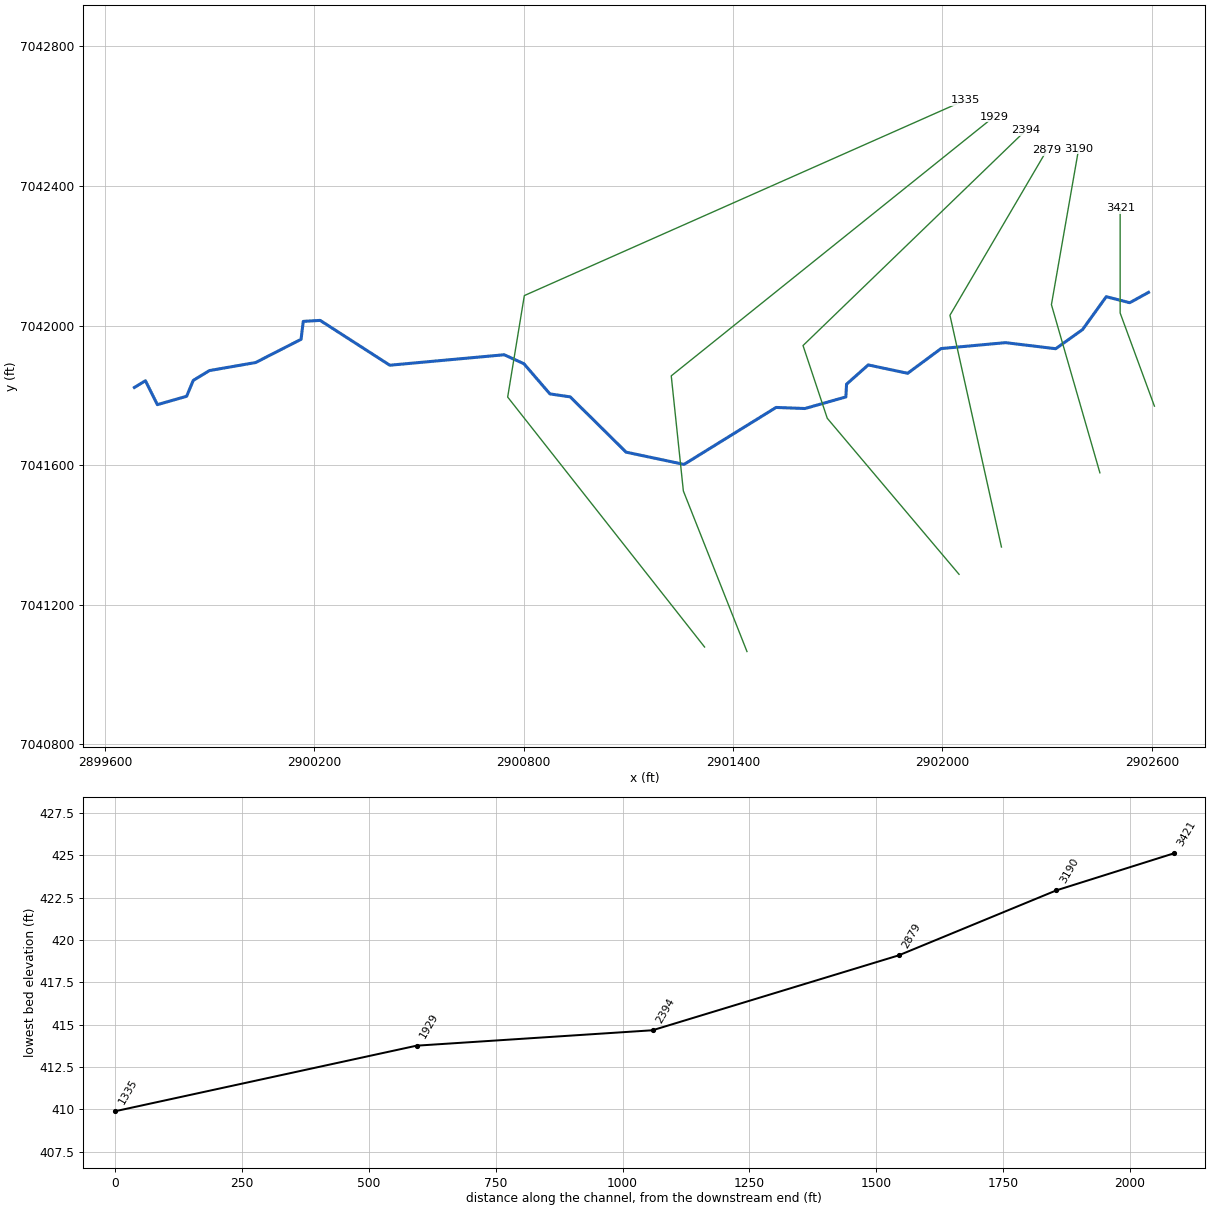
--- UNT 096 in Running Cr Watershed.prj (project) ---

Proj Title=UNT 096 in Running Cr Watershed Base Level Engineering
Current Plan=p01
Default Exp/Contr=0.3,0.1
English Units
Geom File=g01
Flow File=f01
Plan File=p01
BEGIN DESCRIPTION:
UNT 096 in Running Cr Watershed
END DESCRIPTION:

--- UNT 096 in Running Cr Watershed.p01 (plan) ---

Plan Title=Multiple Run
Short Identifier=Multiple
Geom File=g01
Flow File=f01
Subcritical Flow
K Sum by GR= 0
Std Step Tol= 0.01
Critical Tol= 0.01
Num of Std Step Trials= 20
Max Error Tol= 0.3
Flow Tol Ratio= 0.001
Split Flow NTrial= 30
Split Flow Tol= 0.02
Split Flow Ratio= 0.02
Log Output Level= 0
Friction Slope Method= 1
Unsteady Friction Slope Method= 2
Unsteady Bridges Friction Slope Method= 1
Parabolic Critical Depth
Global Vel Dist=  1 , 1 , 1
Global Log Level= 0
CheckData=True
Encroach Param= -1, 0, 0, 0
BEGIN DESCRIPTION:
Multiple Run
END DESCRIPTION:

--- UNT 096 in Running Cr Watershed.f01 (steady flow) ---

Flow Title=Multiple
Number of Profiles=7
Profile Names=10-year,25-year,50-year,1pct_min,100-year,1pct_plu,500-year
River Rch & RM= UNT 096 in Runni,Reach-1,3421
     502     671     809     486     969    1934    1392
Boundary for River Rch & Prof#=UNT 096 in Runni,Reach-1,1
Up Type=0
Dn Type=3
Dn Slope=0.005
Boundary for River Rch & Prof#=UNT 096 in Runni,Reach-1,2
Up Type=0
Dn Type=3
Dn Slope=0.005
Boundary for River Rch & Prof#=UNT 096 in Runni,Reach-1,3
Up Type=0
Dn Type=3
Dn Slope=0.005
Boundary for River Rch & Prof#=UNT 096 in Runni,Reach-1,4
Up Type=0
Dn Type=3
Dn Slope=0.005
Boundary for River Rch & Prof#=UNT 096 in Runni,Reach-1,5
Up Type=0
Dn Type=3
Dn Slope=0.005
Boundary for River Rch & Prof#=UNT 096 in Runni,Reach-1,6
Up Type=0
Dn Type=3
Dn Slope=0.005
Boundary for River Rch & Prof#=UNT 096 in Runni,Reach-1,7
Up Type=0
Dn Type=3
Dn Slope=0.005

--- UNT 096 in Running Cr Watershed.g01 (geometry) ---

Geom Title=Existing Conditions

River Reach=UNT 096 in Runni,Reach-1
Reach XY= 30
      2902590.29      7042094.94      2902536.50      7042065.40
      2902469.28      7042082.64      2902401.41      7041988.52
      2902324.51      7041933.58      2902180.53      7041950.93
      2901995.88      7041933.98      2901900.22      7041863.17
      2901787.20      7041887.12      2901725.09      7041831.96
      2901723.11      7041795.40      2901605.81      7041762.24
      2901523.14      7041765.32      2901259.38      7041602.10
      2901093.31      7041637.20      2900933.23      7041795.56
      2900875.02      7041804.12      2900800.54      7041890.58
      2900744.05      7041916.26      2900416.18      7041886.30
      2900216.73      7042014.71      2900168.21      7042011.91
      2900161.98      7041960.50      2900031.82      7041894.01
      2899899.14      7041870.89      2899852.91      7041842.64
      2899834.08      7041797.27      2899750.19      7041773.31
      2899715.95      7041841.79      2899684.43      7041822.58

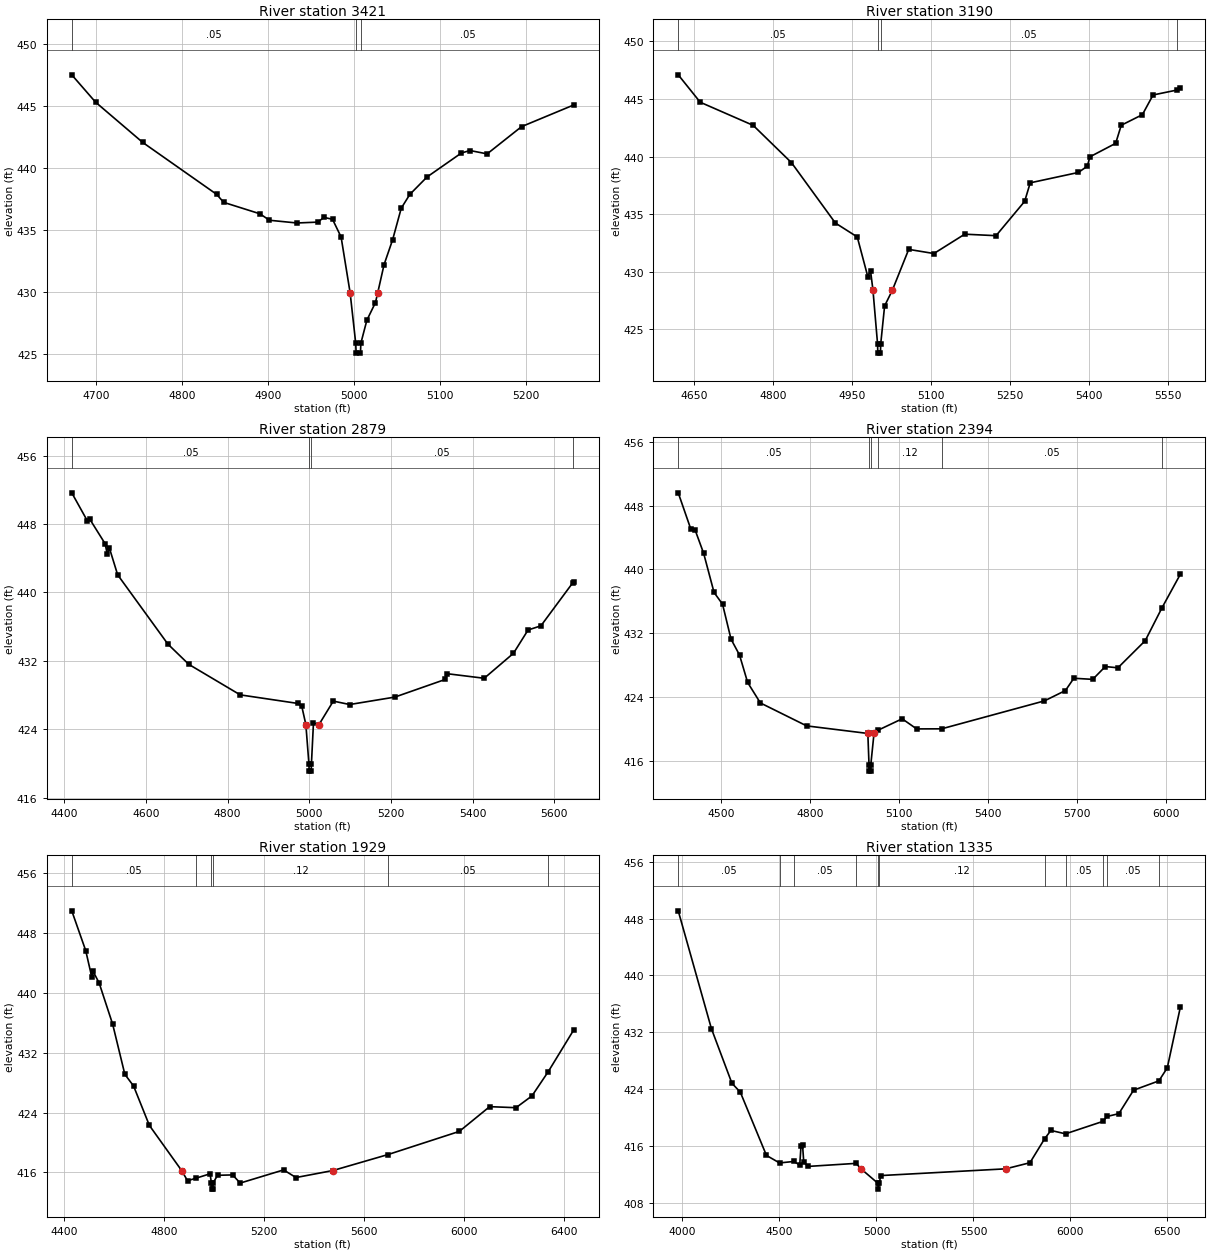
Type RM Length L Ch R = 1,3421,231,231,231
BEGIN DESCRIPTION:
UNT 096 in Running Cr Watershed 2.0
END DESCRIPTION:
XS GIS Cut Line= 3
      2902607.28      7041769.04      2902509.08      7042035.93
      2902509.08      7042335.94
#Sta/Elev= 30
  4671.4  447.50  4699.1  445.30  4754.0  442.06  4840.1  437.88  4848.2  437.24
  4890.4  436.32  4901.5  435.80  4933.5  435.58  4957.8  435.65  4964.9  436.03
  4974.9  435.88  4984.9  434.45  4995.4  429.96  5001.9  425.91  5002.4  425.11
  5007.4  425.11  5007.9  425.91  5014.9  427.76  5024.9  429.18  5027.5  429.96
  5034.9  432.23  5044.9  434.24  5054.9  436.77  5064.9  437.88  5084.9  439.28
  5124.9  441.21  5134.9  441.41  5154.9  441.14  5194.9  443.33  5255.8  445.08
#Mann=3,-1,0
  4671.4    0.05       0  5001.9    0.03       0  5007.9    0.05       0
Bank Sta=4995.4,5027.5
Exp/Cntr=0.3,0.1

Type RM Length L Ch R = 1,3190,311,311,311
BEGIN DESCRIPTION:
Mapping XS dc9be692
END DESCRIPTION:
XS GIS Cut Line= 3
      2902451.05      7041578.03      2902312.16      7042059.80
      2902390.14      7042506.05
#Sta/Elev= 30
  4619.1  447.10  4660.9  444.72  4761.6  442.71  4834.4  439.47  4917.8  434.23
  4959.4  433.02  4979.4  429.58  4984.6  430.10  4989.3  428.38  4998.0  423.73
  4998.5  422.93  5003.5  422.93  5004.0  423.73  5011.4  427.03  5026.0  428.38
  5057.2  431.94  5105.1  431.58  5163.7  433.26  5223.2  433.13  5277.6  436.11
  5288.2  437.72  5379.6  438.62  5396.6  439.16  5401.7  439.98  5450.6  441.15
  5461.2  442.72  5501.4  443.64  5521.7  445.35  5567.3  445.78  5573.5  445.92
#Mann=4,-1,0
  4619.1    0.05       0  4998.0    0.03       0  5004.0    0.05       0
  5567.3    0.08       0
Bank Sta=4989.3,5026
Exp/Cntr=0.3,0.1

Type RM Length L Ch R = 1,2879,485,485,485
BEGIN DESCRIPTION:
Mapping XS 5bc56044
END DESCRIPTION:
XS GIS Cut Line= 3
      2902168.92      7041365.39      2902021.36      7042029.42
      2902299.12      7042502.48
#Sta/Elev= 30
  4418.8  451.64  4457.1  448.35  4462.2  448.61  4500.4  445.69  4505.7  444.47
  4510.9  445.18  4531.1  442.05  4654.0  433.95  4705.2  431.58  4831.0  428.01
  4971.8  427.01  4981.8  426.66  4991.7  424.54  4999.3  419.89  4999.8  419.09
  5004.8  419.09  5005.3  419.89  5010.3  424.70  5023.9  424.54  5058.9  427.28
  5099.0  426.88  5209.5  427.75  5332.5  429.81  5338.3  430.48  5428.2  429.95
  5499.8  432.87  5535.6  435.60  5566.9  436.08  5645.3  441.14  5647.6  441.24
#Mann=4,-1,0
  4418.8    0.05       0  4999.3    0.03       0  5005.3    0.05       0
  5645.3    0.16       0
Bank Sta=4991.7,5023.9
Exp/Cntr=0.3,0.1

Type RM Length L Ch R = 1,2394,465,465,465
BEGIN DESCRIPTION:
Mapping XS e76bea18
END DESCRIPTION:
XS GIS Cut Line= 4
      2902047.42      7041287.20      2901669.80      7041734.28
      2901600.35      7041942.61      2902238.37      7042558.93
#Sta/Elev= 30
  4356.1  449.61  4398.8  445.02  4413.1  444.93  4441.7  442.02  4476.8  437.10
  4505.4  435.63  4534.0  431.24  4562.6  429.25  4590.0  425.80  4632.9  423.23
  4788.9  420.35  4995.0  419.40  4999.0  415.47  4999.5  414.67  5004.5  414.67
  5005.0  415.47  5015.8  419.40  5029.6  419.81  5110.7  421.24  5159.5  419.97
  5243.6  419.98  5590.2  423.49  5660.9  424.79  5689.2  426.33  5752.8  426.19
  5795.2  427.80  5837.7  427.64  5929.8  431.05  5985.6  435.13  6048.0  439.38
#Mann=6,-1,0
  4356.1    0.05       0  4999.0    0.03       0  5005.0    0.05       0
  5029.6    0.12       0  5243.6    0.05       0  5985.6    0.16       0
Bank Sta=4995,5015.8
Exp/Cntr=0.3,0.1

Type RM Length L Ch R = 1,1929,594,594,594
BEGIN DESCRIPTION:
Mapping XS d96352b1
END DESCRIPTION:
XS GIS Cut Line= 4
      2901439.75      7041065.91      2901257.47      7041525.94
      2901222.75      7041855.80      2902147.19      7042597.96
#Sta/Elev= 30
  4429.2  450.98  4485.1  445.66  4509.4  442.12  4514.8  442.88  4539.1  441.31
  4593.2  435.80  4641.8  429.12  4676.9  427.55  4740.2  422.28  4869.4  416.25
  4893.1  414.88  4925.8  415.21  4983.4  415.81  4988.9  414.56  4989.4  413.76
  4994.4  413.76  4994.9  414.56  5013.6  415.61  5073.9  415.66  5104.1  414.57
  5278.1  416.33  5327.7  415.31  5476.1  416.25  5697.1  418.39  5982.2  421.48
  6103.8  424.79  6209.4  424.65  6273.4  426.23  6338.6  429.47  6441.2  435.08
#Mann=6,-1,0
  4429.2    0.05       0  4925.8    0.12       0  4988.9    0.07       0
  4994.9    0.12       0  5697.1    0.05       0  6338.6    0.16       0
Bank Sta=4869.4,5476.1
Exp/Cntr=0.3,0.1

Type RM Length L Ch R = 1,1335,0,0,0
BEGIN DESCRIPTION:
UNT 096 in Running Cr Watershed 1.0
END DESCRIPTION:
XS GIS Cut Line= 4
      2901318.26      7041078.87      2900754.00      7041795.04
      2900801.74      7042085.84      2902064.76      7042645.73
#Sta/Elev= 30
  3978.2  449.10  4149.1  432.51  4254.9  424.81  4298.2  423.55  4432.9  414.64
  4500.5  413.58  4574.3  413.79  4604.5  413.28  4610.9  415.90  4619.0  416.08
  4625.3  413.68  4647.8  413.09  4895.3  413.52  4920.3  412.75  5008.5  410.69
  5009.0  409.89  5014.5  410.69  5021.7  411.80  5666.4  412.75  5791.2  413.61
  5867.1  417.00  5899.2  418.16  5974.4  417.68  6166.8  419.43  6188.9  420.13
  6249.2  420.52  6325.2  423.83  6455.6  425.14  6499.0  426.97  6566.2  435.51
#Mann=11,-1,0
  3978.2    0.05       0  4500.5    0.16       0  4574.3    0.05       0
  4895.3    0.12       0  5008.5    0.07       0  5014.5    0.12       0
  5867.1    0.16       0  5974.4    0.05       0  6166.8    0.16       0
  6188.9    0.05       0  6455.6    0.16       0
Bank Sta=4920.3,5666.4
Exp/Cntr=0.3,0.1

Chan Stop Cuts=-1