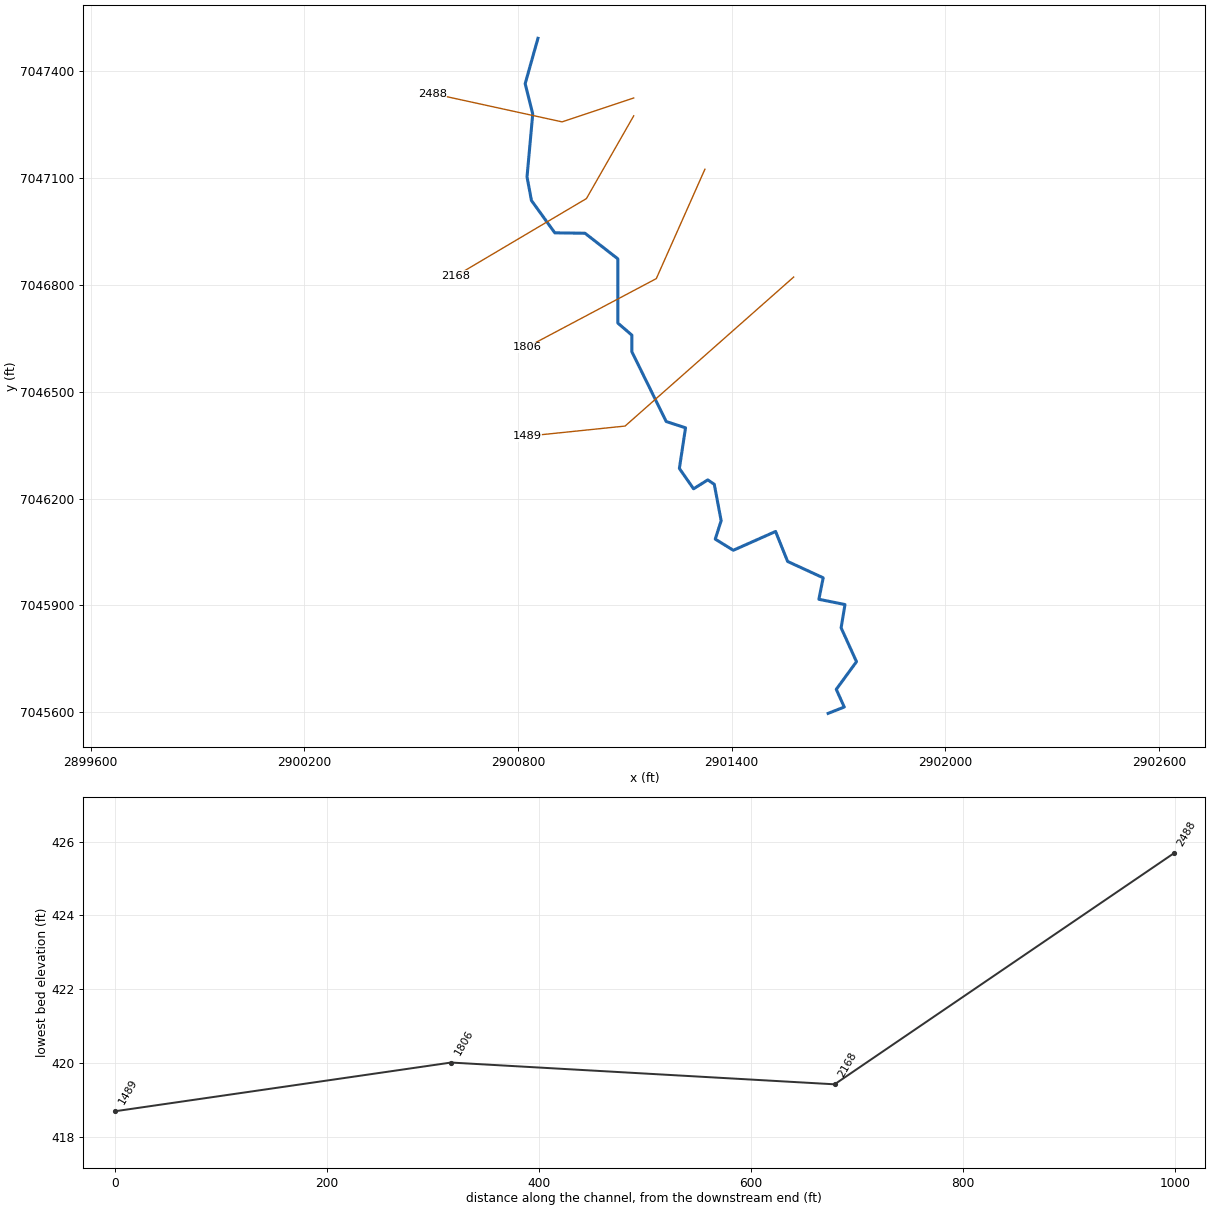
--- UNT 097 in Running Cr Watershed.prj (project) ---

Proj Title=UNT 097 in Running Cr Watershed Base Level Engineering
Current Plan=p01
Default Exp/Contr=0.3,0.1
English Units
Geom File=g01
Flow File=f01
Plan File=p01
BEGIN DESCRIPTION:
UNT 097 in Running Cr Watershed
END DESCRIPTION:

--- UNT 097 in Running Cr Watershed.p01 (plan) ---

Plan Title=Multiple Run
Short Identifier=Multiple
Geom File=g01
Flow File=f01
Subcritical Flow
K Sum by GR= 0
Std Step Tol= 0.01
Critical Tol= 0.01
Num of Std Step Trials= 20
Max Error Tol= 0.3
Flow Tol Ratio= 0.001
Split Flow NTrial= 30
Split Flow Tol= 0.02
Split Flow Ratio= 0.02
Log Output Level= 0
Friction Slope Method= 1
Unsteady Friction Slope Method= 2
Unsteady Bridges Friction Slope Method= 1
Parabolic Critical Depth
Global Vel Dist=  1 , 1 , 1
Global Log Level= 0
CheckData=True
Encroach Param= -1, 0, 0, 0
BEGIN DESCRIPTION:
Multiple Run
END DESCRIPTION:

--- UNT 097 in Running Cr Watershed.f01 (steady flow) ---

Flow Title=Multiple
Number of Profiles=7
Profile Names=10-year,25-year,50-year,1pct_min,100-year,1pct_plu,500-year
River Rch & RM= UNT 097 in Runni,Reach-1,2488
     337     435     512     300     599    1196     821
Boundary for River Rch & Prof#=UNT 097 in Runni,Reach-1,1
Up Type=0
Dn Type=3
Dn Slope=0.005
Boundary for River Rch & Prof#=UNT 097 in Runni,Reach-1,2
Up Type=0
Dn Type=3
Dn Slope=0.005
Boundary for River Rch & Prof#=UNT 097 in Runni,Reach-1,3
Up Type=0
Dn Type=3
Dn Slope=0.005
Boundary for River Rch & Prof#=UNT 097 in Runni,Reach-1,4
Up Type=0
Dn Type=3
Dn Slope=0.005
Boundary for River Rch & Prof#=UNT 097 in Runni,Reach-1,5
Up Type=0
Dn Type=3
Dn Slope=0.005
Boundary for River Rch & Prof#=UNT 097 in Runni,Reach-1,6
Up Type=0
Dn Type=3
Dn Slope=0.005
Boundary for River Rch & Prof#=UNT 097 in Runni,Reach-1,7
Up Type=0
Dn Type=3
Dn Slope=0.005

--- UNT 097 in Running Cr Watershed.g01 (geometry) ---

Geom Title=Existing Conditions

River Reach=UNT 097 in Runni,Reach-1
Reach XY= 30
      2900855.96      7047492.57      2900820.10      7047365.18
      2900841.33      7047280.06      2900825.33      7047103.30
      2900837.75      7047036.96      2900903.39      7046946.22
      2900988.19      7046945.08      2901080.31      7046873.23
      2901080.35      7046692.83      2901119.75      7046658.86
      2901119.66      7046612.45      2901216.33      7046416.12
      2901270.56      7046398.55      2901253.23      7046284.40
      2901293.08      7046227.25      2901332.98      7046252.26
      2901351.29      7046239.85      2901370.61      7046137.50
      2901353.96      7046085.91      2901404.71      7046054.58
      2901523.45      7046107.35      2901557.28      7046023.17
      2901657.23      7045977.21      2901645.12      7045916.90
      2901718.41      7045902.15      2901707.58      7045836.76
      2901750.77      7045741.60      2901693.97      7045663.90
      2901716.35      7045614.22      2901671.05      7045596.43

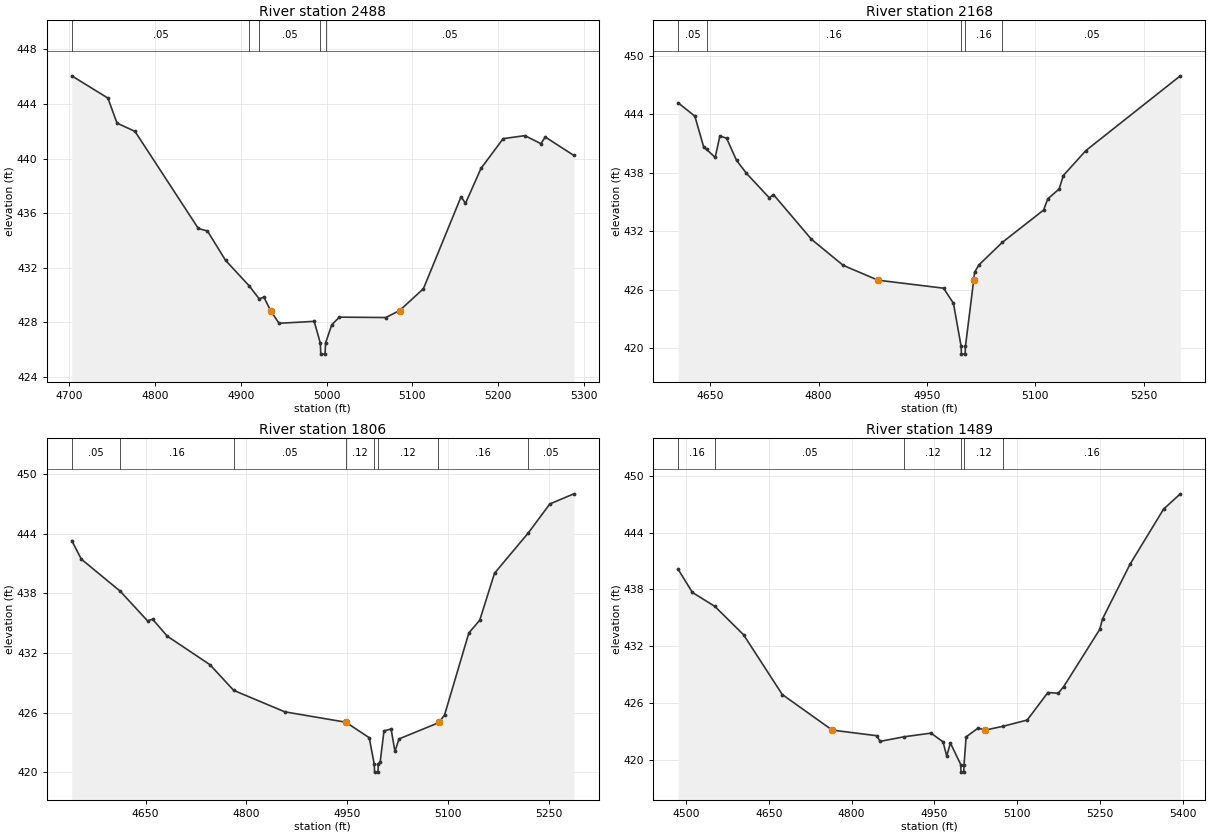
Type RM Length L Ch R = 1,2488,320,320,320
BEGIN DESCRIPTION:
UNT 097 in Running Cr Watershed 4.0
END DESCRIPTION:
XS GIS Cut Line= 3
      2901124.96      7047324.99      2900923.80      7047257.93
      2900559.33      7047337.52
#Sta/Elev= 30
  4703.1  446.06  4745.2  444.43  4755.8  442.60  4776.8  441.99  4850.6  434.88
  4861.2  434.70  4882.3  432.55  4910.0  430.67  4921.5  429.73  4927.0  429.86
  4934.8  428.87  4944.6  427.94  4985.6  428.08  4992.8  426.48  4993.3  425.68
  4998.3  425.68  4998.8  426.48  5006.0  427.82  5014.9  428.39  5069.0  428.36
  5085.1  428.87  5112.9  430.47  5156.8  437.21  5161.9  436.72  5180.0  439.28
  5205.8  441.46  5231.2  441.68  5249.8  441.09  5254.9  441.58  5288.2  440.23
#Mann=5,-1,0
  4703.1    0.05       0  4910.0    0.16       0  4921.5    0.05       0
  4992.8    0.03       0  4998.8    0.05       0
Bank Sta=4934.8,5085.1
Exp/Cntr=0.3,0.1

Type RM Length L Ch R = 1,2168,362,362,362
BEGIN DESCRIPTION:
UNT 097 in Running Cr Watershed 3.0
END DESCRIPTION:
XS GIS Cut Line= 3
      2901125.00      7047275.00      2900992.08      7047042.39
      2900625.02      7046825.01
#Sta/Elev= 30
  4605.9  445.18  4628.9  443.81  4641.2  440.63  4645.2  440.40  4657.0  439.58
  4663.5  441.79  4672.8  441.55  4686.5  439.29  4700.2  437.96  4731.9  435.44
  4737.6  435.78  4790.2  431.19  4834.1  428.52  4882.3  427.00  4972.9  426.18
  4986.6  424.63  4997.2  420.22  4997.7  419.42  5002.7  419.42  5003.2  420.22
  5014.6  427.00  5015.8  427.81  5021.6  428.55  5054.2  430.88  5111.3  434.19
  5117.1  435.34  5132.8  436.35  5138.6  437.73  5169.8  440.29  5300.4  447.95
#Mann=5,-1,0
  4605.9    0.05       0  4645.2    0.16       0  4997.2    0.07       0
  5003.2    0.16       0  5054.2    0.05       0
Bank Sta=4882.3,5014.6
Exp/Cntr=0.3,0.1

Type RM Length L Ch R = 1,1806,317,317,317
BEGIN DESCRIPTION:
UNT 097 in Running Cr Watershed 2.0
END DESCRIPTION:
XS GIS Cut Line= 3
      2901324.99      7047124.98      2901188.39      7046817.63
      2900825.03      7046625.01
#Sta/Elev= 30
  4540.1  443.28  4554.4  441.42  4612.4  438.19  4652.9  435.22  4660.5  435.38
  4682.3  433.68  4745.9  430.81  4781.2  428.23  4857.4  426.07  4948.1  425.03
  4948.6  425.01  4983.0  423.47  4990.5  420.81  4991.0  420.01  4996.0  420.01
  4996.5  420.81  4999.3  421.01  5005.0  424.16  5015.6  424.34  5021.3  422.10
  5027.4  423.35  5085.3  424.95  5087.1  425.01  5095.3  425.78  5131.3  433.99
  5147.6  435.29  5169.6  440.01  5219.9  444.06  5251.9  446.97  5287.7  447.99
#Mann=8,-1,0
  4540.1    0.05       0  4612.4    0.16       0  4781.2    0.05       0
  4948.1    0.12       0  4990.5    0.07       0  4996.5    0.12       0
  5085.3    0.16       0  5219.9    0.05       0
Bank Sta=4948.6,5087.1
Exp/Cntr=0.3,0.1

Type RM Length L Ch R = 1,1489,0,0,0
BEGIN DESCRIPTION:
UNT 097 in Running Cr Watershed 1.0
END DESCRIPTION:
XS GIS Cut Line= 3
      2901574.27      7046822.01      2901100.77      7046403.49
      2900824.99      7046375.00
#Sta/Elev= 30
  4486.2  440.10  4511.9  437.67  4552.5  436.20  4604.4  433.21  4674.6  426.89
  4765.1  423.13  4845.3  422.54  4851.9  421.94  4895.9  422.43  4943.9  422.81
  4965.7  421.89  4972.4  420.40  4979.1  421.76  4997.8  419.49  4998.3  418.69
  5003.3  418.69  5003.8  419.49  5007.5  422.41  5029.3  423.35  5042.1  423.13
  5074.8  423.54  5118.1  424.19  5155.6  427.10  5174.2  427.02  5184.3  427.73
  5249.5  433.77  5254.6  434.89  5304.9  440.71  5365.2  446.48  5395.4  448.09
#Mann=6,-1,0
  4486.2    0.16       0  4552.5    0.05       0  4895.9    0.12       0
  4997.8    0.07       0  5003.8    0.12       0  5074.8    0.16       0
Bank Sta=4765.1,5042.1
Exp/Cntr=0.3,0.1

Chan Stop Cuts=-1