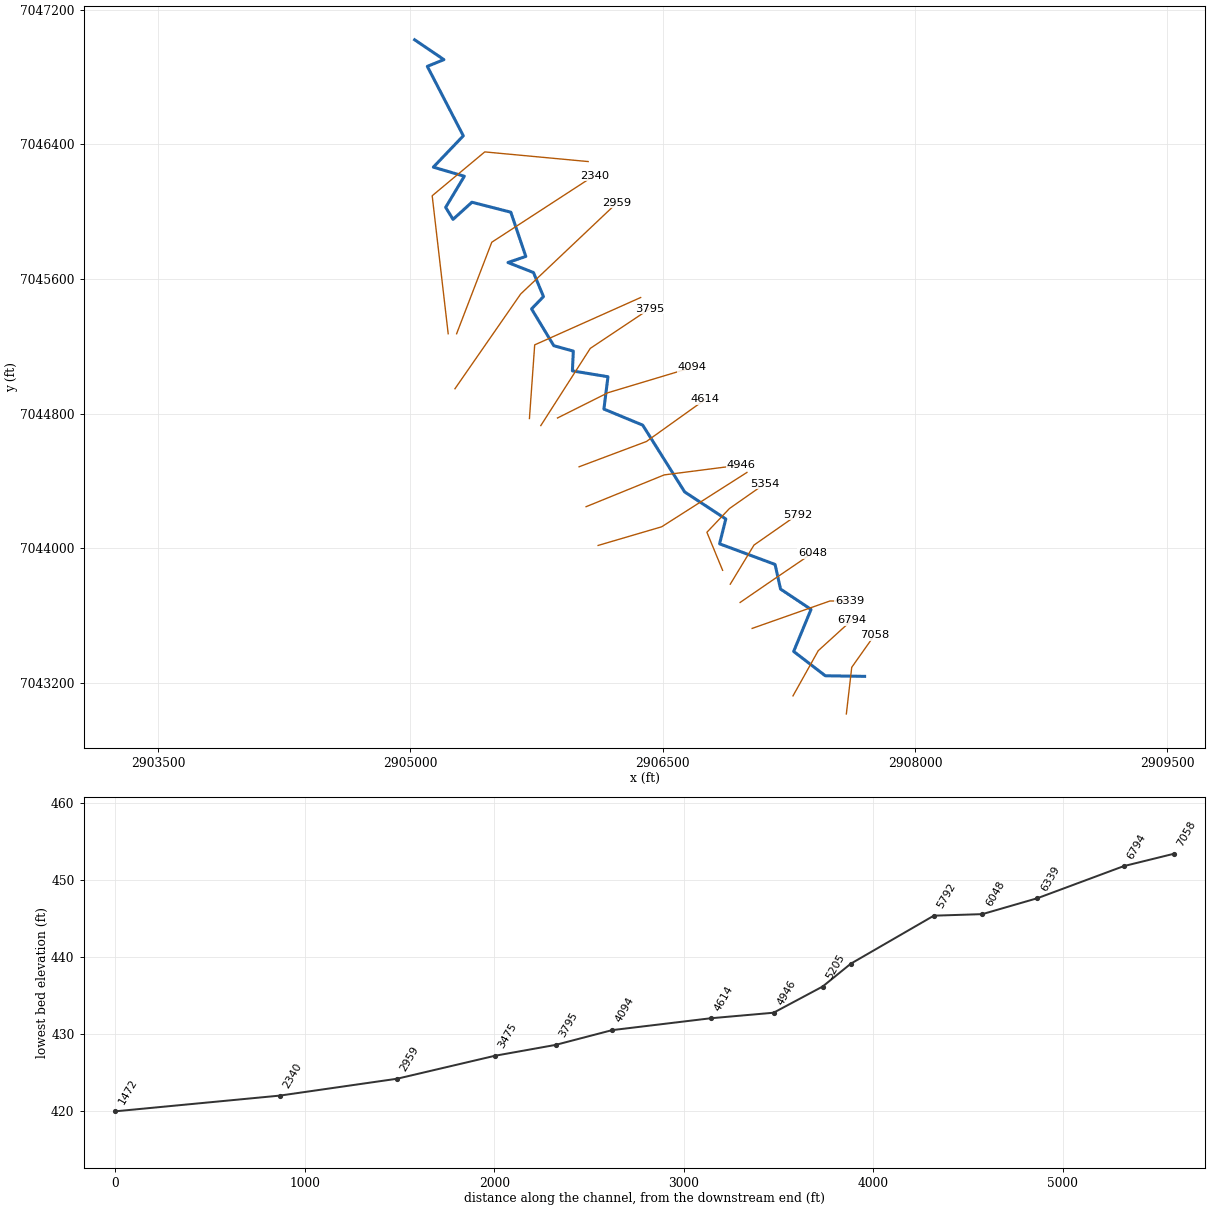
--- UNT 098 in Running Cr Watershed.prj (project) ---

Proj Title=UNT 098 in Running Cr Watershed Base Level Engineering
Current Plan=p01
Default Exp/Contr=0.3,0.1
English Units
Geom File=g01
Flow File=f01
Plan File=p01
BEGIN DESCRIPTION:
UNT 098 in Running Cr Watershed
END DESCRIPTION:

--- UNT 098 in Running Cr Watershed.p01 (plan) ---

Plan Title=Multiple Run
Short Identifier=Multiple
Geom File=g01
Flow File=f01
Subcritical Flow
K Sum by GR= 0
Std Step Tol= 0.01
Critical Tol= 0.01
Num of Std Step Trials= 20
Max Error Tol= 0.3
Flow Tol Ratio= 0.001
Split Flow NTrial= 30
Split Flow Tol= 0.02
Split Flow Ratio= 0.02
Log Output Level= 0
Friction Slope Method= 1
Unsteady Friction Slope Method= 2
Unsteady Bridges Friction Slope Method= 1
Parabolic Critical Depth
Global Vel Dist=  1 , 1 , 1
Global Log Level= 0
CheckData=True
Encroach Param= -1, 0, 0, 0
BEGIN DESCRIPTION:
Multiple Run
END DESCRIPTION:

--- UNT 098 in Running Cr Watershed.f01 (steady flow) ---

Flow Title=Multiple
Number of Profiles=7
Profile Names=10-year,25-year,50-year,1pct_min,100-year,1pct_plu,500-year
River Rch & RM= UNT 098 in Runni,Reach-1,7058
     208     260     300     173     345     687     454
River Rch & RM= UNT 098 in Runni,Reach-1,4946
     496     662     798     478     954    1904    1368
River Rch & RM= UNT 098 in Runni,Reach-1,4614
     749    1023    1250     760    1516    3024    2231
Boundary for River Rch & Prof#=UNT 098 in Runni,Reach-1,1
Up Type=0
Dn Type=3
Dn Slope=0.005
Boundary for River Rch & Prof#=UNT 098 in Runni,Reach-1,2
Up Type=0
Dn Type=3
Dn Slope=0.005
Boundary for River Rch & Prof#=UNT 098 in Runni,Reach-1,3
Up Type=0
Dn Type=3
Dn Slope=0.005
Boundary for River Rch & Prof#=UNT 098 in Runni,Reach-1,4
Up Type=0
Dn Type=3
Dn Slope=0.005
Boundary for River Rch & Prof#=UNT 098 in Runni,Reach-1,5
Up Type=0
Dn Type=3
Dn Slope=0.005
Boundary for River Rch & Prof#=UNT 098 in Runni,Reach-1,6
Up Type=0
Dn Type=3
Dn Slope=0.005
Boundary for River Rch & Prof#=UNT 098 in Runni,Reach-1,7
Up Type=0
Dn Type=3
Dn Slope=0.005

--- UNT 098 in Running Cr Watershed.g01 (geometry) ---

Geom Title=Existing Conditions

River Reach=UNT 098 in Runni,Reach-1
Reach XY= 30
      2907700.61      7043240.75      2907467.05      7043244.25
      2907278.91      7043388.66      2907382.14      7043638.35
      2907200.86      7043759.16      2907168.33      7043905.29
      2906838.45      7044027.79      2906875.45      7044175.13
      2906630.79      7044335.96      2906381.52      7044732.43
      2906150.74      7044827.82      2906174.89      7045019.90
      2905963.42      7045054.66      2905968.92      7045172.13
      2905852.98      7045204.01      2905720.64      7045422.64
      2905791.45      7045495.78      2905731.98      7045638.71
      2905580.43      7045698.01      2905686.34      7045734.26
      2905597.31      7045996.91      2905366.11      7046056.06
      2905253.78      7045954.38      2905209.95      7046025.65
      2905320.89      7046210.28      2905136.82      7046264.48
      2905314.87      7046450.52      2905100.90      7046862.88
      2905199.60      7046902.85      2905025.59      7047020.71

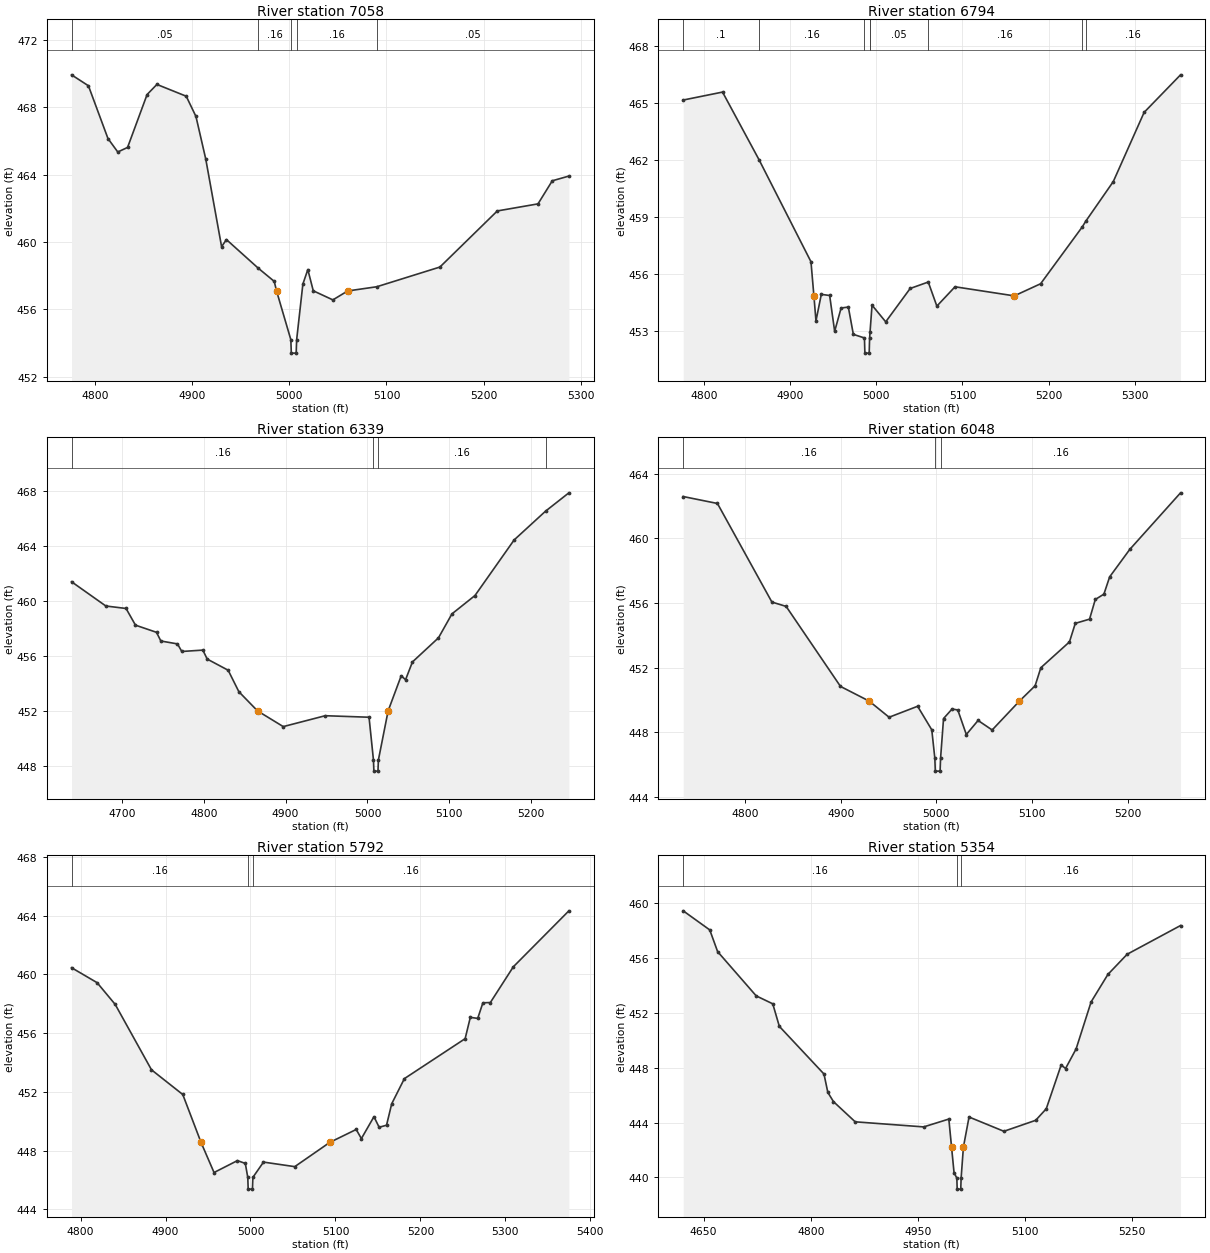
Type RM Length L Ch R = 1,7058,264,264,264
BEGIN DESCRIPTION:
UNT 098 in Running Cr Watershed 11.0
END DESCRIPTION:
XS GIS Cut Line= 3
      2907592.11      7043017.72      2907624.13      7043294.41
      2907759.07      7043485.04
#Sta/Elev= 30
  4775.7  469.93  4793.1  469.28  4813.2  466.15  4823.3  465.35  4833.4  465.62
  4853.5  468.76  4863.6  469.36  4893.8  468.66  4903.8  467.46  4913.9  464.93
  4930.2  459.73  4935.2  460.15  4968.0  458.45  4984.4  457.67  4986.8  457.10
  5001.5  454.21  5002.0  453.41  5007.0  453.41  5007.5  454.21  5013.9  457.51
  5019.0  458.37  5024.6  457.11  5044.8  456.57  5060.0  457.10  5090.0  457.35
  5155.0  458.52  5214.1  461.85  5256.0  462.27  5270.7  463.64  5287.8  463.92
#Mann=5,-1,0
  4775.7    0.05       0  4968.0    0.16       0  5001.5    0.07       0
  5007.5    0.16       0  5090.0    0.05       0
Bank Sta=4986.8,5060
Exp/Cntr=0.3,0.1

Type RM Length L Ch R = 1,6794,455,455,455
BEGIN DESCRIPTION:
UNT 098 in Running Cr Watershed 10.0
END DESCRIPTION:
XS GIS Cut Line= 3
      2907274.99      7043124.98      2907425.00      7043393.13
      2907625.01      7043575.01
#Sta/Elev= 30
  4775.7  465.16  4821.4  465.58  4863.8  462.01  4924.1  456.63  4927.5  454.83
  4929.9  453.51  4936.1  454.91  4945.8  454.85  4951.6  452.96  4959.1  454.19
  4967.5  454.24  4973.3  452.80  4986.2  452.61  4986.7  451.81  4991.7  451.81
  4992.2  452.61  4992.7  452.92  4995.0  454.34  5010.9  453.46  5039.3  455.22
  5060.3  455.56  5070.3  454.29  5091.4  455.31  5160.2  454.83  5190.8  455.47
  5239.2  458.47  5243.1  458.76  5275.2  460.86  5311.0  464.51  5353.3  466.49
#Mann=8,-1,0
  4775.7     0.1       0  4863.8    0.16       0  4986.2    0.03       0
  4992.2    0.16       0  4992.7    0.05       0  5060.3    0.16       0
  5239.2    0.05       0  5243.1    0.16       0
Bank Sta=4927.5,5160.2
Exp/Cntr=0.3,0.1

Type RM Length L Ch R = 1,6339,291,291,291
BEGIN DESCRIPTION:
Mapping XS a8748a15
END DESCRIPTION:
XS GIS Cut Line= 3
      2907032.20      7043525.51      2907494.45      7043688.27
      2907611.88      7043688.27
#Sta/Elev= 30
  4638.5  461.39  4680.4  459.63  4705.1  459.45  4716.6  458.24  4742.3  457.72
  4747.6  457.09  4767.9  456.88  4773.2  456.33  4798.9  456.43  4804.2  455.78
  4829.8  454.97  4842.9  453.41  4865.7  452.02  4897.1  450.88  4948.4  451.67
  5001.9  451.56  5007.3  448.45  5007.8  447.65  5012.8  447.65  5013.3  448.45
  5025.2  452.02  5041.2  454.57  5046.5  454.28  5054.9  455.57  5086.7  457.32
  5103.2  459.06  5131.3  460.39  5179.1  464.42  5217.5  466.51  5246.0  467.84
#Mann=4,-1,0
  4638.5    0.16       0  5007.3    0.07       0  5013.3    0.16       0
  5217.5    0.05       0
Bank Sta=4865.7,5025.2
Exp/Cntr=0.3,0.1

Type RM Length L Ch R = 1,6048,256,256,256
BEGIN DESCRIPTION:
Mapping XS 5cc41c61
END DESCRIPTION:
XS GIS Cut Line= 3
      2906960.63      7043679.62      2907147.23      7043807.63
      2907390.10      7043972.44
#Sta/Elev= 30
  4735.4  462.60  4771.2  462.17  4828.1  456.06  4843.0  455.79  4899.8  450.83
  4929.8  449.92  4950.6  448.92  4980.4  449.60  4995.2  448.14  4998.4  446.38
  4998.9  445.58  5003.9  445.58  5004.4  446.38  5007.5  448.84  5016.4  449.43
  5022.4  449.37  5031.3  447.85  5043.6  448.72  5058.3  448.13  5086.8  449.92
  5103.2  450.87  5109.2  451.99  5139.1  453.59  5145.2  454.74  5160.1  455.00
  5166.1  456.22  5175.1  456.55  5181.1  457.62  5202.1  459.32  5255.2  462.83
#Mann=3,-1,0
  4735.4    0.16       0  4998.4    0.07       0  5004.4    0.16       0
Bank Sta=4929.8,5086.8
Exp/Cntr=0.3,0.1

Type RM Length L Ch R = 1,5792,438,438,438
BEGIN DESCRIPTION:
UNT 098 in Running Cr Watershed 9.0
END DESCRIPTION:
XS GIS Cut Line= 3
      2906902.03      7043788.14      2907043.06      7044020.30
      2907300.32      7044199.74
#Sta/Elev= 30
  4789.4  460.45  4819.5  459.43  4840.8  457.95  4883.5  453.50  4920.3  451.82
  4941.8  448.56  4957.1  446.51  4984.6  447.32  4993.9  447.13  4996.8  446.18
  4997.3  445.38  5002.3  445.38  5002.8  446.18  5015.3  447.22  5052.1  446.91
  5093.3  448.56  5124.4  449.44  5130.5  448.82  5145.3  450.31  5151.4  449.59
  5160.1  449.73  5166.2  451.19  5181.1  452.90  5252.6  455.62  5258.7  457.07
  5267.4  457.00  5273.5  458.06  5282.3  458.08  5309.3  460.51  5374.7  464.32
#Mann=3,-1,0
  4789.4    0.16       0  4996.8    0.07       0  5002.8    0.16       0
Bank Sta=4941.8,5093.3
Exp/Cntr=0.3,0.1

Type RM Length L Ch R = 1,5354,149,149,149
BEGIN DESCRIPTION:
UNT 098 in Running Cr Watershed 8.0
END DESCRIPTION:
XS GIS Cut Line= 4
      2906856.42      7043870.58      2906763.11      7044096.26
      2906896.90      7044237.11      2907108.18      7044384.89
#Sta/Elev= 30
  4621.4  459.41  4658.6  458.02  4669.6  456.44  4723.6  453.22  4746.8  452.64
  4756.0  451.00  4818.5  447.53  4823.9  446.19  4831.8  445.52  4862.2  444.05
  4958.1  443.68  4993.3  444.25  4997.1  442.21  5000.6  440.35  5004.5  439.95
  5005.0  439.15  5010.0  439.15  5010.5  439.95  5013.7  442.21  5021.6  444.40
  5070.4  443.36  5114.9  444.16  5129.7  445.00  5150.6  448.19  5156.7  447.93
  5171.5  449.36  5192.5  452.78  5216.0  454.78  5243.0  456.25  5317.7  458.34
#Mann=3,-1,0
  4621.4    0.16       0  5004.5    0.07       0  5010.5    0.16       0
Bank Sta=4997.1,5013.7
Exp/Cntr=0.3,0.1

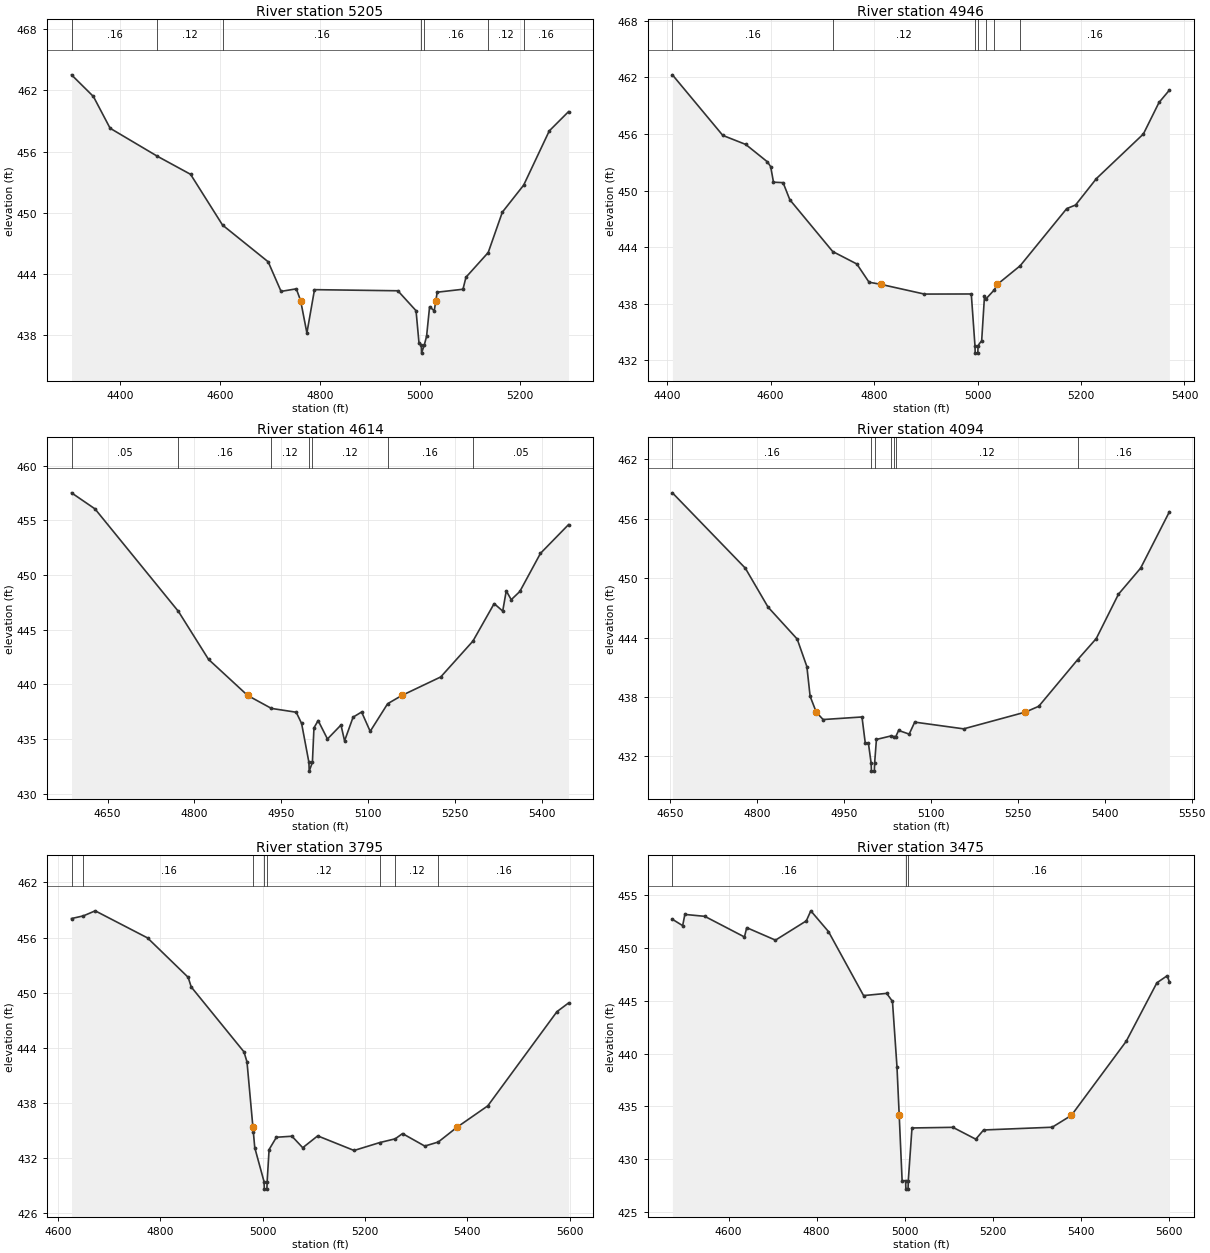
Type RM Length L Ch R = 1,5205,259,259,259
BEGIN DESCRIPTION:
UNT 098 in Running Cr Watershed 7.0
END DESCRIPTION:
XS GIS Cut Line= 3
      2906116.38      7044018.12      2906494.02      7044128.81
      2907000.95      7044451.60
#Sta/Elev= 30
  4302.8  463.54  4346.6  461.41  4380.0  458.29  4474.8  455.53  4541.0  453.76
  4605.0  448.77  4696.3  445.16  4722.1  442.25  4752.6  442.50  4761.3  441.33
  4773.8  438.16  4789.0  442.42  4955.8  442.31  4992.2  440.35  4998.1  437.18
  5002.7  436.98  5003.2  436.18  5008.7  436.98  5013.3  437.84  5019.3  440.74
  5028.6  440.34  5031.8  441.33  5034.5  442.17  5086.1  442.46  5092.1  443.64
  5136.6  446.07  5164.9  450.04  5207.6  452.70  5258.8  458.03  5297.3  459.92
#Mann=7,-1,0
  4302.8    0.16       0  4474.8    0.12       0  4605.0    0.16       0
  5002.7    0.07       0  5008.7    0.16       0  5136.6    0.12       0
  5207.6    0.16       0
Bank Sta=4761.3,5031.8
Exp/Cntr=0.3,0.1

Type RM Length L Ch R = 1,4946,332,332,332
BEGIN DESCRIPTION:
UNT 098 in Running Cr Watershed 6.0
END DESCRIPTION:
XS GIS Cut Line= 3
      2906044.76      7044248.15      2906509.21      7044436.97
      2906964.89      7044495.56
#Sta/Elev= 30
  4410.1  462.28  4507.5  455.86  4551.9  454.90  4593.9  453.05  4600.1  452.54
  4605.5  450.90  4624.1  450.85  4637.1  449.04  4720.0  443.55  4766.6  442.23
  4790.2  440.30  4813.1  440.07  4897.2  439.04  4987.9  439.05  4995.0  433.58
  4995.5  432.78  5000.5  432.78  5001.0  433.58  5008.0  434.11  5013.4  438.80
  5016.3  438.53  5032.3  439.48  5038.3  440.07  5082.4  442.04  5172.4  448.10
  5189.5  448.48  5229.9  451.29  5320.6  456.01  5350.8  459.35  5370.9  460.66
#Mann=7,-1,0
  4410.1    0.16       0  4720.0    0.12       0  4995.0    0.07       0
  5001.0    0.12       0  5016.3    0.16       0  5032.3    0.12       0
  5082.4    0.16       0
Bank Sta=4813.1,5038.3
Exp/Cntr=0.3,0.1

Type RM Length L Ch R = 1,4614,520,520,520
BEGIN DESCRIPTION:
UNT 098 in Running Cr Watershed 5.0
END DESCRIPTION:
XS GIS Cut Line= 3
      2906003.39      7044485.28      2906403.38      7044635.27
      2906753.38      7044885.27
#Sta/Elev= 30
  4587.9  457.53  4628.4  456.06  4772.4  446.67  4824.2  442.29  4891.6  438.99
  4932.7  437.80  4975.5  437.45  4984.8  436.42  4997.4  432.86  4997.9  432.06
  5003.4  432.86  5006.1  436.02  5013.3  436.69  5029.4  435.00  5052.7  436.28
  5058.9  434.83  5073.6  437.00  5088.3  437.47  5103.1  435.70  5133.2  438.23
  5157.9  438.99  5224.8  440.68  5280.3  443.96  5316.9  447.39  5331.7  446.71
  5337.8  448.56  5346.4  447.75  5361.2  448.50  5396.8  451.99  5445.2  454.62
#Mann=7,-1,0
  4587.9    0.05       0  4772.4    0.16       0  4932.7    0.12       0
  4997.4    0.07       0  5003.4    0.12       0  5133.2    0.16       0
  5280.3    0.05       0
Bank Sta=4891.6,5157.9
Exp/Cntr=0.3,0.1

Type RM Length L Ch R = 1,4094,299,299,299
BEGIN DESCRIPTION:
UNT 098 in Running Cr Watershed 4.0
END DESCRIPTION:
XS GIS Cut Line= 3
      2905874.96      7044774.98      2906175.00      7044925.00
      2906675.03      7045075.01
#Sta/Elev= 30
  4654.1  458.63  4779.9  451.02  4819.1  447.09  4869.4  443.86  4886.1  441.08
  4891.7  438.08  4902.3  436.48  4914.1  435.73  4981.2  435.99  4986.8  433.38
  4992.2  433.38  4997.0  431.32  4997.5  430.52  5002.5  430.52  5003.0  431.32
  5006.1  433.72  5031.7  434.08  5035.8  434.01  5039.2  433.97  5044.4  434.63
  5062.6  434.26  5072.2  435.47  5156.6  434.79  5263.0  436.48  5286.2  437.07
  5353.3  441.78  5385.4  443.91  5423.7  448.39  5462.0  451.03  5511.6  456.72
#Mann=7,-1,0
  4654.1    0.16       0  4997.0    0.07       0  5003.0    0.16       0
  5031.7    0.12       0  5035.8    0.16       0  5039.2    0.12       0
  5353.3    0.16       0
Bank Sta=4902.3,5263
Exp/Cntr=0.3,0.1

Type RM Length L Ch R = 1,3795,320,320,320
BEGIN DESCRIPTION:
UNT 098 in Running Cr Watershed 3.0
END DESCRIPTION:
XS GIS Cut Line= 3
      2905775.70      7044729.93      2906069.35      7045187.90
      2906425.03      7045425.02
#Sta/Elev= 30
  4626.1  458.07  4649.3  458.36  4672.4  458.91  4774.7  455.96  4854.1  451.67
  4860.1  450.62  4963.2  443.55  4969.1  442.46  4980.7  435.34  4981.6  434.78
  4984.3  433.11  5002.5  429.40  5003.0  428.60  5008.0  428.60  5008.5  429.40
  5012.3  432.91  5026.6  434.25  5057.0  434.36  5078.1  433.11  5107.3  434.40
  5178.4  432.81  5228.6  433.67  5258.9  434.08  5273.1  434.65  5316.6  433.29
  5343.0  433.73  5379.6  435.34  5439.8  437.67  5575.0  447.93  5597.6  448.87
#Mann=8,-1,0
  4626.1    0.05       0  4649.3    0.16       0  4981.6    0.12       0
  5002.5    0.07       0  5008.5    0.12       0  5228.6    0.16       0
  5258.9    0.12       0  5343.0    0.16       0
Bank Sta=4980.7,5379.6
Exp/Cntr=0.3,0.1

Type RM Length L Ch R = 1,3475,516,516,516
BEGIN DESCRIPTION:
Mapping XS b5cceff0
END DESCRIPTION:
XS GIS Cut Line= 3
      2905707.99      7044771.64      2905739.24      7045209.10
      2906369.08      7045490.19
#Sta/Elev= 30
  4472.5  452.69  4495.8  452.09  4500.8  453.15  4546.0  452.97  4636.1  451.02
  4641.2  451.90  4706.5  450.72  4776.5  452.54  4786.7  453.49  4826.8  451.53
  4906.5  445.48  4959.0  445.69  4972.1  444.93  4982.3  438.76  4987.4  434.16
  4994.0  427.99  5002.0  427.99  5002.5  427.19  5007.5  427.19  5008.0  427.99
  5016.4  432.97  5109.3  433.03  5161.2  431.91  5179.0  432.78  5334.7  433.04
  5378.3  434.16  5502.7  441.16  5572.4  446.69  5595.6  447.35  5600.8  446.77
#Mann=3,-1,0
  4472.5    0.16       0  5002.0    0.07       0  5008.0    0.16       0
Bank Sta=4987.4,5378.3
Exp/Cntr=0.3,0.1

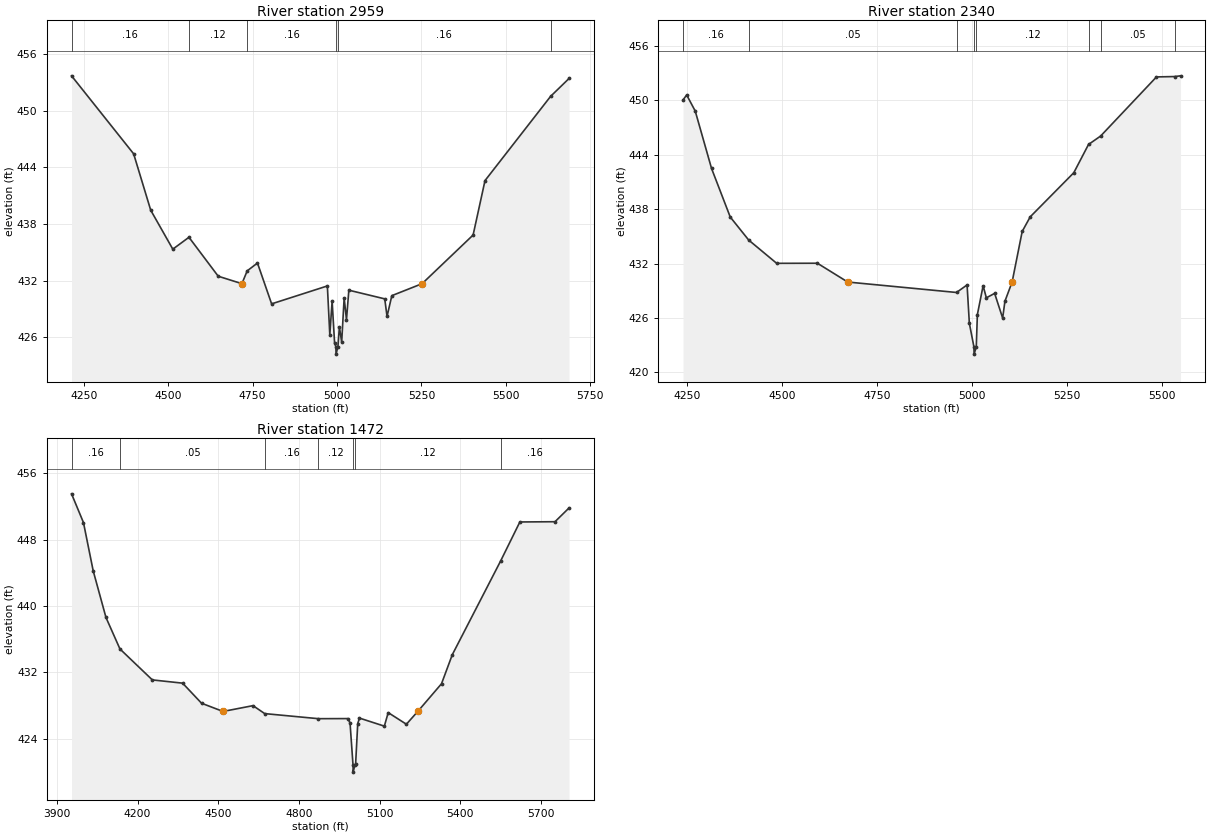
Type RM Length L Ch R = 1,2959,619,619,619
BEGIN DESCRIPTION:
Mapping XS 8410b0ae
END DESCRIPTION:
XS GIS Cut Line= 3
      2905265.29      7044948.70      2905655.91      7045511.19
      2906228.86      7046052.89
#Sta/Elev= 30
  4214.0  453.72  4397.9  445.45  4448.5  439.47  4513.9  435.34  4561.7  436.60
  4648.4  432.47  4718.5  431.68  4734.2  433.04  4764.6  433.87  4806.5  429.54
  4971.6  431.44  4978.8  426.27  4985.7  429.82  4993.0  425.37  4996.8  425.01
  4997.3  424.21  5002.9  425.01  5007.2  427.09  5014.0  425.49  5021.3  430.17
  5028.2  427.86  5035.2  430.99  5141.5  430.07  5148.3  428.21  5162.5  430.41
  5252.1  431.68  5403.2  436.84  5438.4  442.61  5632.6  451.54  5687.3  453.44
#Mann=6,-1,0
  4214.0    0.16       0  4561.7    0.12       0  4734.2    0.16       0
  4996.8    0.07       0  5002.9    0.16       0  5632.6    0.05       0
Bank Sta=4718.5,5252.1
Exp/Cntr=0.3,0.1

Type RM Length L Ch R = 1,2340,868,868,868
BEGIN DESCRIPTION:
UNT 098 in Running Cr Watershed 2.0
END DESCRIPTION:
XS GIS Cut Line= 3
      2905275.01      7045275.03      2905484.03      7045818.48
      2906093.40      7046214.31
#Sta/Elev= 30
  4240.1  450.02  4249.7  450.56  4272.2  448.79  4315.1  442.47  4364.3  437.12
  4412.9  434.58  4486.5  432.02  4593.6  432.03  4673.4  429.96  4959.6  428.81
  4987.4  429.64  4993.4  425.41  5005.4  422.82  5005.9  422.02  5011.6  422.82
  5014.5  426.38  5029.6  429.55  5038.1  428.22  5059.9  428.71  5081.0  425.99
  5087.0  427.85  5105.9  429.96  5132.4  435.53  5153.5  437.14  5268.2  442.00
  5306.9  445.11  5338.8  446.04  5485.7  452.55  5533.3  452.59  5549.0  452.67
#Mann=8,-1,0
  4240.1    0.16       0  4412.9    0.05       0  4959.6    0.12       0
  5005.4    0.07       0  5011.6    0.12       0  5306.9    0.16       0
  5338.8    0.05       0  5533.3    0.16       0
Bank Sta=4673.4,5105.9
Exp/Cntr=0.3,0.1

Type RM Length L Ch R = 1,1472,0,0,0
BEGIN DESCRIPTION:
UNT 098 in Running Cr Watershed 1.0
END DESCRIPTION:
XS GIS Cut Line= 4
      2905225.00      7045274.99      2905129.87      7046094.52
      2905442.37      7046354.94      2906056.98      7046297.64
#Sta/Elev= 30
  3954.8  453.51  3999.1  450.05  4035.3  444.23  4082.8  438.61  4134.7  434.82
  4255.1  431.09  4367.6  430.70  4438.0  428.28  4517.9  427.29  4629.3  427.99
  4672.8  427.03  4872.2  426.42  4982.1  426.43  4989.9  425.90  5001.1  420.78
  5001.6  419.98  5007.3  420.78  5010.7  421.00  5018.5  425.83  5025.0  426.49
  5117.4  425.52  5131.8  427.15  5199.3  425.75  5241.6  427.29  5329.9  430.63
  5370.0  434.13  5549.3  445.40  5621.1  450.12  5751.7  450.15  5803.9  451.81
#Mann=7,-1,0
  3954.8    0.16       0  4134.7    0.05       0  4672.8    0.16       0
  4872.2    0.12       0  5001.1    0.07       0  5007.3    0.12       0
  5549.3    0.16       0
Bank Sta=4517.9,5241.6
Exp/Cntr=0.3,0.1

Chan Stop Cuts=-1