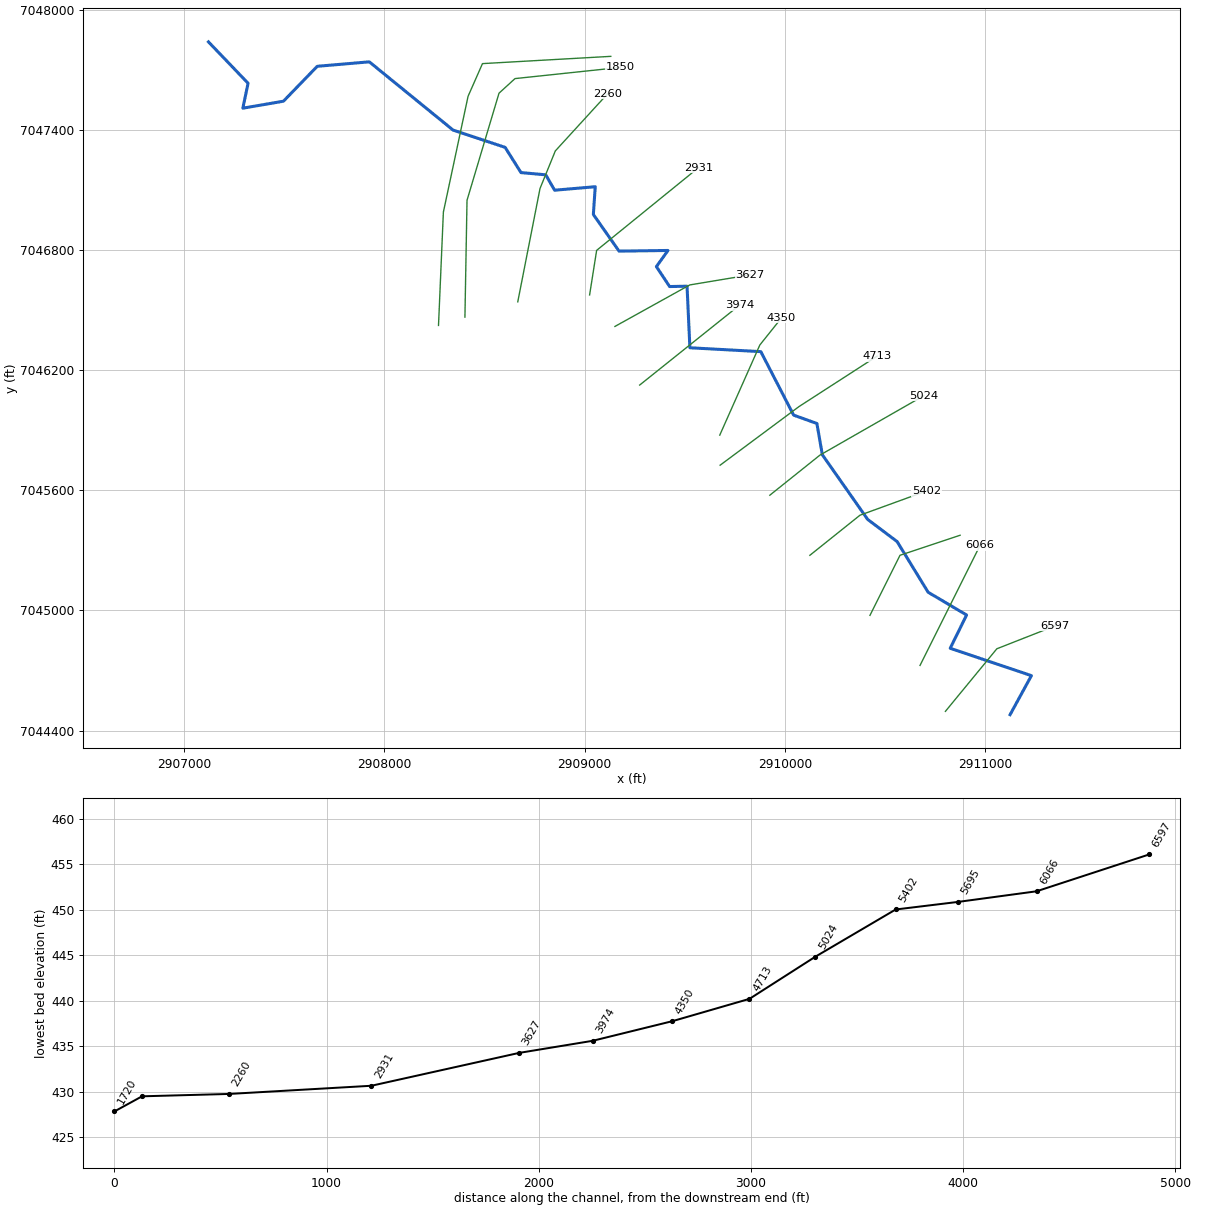
--- UNT 099 in Running Cr Watershed.prj (project) ---

Proj Title=UNT 099 in Running Cr Watershed Base Level Engineering
Current Plan=p01
Default Exp/Contr=0.3,0.1
English Units
Geom File=g01
Flow File=f01
Plan File=p01
BEGIN DESCRIPTION:
UNT 099 in Running Cr Watershed
END DESCRIPTION:

--- UNT 099 in Running Cr Watershed.p01 (plan) ---

Plan Title=Multiple Run
Short Identifier=Multiple
Geom File=g01
Flow File=f01
Subcritical Flow
K Sum by GR= 0
Std Step Tol= 0.01
Critical Tol= 0.01
Num of Std Step Trials= 20
Max Error Tol= 0.3
Flow Tol Ratio= 0.001
Split Flow NTrial= 30
Split Flow Tol= 0.02
Split Flow Ratio= 0.02
Log Output Level= 0
Friction Slope Method= 1
Unsteady Friction Slope Method= 2
Unsteady Bridges Friction Slope Method= 1
Parabolic Critical Depth
Global Vel Dist=  1 , 1 , 1
Global Log Level= 0
CheckData=True
Encroach Param= -1, 0, 0, 0
BEGIN DESCRIPTION:
Multiple Run
END DESCRIPTION:

--- UNT 099 in Running Cr Watershed.f01 (steady flow) ---

Flow Title=Multiple
Number of Profiles=7
Profile Names=10-year,25-year,50-year,1pct_min,100-year,1pct_plu,500-year
River Rch & RM= UNT 099 in Runni,Reach-1,6597
     507     675     810     484     966    1928    1374
Boundary for River Rch & Prof#=UNT 099 in Runni,Reach-1,1
Up Type=0
Dn Type=3
Dn Slope=0.005
Boundary for River Rch & Prof#=UNT 099 in Runni,Reach-1,2
Up Type=0
Dn Type=3
Dn Slope=0.005
Boundary for River Rch & Prof#=UNT 099 in Runni,Reach-1,3
Up Type=0
Dn Type=3
Dn Slope=0.005
Boundary for River Rch & Prof#=UNT 099 in Runni,Reach-1,4
Up Type=0
Dn Type=3
Dn Slope=0.005
Boundary for River Rch & Prof#=UNT 099 in Runni,Reach-1,5
Up Type=0
Dn Type=3
Dn Slope=0.005
Boundary for River Rch & Prof#=UNT 099 in Runni,Reach-1,6
Up Type=0
Dn Type=3
Dn Slope=0.005
Boundary for River Rch & Prof#=UNT 099 in Runni,Reach-1,7
Up Type=0
Dn Type=3
Dn Slope=0.005

--- UNT 099 in Running Cr Watershed.g01 (geometry) ---

Geom Title=Existing Conditions

River Reach=UNT 099 in Runni,Reach-1
Reach XY= 30
      2911124.67      7044478.93      2911231.22      7044673.90
      2910825.73      7044810.57      2910907.57      7044976.75
      2910715.46      7045090.42      2910560.72      7045343.32
      2910413.48      7045454.11      2910187.20      7045776.82
      2910159.99      7045933.08      2910043.82      7045974.87
      2909880.00      7046291.87      2909525.81      7046311.25
      2909511.58      7046618.75      2909424.54      7046616.93
      2909358.46      7046716.48      2909416.43      7046797.11
      2909172.02      7046793.83      2909043.69      7046976.78
      2909053.20      7047115.44      2908850.36      7047098.01
      2908805.99      7047174.87      2908682.38      7047185.96
      2908603.15      7047311.94      2908343.26      7047398.31
      2907924.90      7047739.02      2907665.01      7047716.83
      2907496.24      7047542.52      2907293.40      7047507.65
      2907319.55      7047632.05      2907121.62      7047838.83

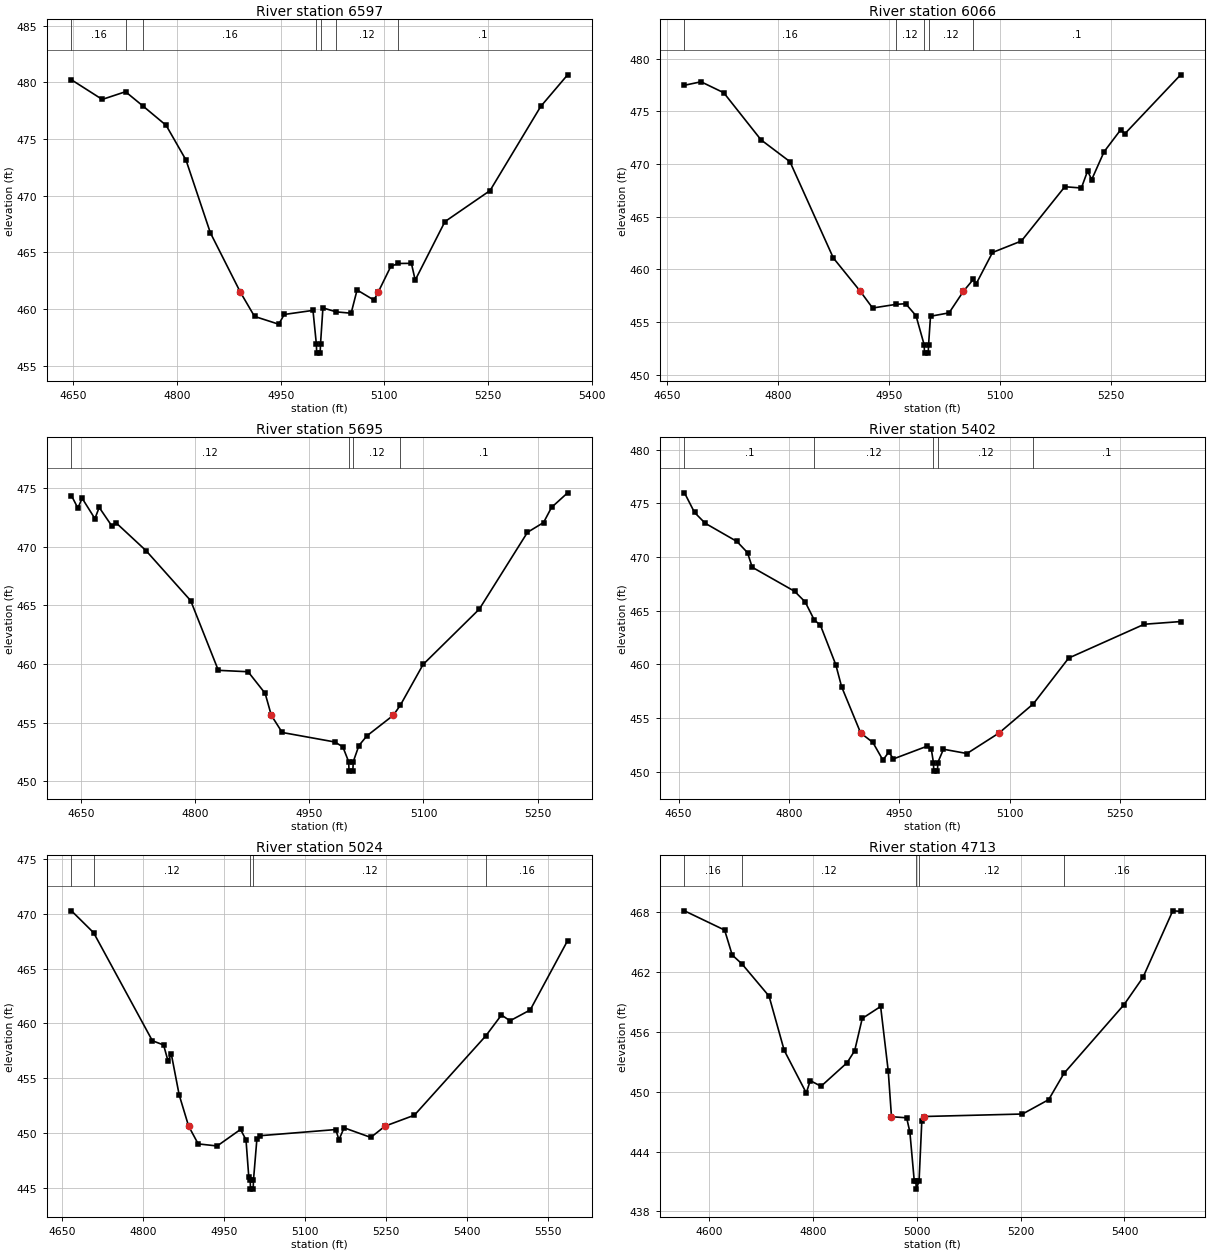
Type RM Length L Ch R = 1,6597,531,531,531
BEGIN DESCRIPTION:
UNT 099 in Running Cr Watershed 12.0
END DESCRIPTION:
XS GIS Cut Line= 3
      2910801.73      7044495.64      2911058.69      7044808.15
      2911350.21      7044922.68
#Sta/Elev= 30
  4647.3  480.21  4691.8  478.48  4725.5  479.16  4751.5  477.86  4784.3  476.19
  4813.0  473.13  4848.2  466.72  4891.7  461.47  4912.1  459.34  4947.2  458.65
  4955.1  459.51  4996.7  459.87  5001.6  456.90  5002.1  456.10  5007.1  456.10
  5007.6  456.90  5011.1  460.09  5030.4  459.74  5051.9  459.62  5060.5  461.67
  5084.9  460.78  5091.0  461.47  5109.3  463.75  5119.9  464.01  5139.1  464.02
  5144.6  462.54  5187.6  467.70  5252.9  470.44  5326.2  477.86  5365.1  480.65
#Mann=7,-1,0
  4647.3    0.16       0  4725.5    0.12       0  4751.5    0.16       0
  5001.6    0.07       0  5007.6    0.16       0  5030.4    0.12       0
  5119.9     0.1       0
Bank Sta=4891.7,5091
Exp/Cntr=0.3,0.1

Type RM Length L Ch R = 1,6066,371,371,371
BEGIN DESCRIPTION:
UNT 099 in Running Cr Watershed 11.0
END DESCRIPTION:
XS GIS Cut Line= 3
      2910674.98      7044724.96      2910825.00      7045025.00
      2910975.02      7045325.03
#Sta/Elev= 30
  4673.0  477.47  4695.4  477.80  4726.1  476.76  4776.5  472.29  4815.6  470.22
  4874.3  461.08  4910.6  457.93  4927.4  456.33  4959.3  456.68  4972.1  456.74
  4986.1  455.60  4997.1  452.85  4997.6  452.05  5002.6  452.05  5003.1  452.85
  5005.7  455.55  5030.8  455.87  5050.3  457.93  5063.7  459.06  5067.1  458.58
  5089.5  461.60  5128.6  462.69  5187.3  467.84  5209.7  467.72  5218.1  469.33
  5223.7  468.52  5240.4  471.16  5262.8  473.24  5268.4  472.86  5343.9  478.46
#Mann=5,-1,0
  4673.0    0.16       0  4959.3    0.12       0  4997.1    0.07       0
  5003.1    0.12       0  5063.7     0.1       0
Bank Sta=4910.6,5050.3
Exp/Cntr=0.3,0.1

Type RM Length L Ch R = 1,5695,293,293,293
BEGIN DESCRIPTION:
UNT 099 in Running Cr Watershed 10.0
END DESCRIPTION:
XS GIS Cut Line= 3
      2910424.98      7044974.96      2910575.00      7045275.00
      2910875.01      7045375.00
#Sta/Elev= 30
  4637.6  474.33  4646.0  473.27  4651.6  474.11  4668.4  472.37  4674.0  473.33
  4690.8  471.73  4696.3  472.01  4735.5  469.65  4794.2  465.39  4830.5  459.46
  4869.6  459.34  4892.0  457.50  4900.1  455.63  4914.4  454.17  4983.6  453.36
  4994.1  452.94  5001.7  451.68  5002.2  450.88  5007.2  450.88  5007.7  451.68
  5015.2  453.06  5025.8  453.89  5060.3  455.63  5069.5  456.48  5099.5  459.96
  5173.3  464.67  5236.6  471.21  5257.7  472.04  5268.2  473.33  5289.3  474.57
#Mann=4,-1,0
  4637.6    0.12       0  5001.7    0.07       0  5007.7    0.12       0
  5069.5     0.1       0
Bank Sta=4900.1,5060.3
Exp/Cntr=0.3,0.1

Type RM Length L Ch R = 1,5402,378,378,378
BEGIN DESCRIPTION:
UNT 099 in Running Cr Watershed 9.0
END DESCRIPTION:
XS GIS Cut Line= 3
      2910124.97      7045274.97      2910375.00      7045475.00
      2910707.98      7045596.34
#Sta/Elev= 30
  4658.0  475.97  4671.7  474.14  4686.1  473.14  4729.3  471.44  4743.7  470.40
  4750.1  469.04  4807.7  466.80  4822.1  465.81  4834.4  464.14  4842.9  463.63
  4863.7  459.97  4871.7  457.90  4897.6  453.60  4914.2  452.72  4927.8  451.08
  4935.8  451.82  4942.2  451.19  4988.2  452.38  4993.5  452.15  4996.5  450.85
  4997.0  450.05  5002.0  450.05  5002.5  450.85  5010.1  452.09  5042.1  451.69
  5085.7  453.60  5132.4  456.32  5180.4  460.58  5283.2  463.73  5332.6  463.98
#Mann=5,-1,0
  4658.0     0.1       0  4834.4    0.12       0  4996.5    0.07       0
  5002.5    0.12       0  5132.4     0.1       0
Bank Sta=4897.6,5085.7
Exp/Cntr=0.3,0.1

Type RM Length L Ch R = 1,5024,311,311,311
BEGIN DESCRIPTION:
UNT 099 in Running Cr Watershed 8.0
END DESCRIPTION:
XS GIS Cut Line= 3
      2909925.01      7045575.01      2910175.00      7045775.00
      2910694.08      7046072.03
#Sta/Elev= 30
  4667.3  470.28  4708.3  468.28  4817.0  458.42  4837.8  458.03  4845.8  456.60
  4852.2  457.17  4866.6  453.48  4884.1  450.62  4901.8  449.00  4937.0  448.81
  4980.2  450.32  4990.3  449.37  4995.4  446.01  4998.1  445.67  4998.6  444.87
  5003.6  444.87  5004.1  445.67  5010.5  449.47  5016.9  449.75  5156.5  450.31
  5162.3  449.37  5171.8  450.47  5221.3  449.59  5247.5  450.62  5301.9  451.62
  5434.2  458.87  5463.1  460.77  5478.9  460.24  5516.3  461.23  5585.5  467.56
#Mann=5,-1,0
  4667.3     0.1       0  4708.3    0.12       0  4998.1    0.07       0
  5004.1    0.12       0  5434.2    0.16       0
Bank Sta=4884.1,5247.5
Exp/Cntr=0.3,0.1

Type RM Length L Ch R = 1,4713,363,363,363
BEGIN DESCRIPTION:
UNT 099 in Running Cr Watershed 7.0
END DESCRIPTION:
XS GIS Cut Line= 3
      2909676.77      7045724.83      2910071.01      7046017.81
      2910460.73      7046269.48
#Sta/Elev= 30
  4553.0  468.13  4630.3  466.20  4644.9  463.70  4663.8  462.80  4715.8  459.58
  4745.0  454.14  4787.5  449.87  4795.1  451.11  4815.9  450.54  4866.0  452.90
  4880.6  454.10  4895.2  457.34  4930.6  458.54  4945.3  452.05  4951.5  447.49
  4980.7  447.38  4986.9  445.96  4995.3  441.08  4998.6  441.03  4999.1  440.23
  5004.6  441.03  5009.9  447.07  5013.8  447.51  5203.7  447.76  5254.1  449.20
  5283.5  451.83  5399.3  458.73  5435.6  461.45  5493.0  468.13  5508.1  468.08
#Mann=5,-1,0
  4553.0    0.16       0  4663.8    0.12       0  4998.6    0.07       0
  5004.6    0.12       0  5283.5    0.16       0
Bank Sta=4951.5,5013.8
Exp/Cntr=0.3,0.1

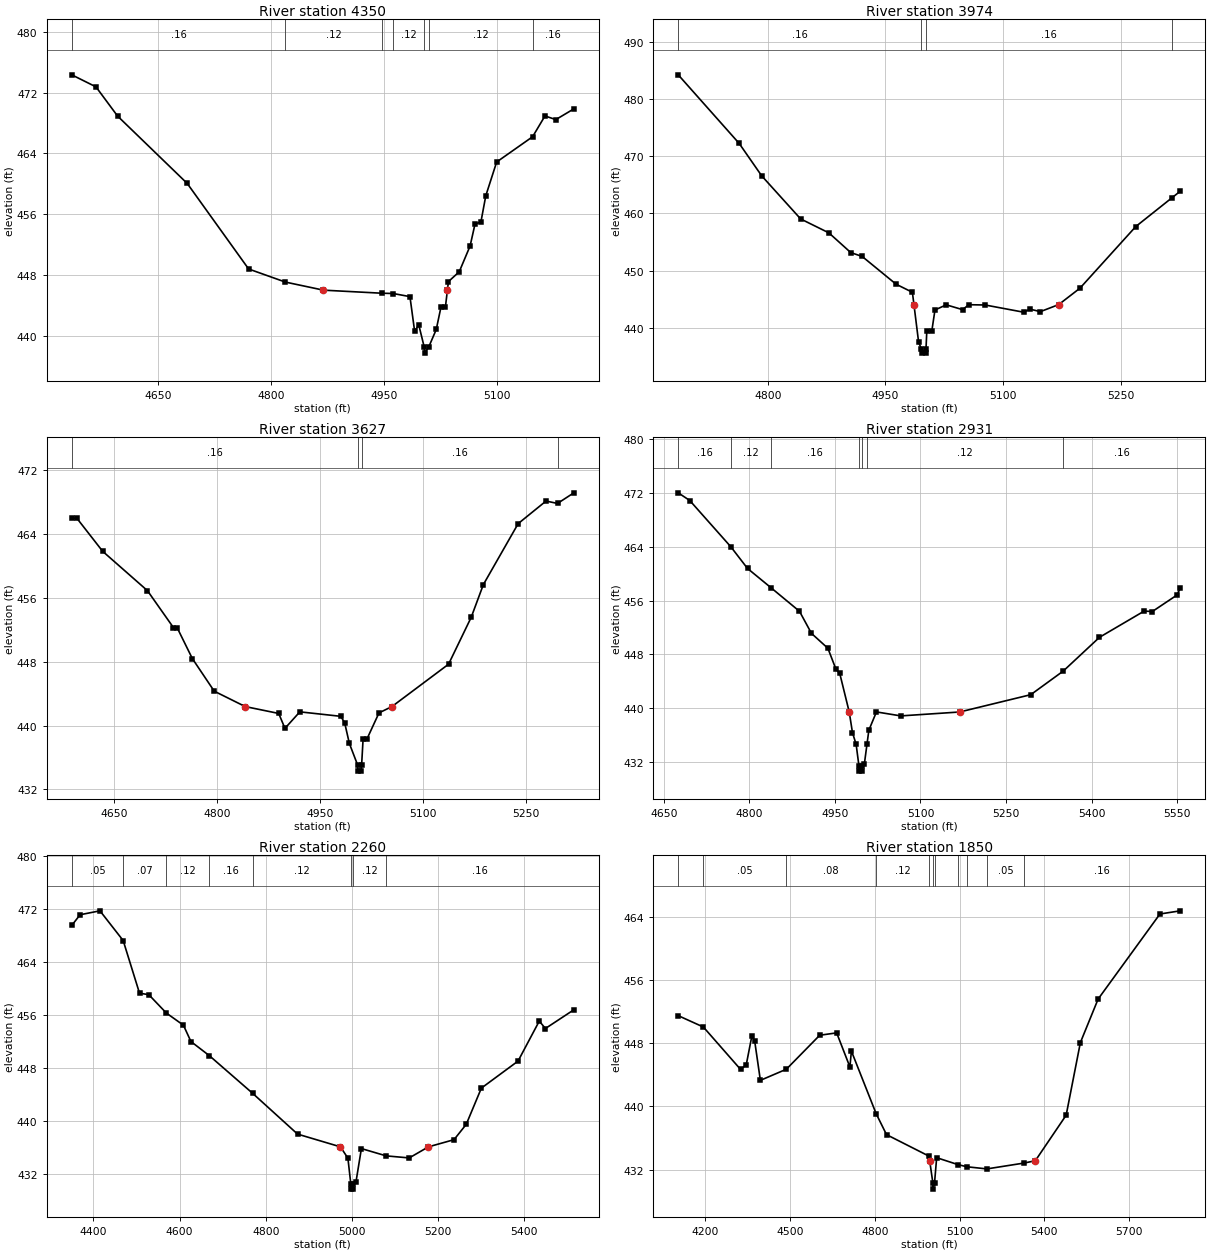
Type RM Length L Ch R = 1,4350,376,376,376
BEGIN DESCRIPTION:
UNT 099 in Running Cr Watershed 6.0
END DESCRIPTION:
XS GIS Cut Line= 3
      2909675.01      7045875.03      2909875.00      7046325.00
      2909983.44      7046460.55
#Sta/Elev= 30
  4536.0  474.33  4568.1  472.75  4596.8  468.91  4689.2  460.06  4770.6  448.83
  4819.4  447.11  4869.9  446.05  4946.9  445.65  4962.3  445.61  4984.6  445.20
  4990.8  440.65  4996.3  441.49  5003.5  438.58  5004.0  437.78  5009.5  438.58
  5019.5  440.89  5025.7  443.81  5031.6  443.81  5034.3  446.05  5035.6  447.17
  5050.0  448.47  5064.4  451.86  5070.8  454.69  5078.8  455.04  5085.2  458.45
  5099.6  462.88  5147.3  466.20  5163.7  468.93  5178.1  468.45  5202.0  469.86
#Mann=7,-1,0
  4536.0    0.16       0  4819.4    0.12       0  4946.9    0.16       0
  4962.3    0.12       0  5003.5    0.07       0  5009.5    0.12       0
  5147.3    0.16       0
Bank Sta=4869.9,5034.3
Exp/Cntr=0.3,0.1

Type RM Length L Ch R = 1,3974,347,347,347
BEGIN DESCRIPTION:
UNT 099 in Running Cr Watershed 5.0
END DESCRIPTION:
XS GIS Cut Line= 3
      2909274.99      7046124.99      2909525.00      7046325.00
      2909774.98      7046524.98
#Sta/Elev= 30
  4685.9  484.19  4763.6  472.22  4792.4  466.55  4842.0  459.04  4878.0  456.61
  4906.0  453.16  4920.4  452.50  4963.7  447.65  4984.5  446.24  4986.5  444.09
  4992.5  437.49  4995.9  436.42  4996.4  435.62  5001.4  435.62  5001.9  436.42
  5002.9  439.49  5009.3  439.49  5013.3  443.15  5027.7  444.05  5048.5  443.21
  5056.5  444.07  5077.3  444.02  5126.9  442.75  5134.1  443.31  5147.7  442.86
  5171.1  444.09  5198.2  446.95  5269.4  457.71  5315.9  462.77  5326.2  463.88
#Mann=4,-1,0
  4685.9    0.16       0  4995.9    0.07       0  5001.9    0.16       0
  5315.9    0.12       0
Bank Sta=4986.5,5171.1
Exp/Cntr=0.3,0.1

Type RM Length L Ch R = 1,3627,696,696,696
BEGIN DESCRIPTION:
UNT 099 in Running Cr Watershed 4.0
END DESCRIPTION:
XS GIS Cut Line= 3
      2909151.48      7046417.74      2909525.00      7046625.00
      2909824.99      7046675.00
#Sta/Elev= 30
  4588.0  465.96  4595.2  466.01  4633.0  461.84  4698.2  456.91  4736.0  452.29
  4741.7  452.23  4763.6  448.40  4795.5  444.31  4840.7  442.38  4889.4  441.52
  4898.5  439.65  4920.2  441.72  4979.7  441.16  4985.4  440.38  4992.3  437.77
  5004.2  435.09  5004.7  434.29  5009.7  434.29  5010.2  435.09  5012.3  438.27
  5017.7  438.27  5035.5  441.59  5054.3  442.38  5136.8  447.69  5169.8  453.57
  5187.5  457.67  5238.2  465.31  5278.8  468.14  5295.5  467.84  5319.3  469.17
#Mann=4,-1,0
  4588.0    0.16       0  5004.2    0.07       0  5010.2    0.16       0
  5295.5    0.12       0
Bank Sta=4840.7,5054.3
Exp/Cntr=0.3,0.1

Type RM Length L Ch R = 1,2931,671,671,671
BEGIN DESCRIPTION:
UNT 099 in Running Cr Watershed 3.0
END DESCRIPTION:
XS GIS Cut Line= 3
      2909025.00      7046575.00      2909060.11      7046797.56
      2909568.55      7047210.48
#Sta/Elev= 30
  4675.3  472.00  4695.5  470.86  4767.5  463.99  4796.8  460.77  4838.4  457.88
  4887.9  454.41  4908.9  451.13  4937.7  448.92  4952.0  445.77  4958.5  445.18
  4975.1  439.46  4980.8  436.39  4987.2  434.66  4992.1  431.48  4992.6  430.68
  4997.6  430.68  4998.1  431.48  5001.6  431.72  5006.2  434.65  5009.5  436.75
  5022.8  439.47  5065.5  438.88  5168.7  439.46  5293.4  442.03  5350.4  445.54
  5413.9  450.55  5492.2  454.44  5506.6  454.38  5549.7  456.82  5555.6  457.85
#Mann=7,-1,0
  4675.3    0.16       0  4767.5    0.12       0  4838.4    0.16       0
  4992.1    0.07       0  4998.1    0.16       0  5006.2    0.12       0
  5350.4    0.16       0
Bank Sta=4975.1,5168.7
Exp/Cntr=0.3,0.1

Type RM Length L Ch R = 1,2260,410,410,410
BEGIN DESCRIPTION:
UNT 099 in Running Cr Watershed 2.0
END DESCRIPTION:
XS GIS Cut Line= 4
      2908666.32      7046540.78      2908777.44      7047106.76
      2908853.82      7047294.26      2909114.24      7047578.98
#Sta/Elev= 30
  4349.6  469.51  4368.9  471.12  4415.0  471.71  4468.9  467.23  4506.8  459.30
  4528.3  459.08  4569.1  456.31  4608.7  454.48  4626.1  452.02  4669.2  449.87
  4769.4  444.21  4873.6  438.07  4973.1  436.15  4990.4  434.44  4997.1  430.58
  4997.6  429.78  5002.6  429.78  5003.1  430.58  5009.1  430.86  5021.7  435.89
  5079.2  434.79  5132.7  434.48  5177.2  436.15  5236.6  437.23  5265.0  439.54
  5300.1  445.00  5385.2  449.07  5434.5  455.10  5448.7  453.98  5514.7  456.80
#Mann=8,-1,0
  4349.6    0.05       0  4468.9    0.07       0  4569.1    0.12       0
  4669.2    0.16       0  4769.4    0.12       0  4997.1    0.07       0
  5003.1    0.12       0  5079.2    0.16       0
Bank Sta=4973.1,5177.2
Exp/Cntr=0.3,0.1

Type RM Length L Ch R = 1,1850,130,130,130
BEGIN DESCRIPTION:
Mapping XS 6f132ea0
END DESCRIPTION:
XS GIS Cut Line= 5
      2908402.44      7046464.38      2908412.85      7047047.73
      2908572.57      7047582.45      2908652.44      7047655.37
      2909176.75      7047710.93
#Sta/Elev= 30
  4104.0  451.48  4193.0  450.04  4324.7  444.67  4344.7  445.26  4364.7  448.93
  4374.7  448.23  4394.7  443.29  4486.7  444.70  4604.7  449.00  4664.7  449.30
  4711.6  444.98  4716.8  447.00  4804.3  439.08  4841.1  436.42  4990.7  433.71
  4993.9  433.11  5005.1  430.32  5005.6  429.52  5011.1  430.32  5018.6  433.50
  5093.5  432.63  5125.5  432.35  5196.3  432.08  5327.8  432.82  5367.7  433.11
  5476.9  438.88  5527.2  448.07  5590.0  453.58  5808.8  464.35  5880.9  464.75
#Mann=11,-1,0
  4104.0    0.07       0  4193.0    0.05       0  4486.7    0.08       0
  4804.3    0.12       0  4990.7    0.05       0  5005.1    0.04       0
  5011.1    0.05       0  5093.5    0.08       0  5125.5    0.16       0
  5196.3    0.05       0  5327.8    0.16       0
Bank Sta=4993.9,5367.7
Exp/Cntr=0.3,0.1

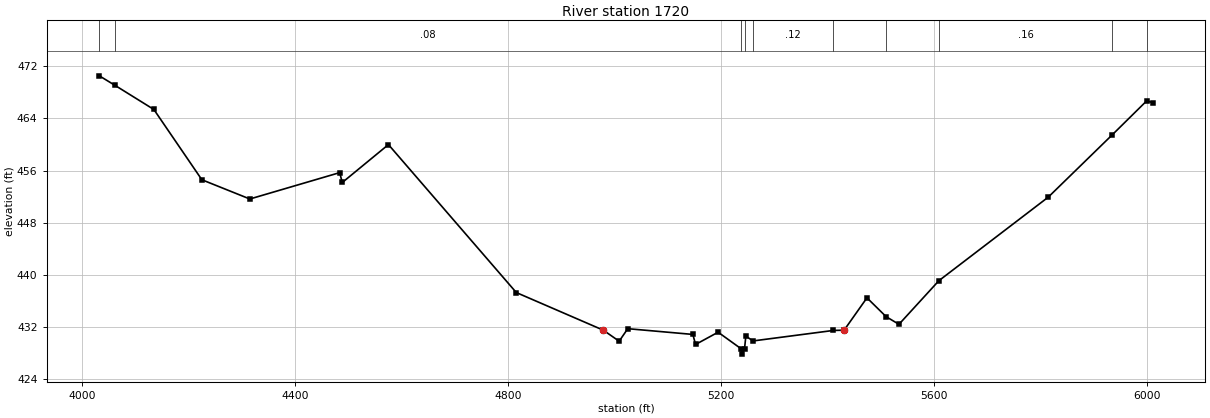
Type RM Length L Ch R = 1,1720,0,0,0
BEGIN DESCRIPTION:
UNT 099 in Running Cr Watershed 1.0
END DESCRIPTION:
XS GIS Cut Line= 5
      2908270.49      7046422.70      2908294.80      7046988.70
      2908418.06      7047566.83      2908490.08      7047730.18
      2909130.79      7047766.44
#Sta/Elev= 30
  4032.3  470.52  4062.1  469.04  4134.7  465.36  4224.8  454.59  4314.9  451.64
  4483.5  455.68  4488.5  454.17  4575.1  459.98  4815.2  437.30  4978.6  431.53
  5008.3  429.84  5024.5  431.76  5146.7  430.88  5151.8  429.34  5194.1  431.22
  5237.7  428.66  5238.2  427.86  5243.7  428.66  5246.2  430.63  5259.5  429.88
  5410.5  431.49  5430.7  431.53  5473.6  436.49  5509.6  433.60  5533.7  432.43
  5608.7  439.12  5814.1  451.93  5934.2  461.48  5998.8  466.68  6010.2  466.41
#Mann=10,-1,0
  4032.3    0.05       0  4062.1    0.08       0  5237.7    0.07       0
  5243.7    0.08       0  5259.5    0.12       0  5410.5    0.08       0
  5509.6    0.05       0  5608.7    0.16       0  5934.2    0.05       0
  5998.8    0.16       0
Bank Sta=4978.6,5430.7
Exp/Cntr=0.3,0.1

Chan Stop Cuts=-1