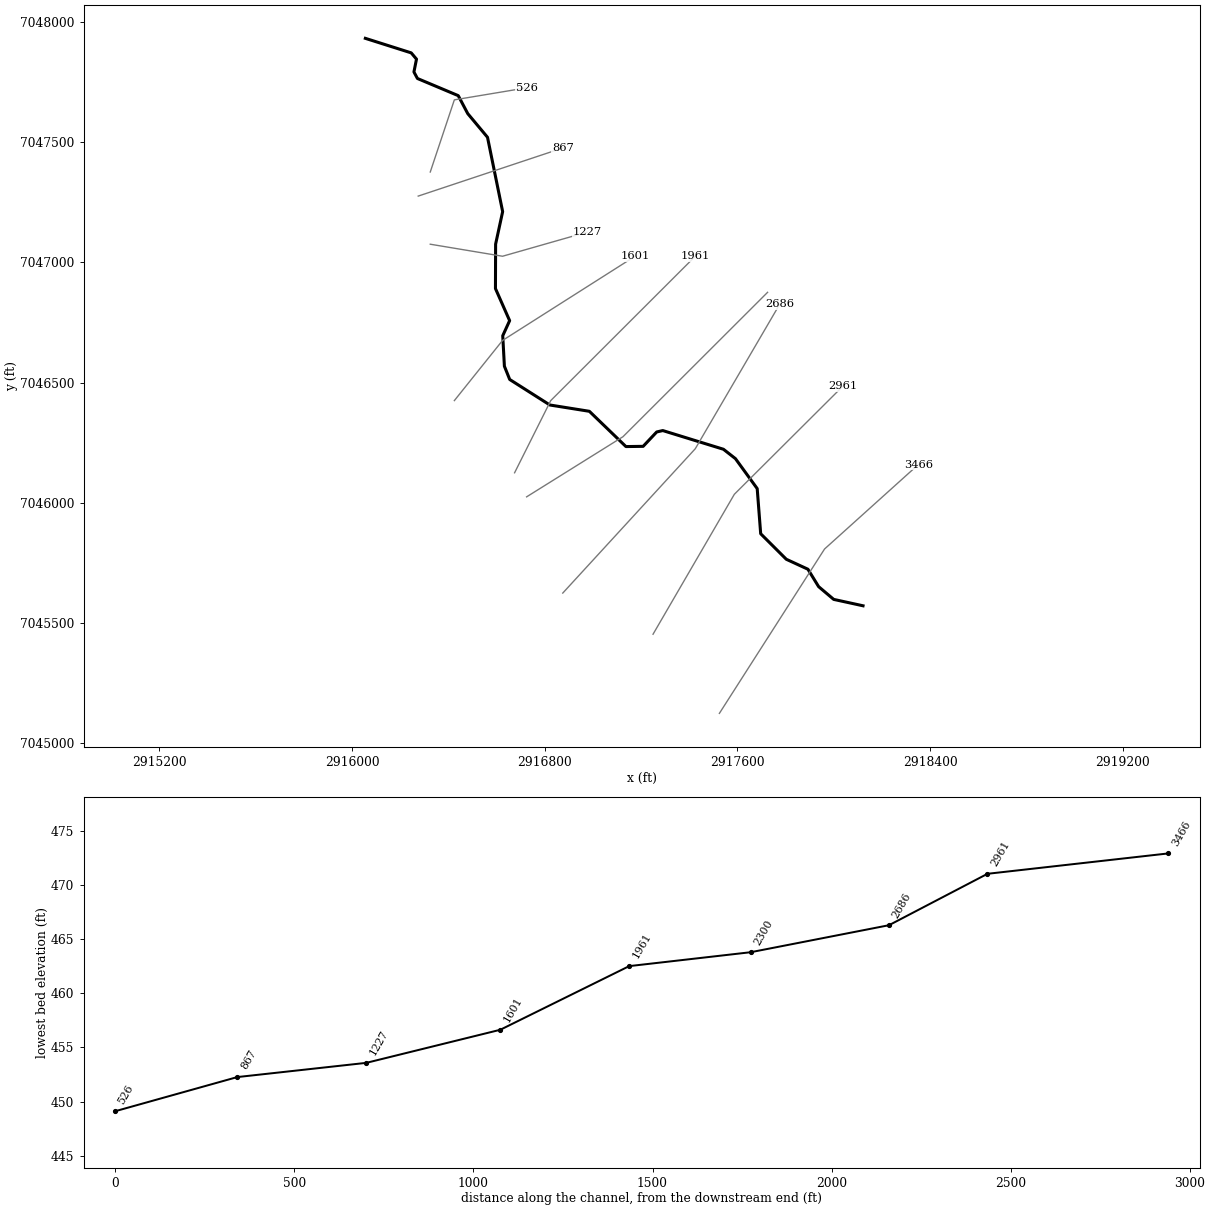
--- UNT 100 in Running Cr Watershed.prj (project) ---

Proj Title=UNT 100 in Running Cr Watershed Base Level Engineering
Current Plan=p01
Default Exp/Contr=0.3,0.1
English Units
Geom File=g01
Flow File=f01
Plan File=p01
BEGIN DESCRIPTION:
UNT 100 in Running Cr Watershed
END DESCRIPTION:

--- UNT 100 in Running Cr Watershed.p01 (plan) ---

Plan Title=Multiple Run
Short Identifier=Multiple
Geom File=g01
Flow File=f01
Subcritical Flow
K Sum by GR= 0
Std Step Tol= 0.01
Critical Tol= 0.01
Num of Std Step Trials= 20
Max Error Tol= 0.3
Flow Tol Ratio= 0.001
Split Flow NTrial= 30
Split Flow Tol= 0.02
Split Flow Ratio= 0.02
Log Output Level= 0
Friction Slope Method= 1
Unsteady Friction Slope Method= 2
Unsteady Bridges Friction Slope Method= 1
Parabolic Critical Depth
Global Vel Dist=  1 , 1 , 1
Global Log Level= 0
CheckData=True
Encroach Param= -1, 0, 0, 0
BEGIN DESCRIPTION:
Multiple Run
END DESCRIPTION:

--- UNT 100 in Running Cr Watershed.f01 (steady flow) ---

Flow Title=Multiple
Number of Profiles=7
Profile Names=10-year,25-year,50-year,1pct_min,100-year,1pct_plu,500-year
River Rch & RM= UNT 100 in Runni,Reach-1,3466
     309     398     467     274     546    1089     744
River Rch & RM= UNT 100 in Runni,Reach-1,1227
     427     560     667     395     788    1572    1102
Boundary for River Rch & Prof#=UNT 100 in Runni,Reach-1,1
Up Type=0
Dn Type=3
Dn Slope=0.005
Boundary for River Rch & Prof#=UNT 100 in Runni,Reach-1,2
Up Type=0
Dn Type=3
Dn Slope=0.005
Boundary for River Rch & Prof#=UNT 100 in Runni,Reach-1,3
Up Type=0
Dn Type=3
Dn Slope=0.005
Boundary for River Rch & Prof#=UNT 100 in Runni,Reach-1,4
Up Type=0
Dn Type=3
Dn Slope=0.005
Boundary for River Rch & Prof#=UNT 100 in Runni,Reach-1,5
Up Type=0
Dn Type=3
Dn Slope=0.005
Boundary for River Rch & Prof#=UNT 100 in Runni,Reach-1,6
Up Type=0
Dn Type=3
Dn Slope=0.005
Boundary for River Rch & Prof#=UNT 100 in Runni,Reach-1,7
Up Type=0
Dn Type=3
Dn Slope=0.005

--- UNT 100 in Running Cr Watershed.g01 (geometry) ---

Geom Title=Existing Conditions

River Reach=UNT 100 in Runni,Reach-1
Reach XY= 30
      2918121.24      7045572.16      2917999.44      7045598.75
      2917936.83      7045651.79      2917892.50      7045724.09
      2917802.66      7045765.54      2917696.42      7045871.66
      2917681.96      7046059.24      2917591.72      7046183.69
      2917541.81      7046222.77      2917290.11      7046300.46
      2917264.86      7046294.65      2917208.57      7046234.87
      2917137.10      7046233.94      2916985.39      7046380.52
      2916821.46      7046406.70      2916654.77      7046512.77
      2916632.73      7046567.88      2916625.84      7046694.61
      2916654.45      7046757.31      2916595.59      7046890.71
      2916596.26      7047075.32      2916625.46      7047210.50
      2916562.59      7047519.47      2916480.55      7047617.90
      2916441.25      7047692.46      2916271.80      7047763.81
      2916257.24      7047790.96      2916267.86      7047844.27
      2916246.03      7047870.25      2916055.59      7047930.71

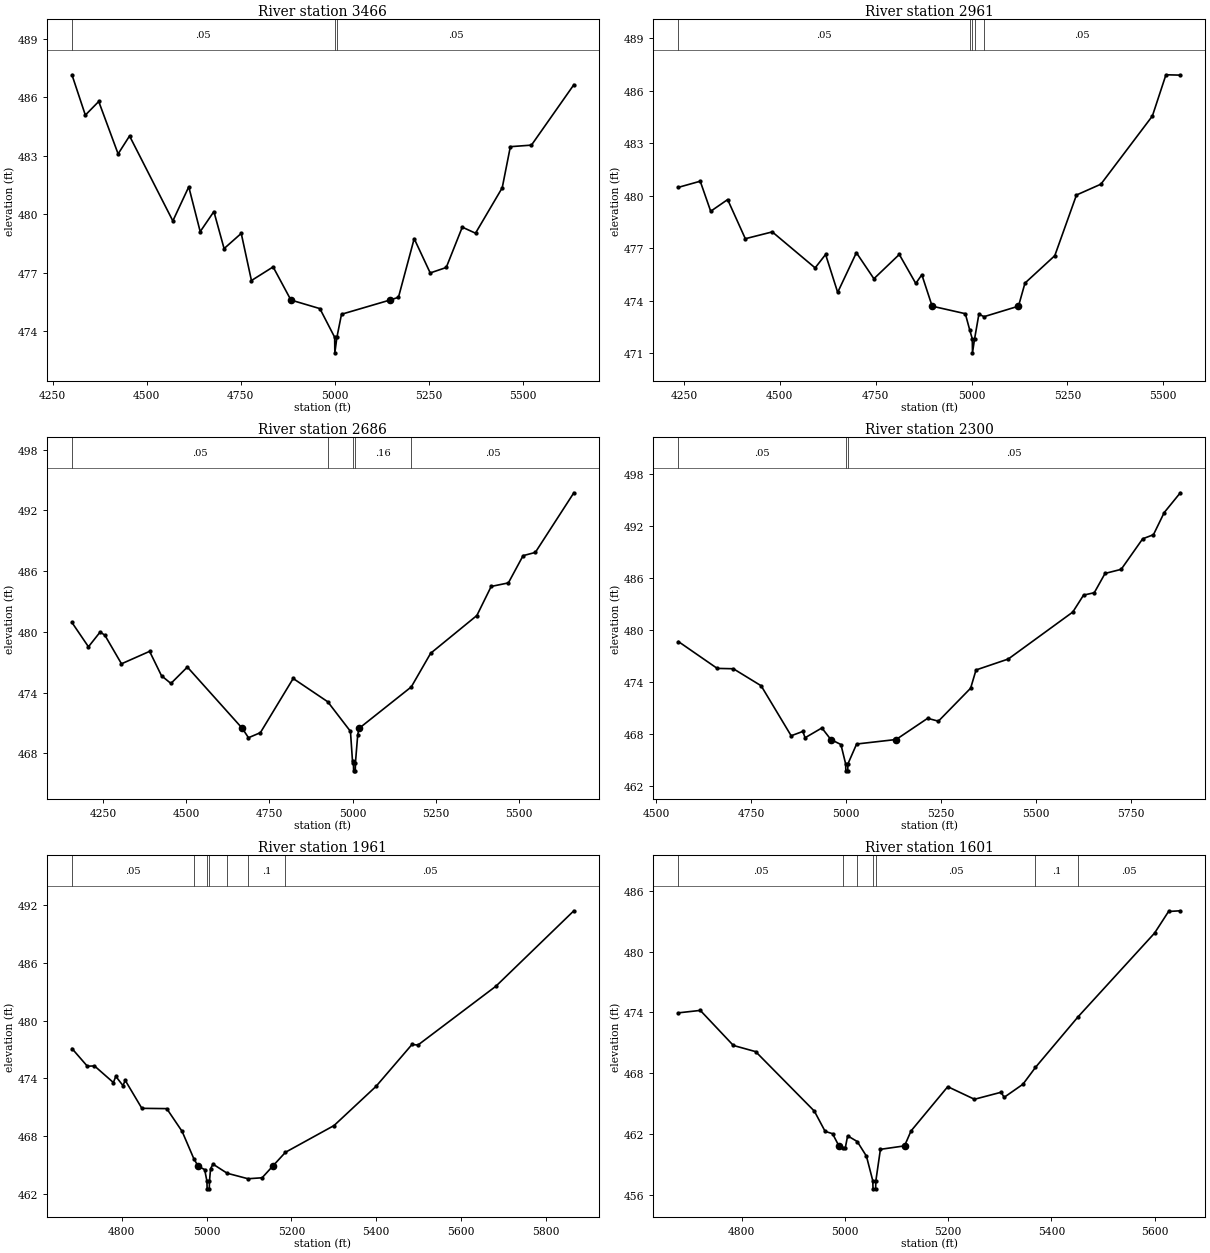
Type RM Length L Ch R = 1,3466,505,505,505
BEGIN DESCRIPTION:
UNT 100 in Running Cr Watershed 9.0
END DESCRIPTION:
XS GIS Cut Line= 3
      2917524.99      7045124.99      2917961.46      7045808.15
      2918350.17      7046158.67
#Sta/Elev= 30
  4301.0  487.16  4336.6  485.09  4372.2  485.79  4423.7  483.10  4454.1  484.02
  4569.2  479.66  4611.5  481.41  4641.9  479.11  4678.3  480.14  4705.4  478.24
  4751.0  479.02  4778.1  476.60  4835.7  477.30  4883.0  475.60  4960.0  475.16
  4999.3  473.69  4999.8  472.89  5005.3  473.69  5017.5  474.87  5146.5  475.60
  5168.9  475.74  5210.7  478.75  5253.3  476.99  5295.9  477.27  5338.5  479.34
  5373.7  479.03  5444.7  481.36  5466.3  483.47  5522.4  483.55  5635.1  486.65
#Mann=3,-1,0
  4301.0    0.05       0  4999.3    0.03       0  5005.3    0.05       0
Bank Sta=4883,5146.5
Exp/Cntr=0.3,0.1

Type RM Length L Ch R = 1,2961,275,275,275
BEGIN DESCRIPTION:
UNT 100 in Running Cr Watershed 8.0
END DESCRIPTION:
XS GIS Cut Line= 3
      2917249.64      7045453.95      2917587.03      7046035.53
      2918037.83      7046485.21
#Sta/Elev= 30
  4235.4  480.48  4292.3  480.83  4319.6  479.11  4363.8  479.78  4409.9  477.54
  4480.2  477.93  4592.0  475.87  4619.3  476.64  4650.8  474.47  4699.6  476.74
  4745.3  475.25  4811.5  476.64  4854.5  474.98  4870.3  475.48  4897.2  473.68
  4983.7  473.25  4995.3  472.31  5001.9  471.81  5002.4  471.01  5007.9  471.81
  5019.1  473.22  5032.6  473.08  5122.4  473.68  5139.3  475.00  5217.1  476.57
  5273.6  480.04  5337.3  480.66  5471.6  484.56  5507.0  486.92  5544.5  486.90
#Mann=5,-1,0
  4235.4    0.05       0  4995.3    0.16       0  5001.9    0.07       0
  5007.9    0.16       0  5032.6    0.05       0
Bank Sta=4897.2,5122.4
Exp/Cntr=0.3,0.1

Type RM Length L Ch R = 1,2686,386,386,386
BEGIN DESCRIPTION:
UNT 100 in Running Cr Watershed 7.0
END DESCRIPTION:
XS GIS Cut Line= 3
      2916875.00      7045625.00      2917425.00      7046225.00
      2917775.02      7046825.03
#Sta/Elev= 30
  4156.3  480.92  4205.9  478.52  4241.1  479.98  4255.3  479.66  4305.2  476.84
  4389.7  478.07  4425.5  475.66  4453.8  474.90  4503.2  476.52  4668.2  470.47
  4686.9  469.54  4722.7  470.04  4821.3  475.39  4925.2  473.09  4993.4  470.17
  4999.6  467.20  5002.4  467.07  5002.9  466.27  5007.9  466.27  5008.4  467.07
  5015.3  469.84  5019.5  470.47  5176.3  474.56  5234.5  477.88  5373.4  481.61
  5416.4  484.48  5468.1  484.83  5512.3  487.52  5549.1  487.84  5664.9  493.73
#Mann=5,-1,0
  4156.3    0.05       0  4925.2    0.16       0  5002.4    0.07       0
  5008.4    0.16       0  5176.3    0.05       0
Bank Sta=4668.2,5019.5
Exp/Cntr=0.3,0.1

Type RM Length L Ch R = 1,2300,339,339,339
BEGIN DESCRIPTION:
UNT 100 in Running Cr Watershed 6.0
END DESCRIPTION:
XS GIS Cut Line= 3
      2916724.96      7046024.97      2917125.00      7046275.00
      2917725.02      7046875.02
#Sta/Elev= 30
  4558.8  478.67  4660.9  475.58  4703.3  475.54  4776.4  473.58  4855.4  467.82
  4886.1  468.32  4892.0  467.59  4936.2  468.72  4959.7  467.39  4986.3  466.81
  4998.7  464.58  4999.2  463.78  5004.2  463.78  5004.7  464.58  5027.6  466.87
  5131.6  467.39  5214.4  469.83  5242.7  469.50  5327.5  473.30  5341.7  475.40
  5426.5  476.66  5596.2  482.07  5624.5  484.02  5652.8  484.30  5681.1  486.52
  5723.5  486.99  5780.1  490.51  5808.4  490.98  5836.7  493.53  5879.1  495.81
#Mann=3,-1,0
  4558.8    0.05       0  4998.7    0.03       0  5004.7    0.05       0
Bank Sta=4959.7,5131.6
Exp/Cntr=0.3,0.1

Type RM Length L Ch R = 1,1961,360,360,360
BEGIN DESCRIPTION:
UNT 100 in Running Cr Watershed 5.0
END DESCRIPTION:
XS GIS Cut Line= 3
      2916675.00      7046125.00      2916825.00      7046425.00
      2917424.98      7047024.98
#Sta/Elev= 30
  4682.4  477.09  4718.7  475.25  4735.5  475.28  4780.2  473.55  4785.8  474.20
  4802.6  473.24  4808.2  473.77  4847.3  470.87  4906.0  470.84  4942.3  468.47
  4969.8  465.64  4980.0  464.86  4995.4  464.50  5000.8  463.30  5001.3  462.50
  5006.3  462.50  5006.8  463.30  5009.4  464.59  5015.0  465.07  5048.6  464.12
  5097.7  463.55  5130.9  463.65  5156.0  464.86  5186.0  466.30  5300.6  469.08
  5399.6  473.15  5484.5  477.51  5498.6  477.45  5682.5  483.57  5866.3  491.41
#Mann=7,-1,0
  4682.4    0.05       0  4969.8     0.1       0  5000.8    0.07       0
  5006.8     0.1       0  5048.6    0.05       0  5097.7     0.1       0
  5186.0    0.05       0
Bank Sta=4980,5156
Exp/Cntr=0.3,0.1

Type RM Length L Ch R = 1,1601,374,374,374
BEGIN DESCRIPTION:
UNT 100 in Running Cr Watershed 4.0
END DESCRIPTION:
XS GIS Cut Line= 3
      2916425.03      7046425.03      2916625.00      7046675.00
      2917174.97      7047024.98
#Sta/Elev= 30
  4677.7  473.96  4720.1  474.20  4784.1  470.75  4827.3  470.14  4941.0  464.28
  4961.8  462.29  4976.2  462.06  4988.5  460.86  4997.0  460.64  5000.8  460.64
  5005.4  461.85  5024.0  461.29  5041.8  459.85  5054.1  457.43  5054.6  456.63
  5059.6  456.63  5060.1  457.43  5068.9  460.52  5115.6  460.86  5128.2  462.33
  5199.3  466.69  5251.0  465.45  5302.6  466.14  5308.5  465.64  5344.9  466.93
  5369.2  468.59  5451.7  473.57  5599.8  481.81  5626.9  483.94  5649.7  484.01
#Mann=7,-1,0
  4677.7    0.05       0  4997.0    0.16       0  5024.0    0.05       0
  5054.1    0.07       0  5060.1    0.05       0  5369.2     0.1       0
  5451.7    0.05       0
Bank Sta=4988.5,5115.6
Exp/Cntr=0.3,0.1

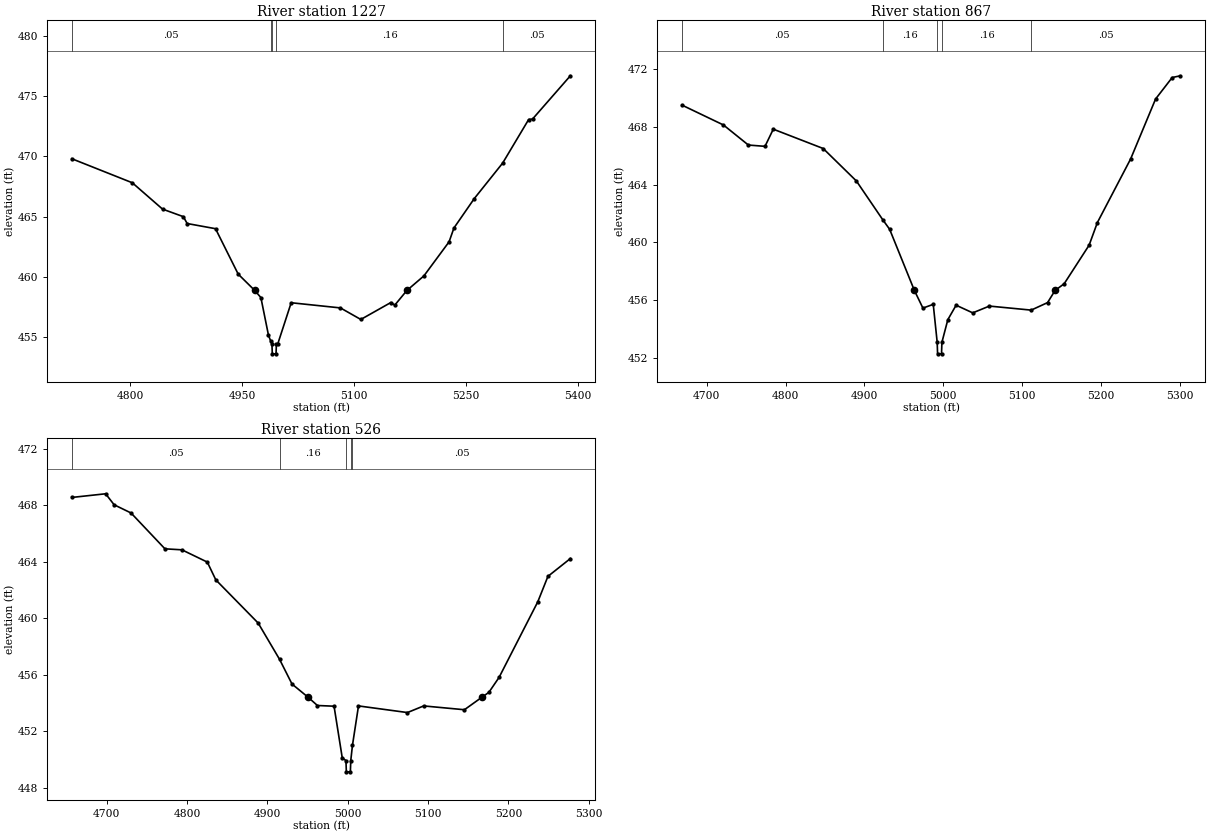
Type RM Length L Ch R = 1,1227,360,360,360
BEGIN DESCRIPTION:
UNT 100 in Running Cr Watershed 3.0
END DESCRIPTION:
XS GIS Cut Line= 3
      2916325.02      7047075.00      2916625.00      7047025.00
      2916974.98      7047124.99
#Sta/Elev= 30
  4721.5  469.81  4802.6  467.81  4843.1  465.62  4871.0  464.99  4876.1  464.42
  4914.1  463.99  4944.5  460.21  4966.7  458.85  4974.9  458.26  4985.1  455.12
  4988.0  454.65  4989.7  454.38  4990.2  453.58  4995.2  453.58  4995.7  454.38
  4997.7  454.44  5015.5  457.83  5081.5  457.40  5108.8  456.44  5149.1  457.85
  5154.3  457.63  5170.5  458.85  5193.3  460.06  5227.1  462.90  5233.6  464.05
  5260.9  466.50  5298.9  469.45  5333.7  473.07  5338.9  473.11  5389.6  476.71
#Mann=5,-1,0
  4721.5    0.05       0  4988.0    0.16       0  4989.7    0.07       0
  4995.7    0.16       0  5298.9    0.05       0
Bank Sta=4966.7,5170.5
Exp/Cntr=0.3,0.1

Type RM Length L Ch R = 1,867,341,341,341
BEGIN DESCRIPTION:
UNT 100 in Running Cr Watershed 2.0
END DESCRIPTION:
XS GIS Cut Line= 3
      2916275.02      7047275.01      2916575.00      7047375.00
      2916874.96      7047474.99
#Sta/Elev= 30
  4668.6  469.51  4721.3  468.13  4752.9  466.74  4774.0  466.65  4784.5  467.84
  4847.8  466.50  4889.9  464.25  4923.4  461.56  4932.1  460.90  4963.5  456.66
  4974.3  455.44  4987.4  455.70  4992.4  453.07  4992.9  452.27  4997.9  452.27
  4998.4  453.07  5005.9  454.64  5016.4  455.64  5037.5  455.11  5058.6  455.58
  5111.6  455.30  5132.4  455.82  5141.9  456.66  5153.5  457.13  5185.1  459.80
  5195.6  461.37  5237.8  465.78  5269.4  469.93  5290.5  471.42  5301.0  471.54
#Mann=5,-1,0
  4668.6    0.05       0  4923.4    0.16       0  4992.4    0.07       0
  4998.4    0.16       0  5111.6    0.05       0
Bank Sta=4963.5,5141.9
Exp/Cntr=0.3,0.1

Type RM Length L Ch R = 1,526,0,0,0
BEGIN DESCRIPTION:
UNT 100 in Running Cr Watershed 1.0
END DESCRIPTION:
XS GIS Cut Line= 3
      2916325.01      7047375.04      2916425.00      7047675.00
      2916724.97      7047725.00
#Sta/Elev= 30
  4656.7  468.56  4698.8  468.82  4709.4  468.04  4730.4  467.46  4772.6  464.92
  4793.7  464.85  4825.3  463.98  4835.9  462.72  4888.6  459.66  4915.2  457.09
  4930.7  455.34  4950.8  454.40  4962.3  453.82  4983.0  453.77  4993.2  450.11
  4997.8  449.92  4998.3  449.12  5003.3  449.12  5003.8  449.92  5005.9  451.00
  5013.4  453.79  5074.3  453.32  5094.5  453.79  5145.2  453.52  5166.8  454.40
  5175.6  454.75  5188.3  455.81  5236.5  461.17  5249.1  462.97  5277.0  464.23
#Mann=5,-1,0
  4656.7    0.05       0  4915.2    0.16       0  4997.8    0.07       0
  5003.8    0.16       0  5005.9    0.05       0
Bank Sta=4950.8,5166.8
Exp/Cntr=0.3,0.1

Chan Stop Cuts=-1