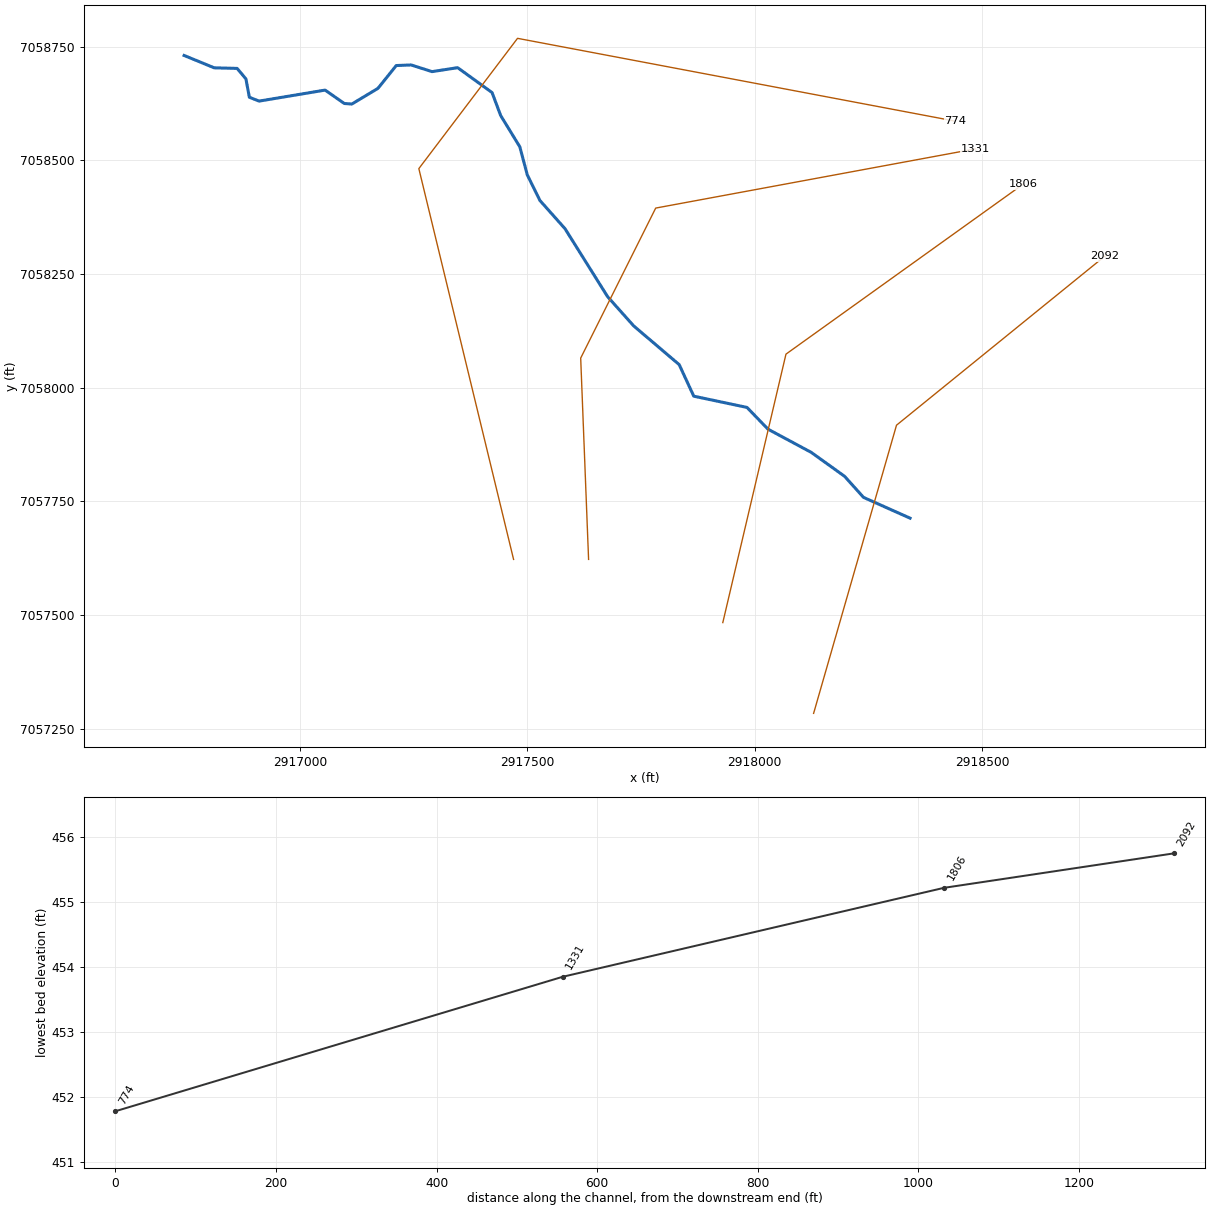
--- UNT 101 in Running Cr Watershed.prj (project) ---

Proj Title=UNT 101 in Running Cr Watershed Base Level Engineering
Current Plan=p01
Default Exp/Contr=0.3,0.1
English Units
Geom File=g01
Flow File=f01
Plan File=p01
BEGIN DESCRIPTION:
UNT 101 in Running Cr Watershed
END DESCRIPTION:

--- UNT 101 in Running Cr Watershed.p01 (plan) ---

Plan Title=Multiple Run
Short Identifier=Multiple
Geom File=g01
Flow File=f01
Subcritical Flow
K Sum by GR= 0
Std Step Tol= 0.01
Critical Tol= 0.01
Num of Std Step Trials= 20
Max Error Tol= 0.3
Flow Tol Ratio= 0.001
Split Flow NTrial= 30
Split Flow Tol= 0.02
Split Flow Ratio= 0.02
Log Output Level= 0
Friction Slope Method= 1
Unsteady Friction Slope Method= 2
Unsteady Bridges Friction Slope Method= 1
Parabolic Critical Depth
Global Vel Dist=  1 , 1 , 1
Global Log Level= 0
CheckData=True
Encroach Param= -1, 0, 0, 0
BEGIN DESCRIPTION:
Multiple Run
END DESCRIPTION:

--- UNT 101 in Running Cr Watershed.f01 (steady flow) ---

Flow Title=Multiple
Number of Profiles=7
Profile Names=10-year,25-year,50-year,1pct_min,100-year,1pct_plu,500-year
River Rch & RM= UNT 101 in Runni,Reach-1,2092
     373     482     567     332     663    1323     906
Boundary for River Rch & Prof#=UNT 101 in Runni,Reach-1,1
Up Type=0
Dn Type=3
Dn Slope=0.005
Boundary for River Rch & Prof#=UNT 101 in Runni,Reach-1,2
Up Type=0
Dn Type=3
Dn Slope=0.005
Boundary for River Rch & Prof#=UNT 101 in Runni,Reach-1,3
Up Type=0
Dn Type=3
Dn Slope=0.005
Boundary for River Rch & Prof#=UNT 101 in Runni,Reach-1,4
Up Type=0
Dn Type=3
Dn Slope=0.005
Boundary for River Rch & Prof#=UNT 101 in Runni,Reach-1,5
Up Type=0
Dn Type=3
Dn Slope=0.005
Boundary for River Rch & Prof#=UNT 101 in Runni,Reach-1,6
Up Type=0
Dn Type=3
Dn Slope=0.005
Boundary for River Rch & Prof#=UNT 101 in Runni,Reach-1,7
Up Type=0
Dn Type=3
Dn Slope=0.005

--- UNT 101 in Running Cr Watershed.g01 (geometry) ---

Geom Title=Existing Conditions

River Reach=UNT 101 in Runni,Reach-1
Reach XY= 30
      2918341.94      7057713.28      2918239.58      7057758.94
      2918197.88      7057805.36      2918124.48      7057858.01
      2918029.50      7057908.95      2917983.34      7057956.76
      2917866.33      7057981.48      2917834.29      7058050.86
      2917734.05      7058136.14      2917676.80      7058200.34
      2917583.21      7058349.72      2917528.07      7058411.74
      2917500.30      7058467.95      2917483.75      7058529.95
      2917441.70      7058598.61      2917422.75      7058649.14
      2917347.10      7058703.85      2917290.75      7058695.18
      2917244.77      7058709.85      2917212.11      7058708.54
      2917171.81      7058658.36      2917114.47      7058623.90
      2917097.88      7058625.10      2917055.60      7058654.57
      2916910.43      7058630.34      2916889.06      7058638.84
      2916881.56      7058679.14      2916862.18      7058702.23
      2916811.76      7058703.55      2916745.59      7058730.71

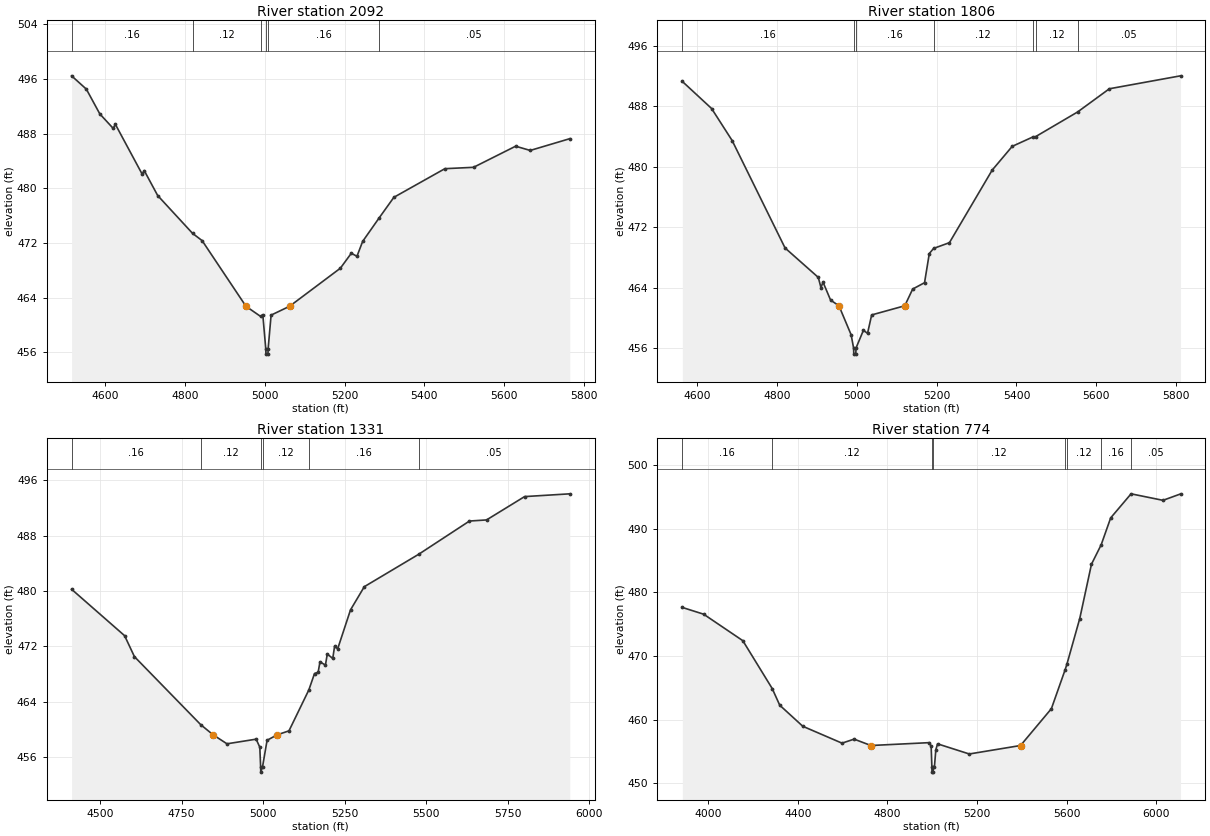
Type RM Length L Ch R = 1,2092,286,286,286
BEGIN DESCRIPTION:
UNT 101 in Running Cr Watershed 2.0
END DESCRIPTION:
XS GIS Cut Line= 3
      2918129.82      7057284.00      2918312.11      7057917.68
      2918770.53      7058289.61
#Sta/Elev= 30
  4515.1  496.48  4552.2  494.53  4585.9  490.91  4619.6  488.78  4624.8  489.40
  4692.2  482.09  4697.4  482.61  4731.1  478.96  4818.5  473.43  4842.6  472.36
  4952.6  462.75  4989.2  461.27  4994.8  461.52  5002.2  456.55  5002.7  455.75
  5007.7  455.75  5008.2  456.55  5015.6  461.46  5061.9  462.75  5189.3  468.32
  5216.8  470.51  5231.0  470.07  5245.3  472.25  5285.6  475.60  5323.6  478.70
  5451.5  482.89  5523.4  483.09  5629.0  486.18  5665.6  485.56  5764.8  487.28
#Mann=6,-1,0
  4515.1    0.16       0  4818.5    0.12       0  4989.2    0.16       0
  5002.2    0.07       0  5008.2    0.16       0  5285.6    0.05       0
Bank Sta=4952.6,5061.9
Exp/Cntr=0.3,0.1

Type RM Length L Ch R = 1,1806,475,475,475
BEGIN DESCRIPTION:
Mapping XS b539cc2f
END DESCRIPTION:
XS GIS Cut Line= 3
      2917930.16      7057483.65      2918069.05      7058073.93
      2918589.91      7058447.20
#Sta/Elev= 30
  4563.4  491.26  4636.7  487.68  4688.1  483.45  4820.6  469.25  4903.8  465.36
  4910.5  464.01  4915.6  464.74  4934.6  462.36  4955.5  461.61  4986.0  457.78
  4992.2  456.02  4992.7  455.22  4997.7  455.22  4998.2  456.02  5016.8  458.37
  5027.1  457.97  5037.4  460.40  5120.3  461.61  5140.1  463.82  5169.8  464.66
  5181.7  468.51  5192.5  469.19  5232.1  469.95  5339.0  479.53  5389.3  482.68
  5440.6  483.91  5448.4  483.98  5552.9  487.22  5632.5  490.29  5810.6  492.00
#Mann=7,-1,0
  4563.4    0.16       0  4992.2    0.07       0  4998.2    0.16       0
  5192.5    0.12       0  5440.6    0.05       0  5448.4    0.12       0
  5552.9    0.05       0
Bank Sta=4955.5,5120.3
Exp/Cntr=0.3,0.1

Type RM Length L Ch R = 1,1331,557,557,557
BEGIN DESCRIPTION:
Mapping XS a9832f7c
END DESCRIPTION:
XS GIS Cut Line= 4
      2917635.02      7057622.57      2917617.66      7058065.25
      2917782.59      7058395.11      2918485.73      7058525.32
#Sta/Elev= 30
  4412.7  480.26  4575.3  473.55  4605.3  470.53  4808.6  460.70  4846.5  459.24
  4889.0  457.94  4978.4  458.61  4989.6  457.45  4992.1  454.65  4992.6  453.85
  4998.1  454.65  5011.9  458.45  5043.0  459.24  5079.0  459.81  5139.9  465.72
  5157.3  468.09  5168.4  468.27  5174.0  469.77  5190.8  469.31  5196.4  470.90
  5213.2  470.27  5218.8  472.02  5228.3  471.66  5267.6  477.28  5309.9  480.63
  5476.2  485.30  5632.2  490.11  5684.6  490.27  5801.1  493.64  5939.6  494.04
#Mann=6,-1,0
  4412.7    0.16       0  4808.6    0.12       0  4992.1    0.07       0
  4998.1    0.12       0  5139.9    0.16       0  5476.2    0.05       0
Bank Sta=4846.5,5043
Exp/Cntr=0.3,0.1

Type RM Length L Ch R = 1,774,0,0,0
BEGIN DESCRIPTION:
UNT 101 in Running Cr Watershed 1.0
END DESCRIPTION:
XS GIS Cut Line= 4
      2917470.09      7057622.55      2917261.76      7058481.91
      2917478.78      7058768.37      2918441.17      7058586.29
#Sta/Elev= 30
  3884.7  477.64  3979.8  476.58  4154.7  472.42  4285.9  464.90  4319.4  462.29
  4422.3  458.98  4597.2  456.33  4651.4  456.96  4726.3  455.96  4986.8  456.41
  4995.1  455.83  4998.4  452.58  4998.9  451.78  5003.9  451.78  5004.4  452.58
  5009.7  452.61  5015.9  455.28  5023.7  456.22  5165.2  454.63  5394.0  455.96
  5531.6  461.74  5593.3  467.89  5600.9  468.73  5658.2  475.90  5710.5  484.43
  5753.7  487.47  5796.2  491.70  5887.2  495.48  6029.6  494.46  6107.8  495.46
#Mann=8,-1,0
  3884.7    0.16       0  4285.9    0.12       0  4998.4    0.07       0
  5004.4    0.12       0  5593.3    0.16       0  5600.9    0.12       0
  5753.7    0.16       0  5887.2    0.05       0
Bank Sta=4726.3,5394
Exp/Cntr=0.3,0.1

Chan Stop Cuts=-1