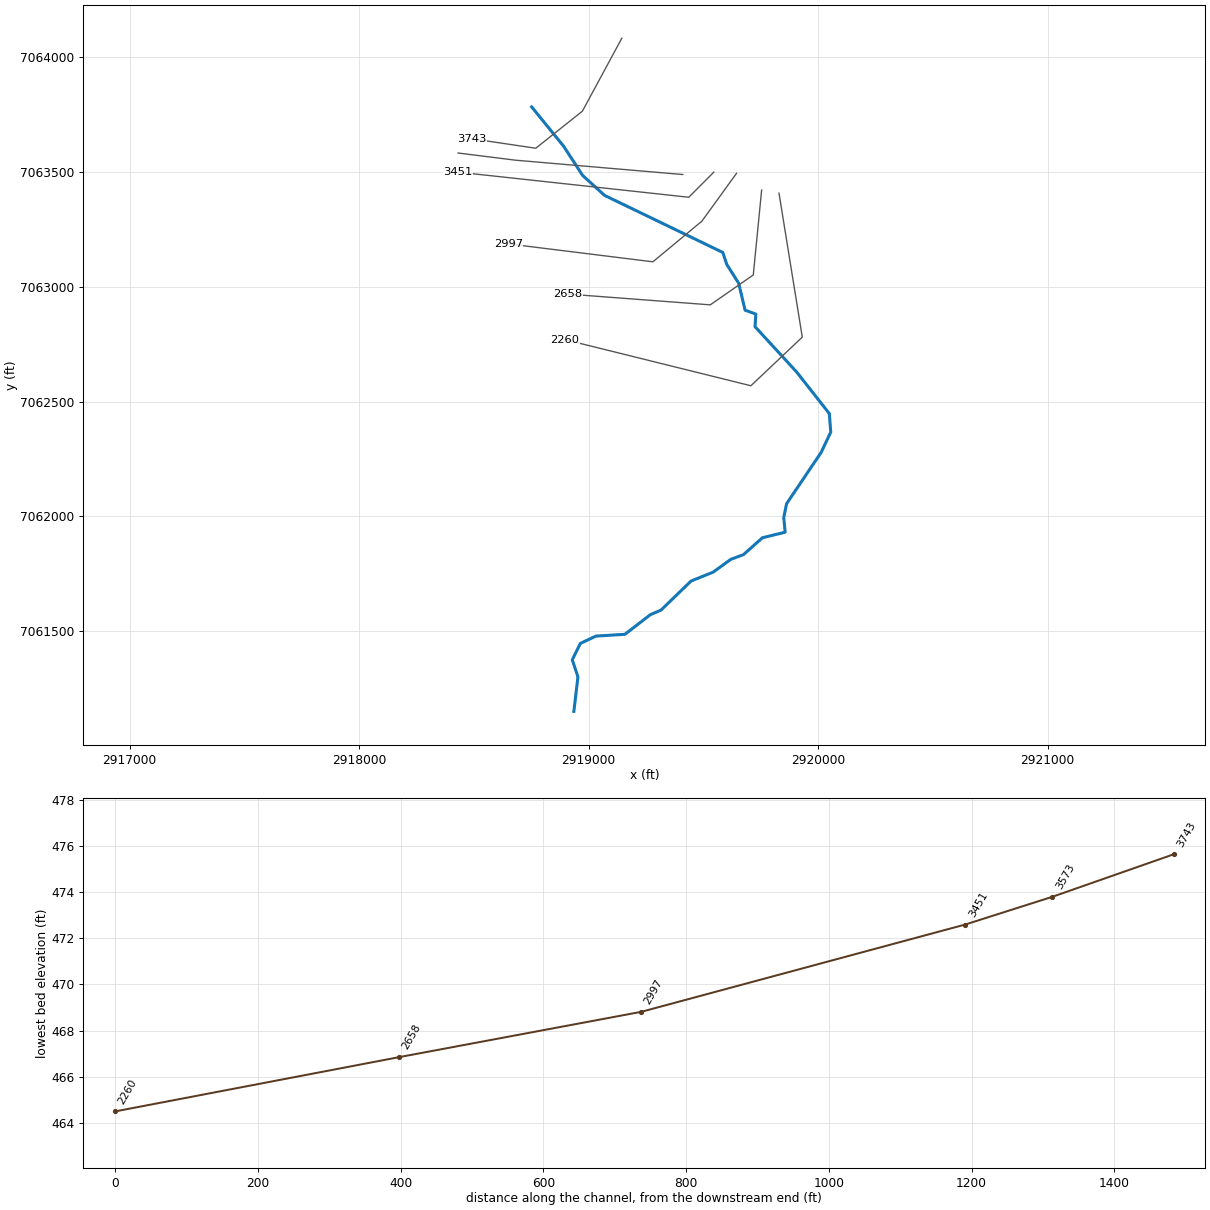
--- UNT 102 in Running Cr Watershed.prj (project) ---

Proj Title=UNT 102 in Running Cr Watershed Base Level Engineering
Current Plan=p01
Default Exp/Contr=0.3,0.1
English Units
Geom File=g01
Flow File=f01
Plan File=p01
BEGIN DESCRIPTION:
UNT 102 in Running Cr Watershed
END DESCRIPTION:

--- UNT 102 in Running Cr Watershed.p01 (plan) ---

Plan Title=Multiple Run
Short Identifier=Multiple
Geom File=g01
Flow File=f01
Subcritical Flow
K Sum by GR= 0
Std Step Tol= 0.01
Critical Tol= 0.01
Num of Std Step Trials= 20
Max Error Tol= 0.3
Flow Tol Ratio= 0.001
Split Flow NTrial= 30
Split Flow Tol= 0.02
Split Flow Ratio= 0.02
Log Output Level= 0
Friction Slope Method= 1
Unsteady Friction Slope Method= 2
Unsteady Bridges Friction Slope Method= 1
Parabolic Critical Depth
Global Vel Dist=  1 , 1 , 1
Global Log Level= 0
CheckData=True
Encroach Param= -1, 0, 0, 0
BEGIN DESCRIPTION:
Multiple Run
END DESCRIPTION:

--- UNT 102 in Running Cr Watershed.f01 (steady flow) ---

Flow Title=Multiple
Number of Profiles=7
Profile Names=10-year,25-year,50-year,1pct_min,100-year,1pct_plu,500-year
River Rch & RM= UNT 102 in Runni,Reach-1,3743
     438     569     671     394     786    1567    1072
Boundary for River Rch & Prof#=UNT 102 in Runni,Reach-1,1
Up Type=0
Dn Type=3
Dn Slope=0.005
Boundary for River Rch & Prof#=UNT 102 in Runni,Reach-1,2
Up Type=0
Dn Type=3
Dn Slope=0.005
Boundary for River Rch & Prof#=UNT 102 in Runni,Reach-1,3
Up Type=0
Dn Type=3
Dn Slope=0.005
Boundary for River Rch & Prof#=UNT 102 in Runni,Reach-1,4
Up Type=0
Dn Type=3
Dn Slope=0.005
Boundary for River Rch & Prof#=UNT 102 in Runni,Reach-1,5
Up Type=0
Dn Type=3
Dn Slope=0.005
Boundary for River Rch & Prof#=UNT 102 in Runni,Reach-1,6
Up Type=0
Dn Type=3
Dn Slope=0.005
Boundary for River Rch & Prof#=UNT 102 in Runni,Reach-1,7
Up Type=0
Dn Type=3
Dn Slope=0.005

--- UNT 102 in Running Cr Watershed.g01 (geometry) ---

Geom Title=Existing Conditions

River Reach=UNT 102 in Runni,Reach-1
Reach XY= 30
      2918751.73      7063783.82      2918890.42      7063613.28
      2918973.97      7063485.07      2919069.31      7063398.41
      2919584.58      7063149.89      2919601.49      7063098.55
      2919654.07      7063015.07      2919681.61      7062898.51
      2919728.69      7062881.27      2919725.10      7062826.42
      2919906.08      7062629.43      2920048.84      7062447.87
      2920055.05      7062367.18      2920013.15      7062278.73
      2919862.63      7062055.28      2919850.22      7061994.76
      2919856.43      7061931.14      2919757.44      7061906.96
      2919674.51      7061833.31      2919619.41      7061812.86
      2919542.39      7061757.05      2919446.48      7061718.56
      2919315.73      7061592.08      2919269.27      7061572.07
      2919157.98      7061486.32      2919031.44      7061478.49
      2918963.64      7061446.51      2918928.58      7061375.13
      2918953.26      7061300.78      2918935.59      7061150.71

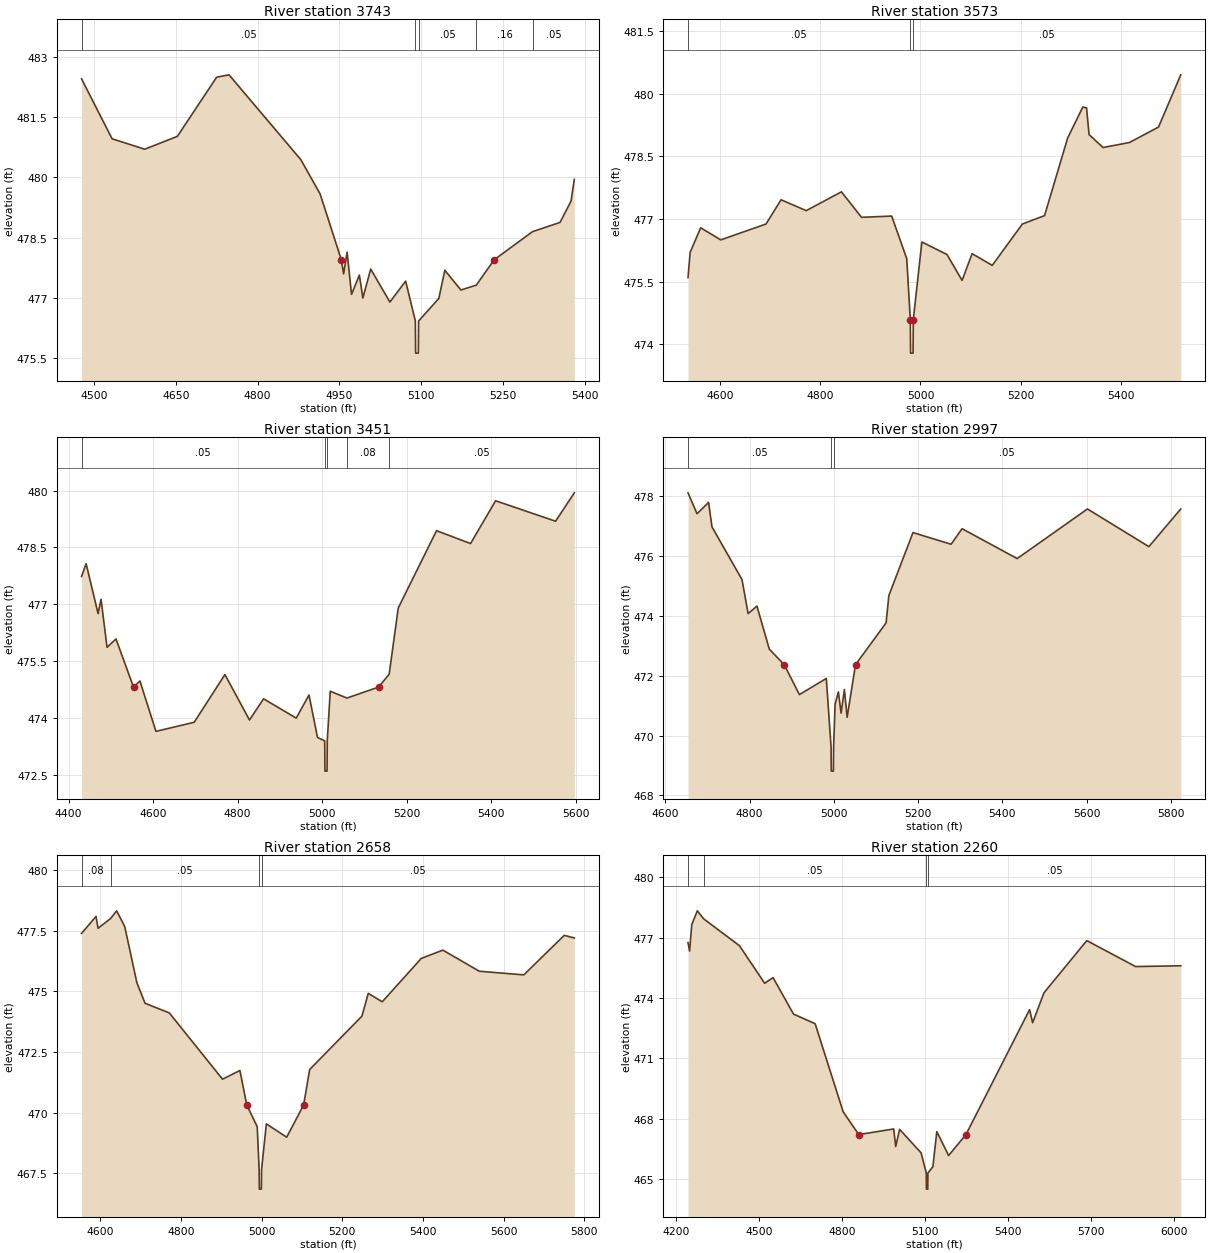
Type RM Length L Ch R = 1,3743,170,170,170
BEGIN DESCRIPTION:
UNT 102 in Running Cr Watershed 2.0
END DESCRIPTION:
XS GIS Cut Line= 4
      2919144.55      7064083.05      2918972.67      7063765.33
      2918769.54      7063603.87      2918489.11      7063645.42
#Sta/Elev= 30
  4477.0  482.45  4533.0  480.96  4592.9  480.70  4652.8  481.02  4724.9  482.49
  4747.6  482.55  4879.4  480.44  4914.7  479.59  4953.7  477.95  4957.9  477.60
  4964.3  478.14  4972.4  477.09  4986.8  477.57  4993.2  477.00  5007.6  477.72
  5042.8  476.90  5071.7  477.42  5089.5  476.43  5090.0  475.63  5095.0  475.63
  5095.5  476.43  5132.6  476.99  5143.6  477.69  5173.1  477.20  5201.3  477.32
  5234.1  477.95  5304.5  478.65  5355.0  478.88  5375.2  479.41  5381.2  479.95
#Mann=5,-1,0
  4477.0    0.05       0  5089.5    0.03       0  5095.5    0.05       0
  5201.3    0.16       0  5304.5    0.05       0
Bank Sta=4953.7,5234.1
Exp/Cntr=0.3,0.1

Type RM Length L Ch R = 1,3573,122,122,122
BEGIN DESCRIPTION:
Mapping XS fa5ab899
END DESCRIPTION:
XS GIS Cut Line= 3
      2919410.15      7063489.29      2918681.00      7063551.79
      2918430.97      7063583.04
#Sta/Elev= 30
  4535.9  475.60  4540.1  476.20  4561.1  476.79  4601.3  476.50  4691.6  476.88
  4721.7  477.46  4771.9  477.20  4842.2  477.65  4882.3  477.04  4942.5  477.07
  4972.6  476.05  4979.7  474.59  4980.2  473.79  4985.2  473.79  4985.7  474.59
  5002.8  476.45  5052.9  476.15  5083.1  475.53  5103.1  476.17  5143.3  475.89
  5203.5  476.88  5247.7  477.08  5293.9  478.94  5324.2  479.68  5331.6  479.66
  5336.6  479.02  5364.5  478.71  5417.2  478.83  5475.3  479.20  5519.7  480.45
#Mann=3,-1,0
  4535.9    0.05       0  4979.7    0.03       0  4985.7    0.05       0
Bank Sta=4979.7,4985.7
Exp/Cntr=0.3,0.1

Type RM Length L Ch R = 1,3451,454,454,454
BEGIN DESCRIPTION:
Mapping XS 6233b038
END DESCRIPTION:
XS GIS Cut Line= 3
      2919545.56      7063499.68      2919436.21      7063390.33
      2918430.99      7063499.71
#Sta/Elev= 30
  4430.7  477.73  4441.5  478.07  4469.8  476.75  4476.8  477.13  4491.0  475.86
  4512.2  476.08  4553.6  474.81  4568.8  474.97  4606.7  473.64  4697.2  473.88
  4769.9  475.14  4828.0  473.94  4861.4  474.50  4938.6  473.99  4968.8  474.60
  4988.9  473.48  5006.0  473.39  5006.5  472.59  5011.5  472.59  5012.0  473.39
  5019.1  474.70  5058.6  474.52  5133.6  474.81  5158.5  475.15  5180.0  476.90
  5270.6  478.94  5351.0  478.60  5410.3  479.73  5552.2  479.19  5596.5  479.94
#Mann=5,-1,0
  4430.7    0.05       0  5006.0    0.04       0  5012.0    0.05       0
  5058.6    0.08       0  5158.5    0.05       0
Bank Sta=4553.6,5133.6
Exp/Cntr=0.3,0.1

Type RM Length L Ch R = 1,2997,339,339,339
BEGIN DESCRIPTION:
Mapping XS 8a5aa9f0
END DESCRIPTION:
XS GIS Cut Line= 4
      2919644.55      7063494.51      2919493.50      7063286.17
      2919279.96      7063109.08      2918649.84      7063187.20
#Sta/Elev= 30
  4653.7  478.12  4675.1  477.42  4702.5  477.80  4710.6  476.98  4781.8  475.22
  4796.4  474.08  4817.3  474.33  4846.7  472.89  4882.1  472.37  4918.1  471.37
  4982.0  471.91  4993.3  469.61  4993.8  468.81  4998.8  468.81  4999.3  469.61
  5002.8  471.05  5010.6  471.46  5017.1  470.75  5024.9  471.54  5031.4  470.61
  5051.3  472.37  5123.9  473.77  5130.4  474.68  5187.7  476.79  5278.2  476.40
  5304.3  476.92  5435.0  475.92  5601.9  477.58  5747.7  476.32  5823.4  477.58
#Mann=3,-1,0
  4653.7    0.05       0  4993.3    0.03       0  4999.3    0.05       0
Bank Sta=4882.1,5051.3
Exp/Cntr=0.3,0.1

Type RM Length L Ch R = 1,2658,398,398,398
BEGIN DESCRIPTION:
Mapping XS 7ae297ec
END DESCRIPTION:
XS GIS Cut Line= 4
      2919753.92      7063421.61      2919717.46      7063051.79
      2919529.96      7062921.58      2918910.12      7062968.46
#Sta/Elev= 30
  4553.6  477.39  4589.5  478.09  4594.5  477.60  4625.4  478.00  4640.6  478.32
  4660.7  477.67  4690.7  475.36  4711.0  474.51  4771.3  474.11  4903.1  471.38
  4946.2  471.74  4963.1  470.32  4989.1  469.42  4993.8  467.65  4994.3  466.85
  4999.3  466.85  4999.8  467.65  5011.7  469.54  5062.1  468.99  5104.2  470.32
  5119.1  471.78  5248.7  473.98  5264.4  474.92  5298.9  474.57  5395.9  476.36
  5449.3  476.70  5539.6  475.83  5649.9  475.68  5750.2  477.31  5775.1  477.20
#Mann=4,-1,0
  4553.6    0.08       0  4625.4    0.05       0  4993.8    0.03       0
  4999.8    0.05       0
Bank Sta=4963.1,5104.2
Exp/Cntr=0.3,0.1

Type RM Length L Ch R = 1,2260,0,0,0
BEGIN DESCRIPTION:
UNT 102 in Running Cr Watershed 1.0
END DESCRIPTION:
XS GIS Cut Line= 4
      2919829.53      7063408.26      2919931.00      7062780.96
      2919707.04      7062569.15      2918895.61      7062770.28
#Sta/Elev= 30
  4243.6  476.75  4249.3  476.33  4257.0  477.64  4277.3  478.33  4300.3  477.93
  4429.2  476.60  4520.4  474.73  4550.8  475.01  4624.5  473.20  4702.7  472.72
  4804.0  468.34  4860.4  467.21  4986.4  467.49  4993.7  466.62  5007.9  467.47
  5085.5  466.30  5104.0  465.30  5104.5  464.50  5109.5  464.50  5110.0  465.30
  5128.0  465.61  5142.2  467.36  5184.7  466.17  5247.4  467.21  5477.3  473.42
  5488.2  472.77  5529.4  474.26  5683.9  476.85  5860.1  475.56  6023.3  475.60
#Mann=4,-1,0
  4243.6    0.08       0  4300.3    0.05       0  5104.0    0.03       0
  5110.0    0.05       0
Bank Sta=4860.4,5247.4
Exp/Cntr=0.3,0.1

Chan Stop Cuts=-1