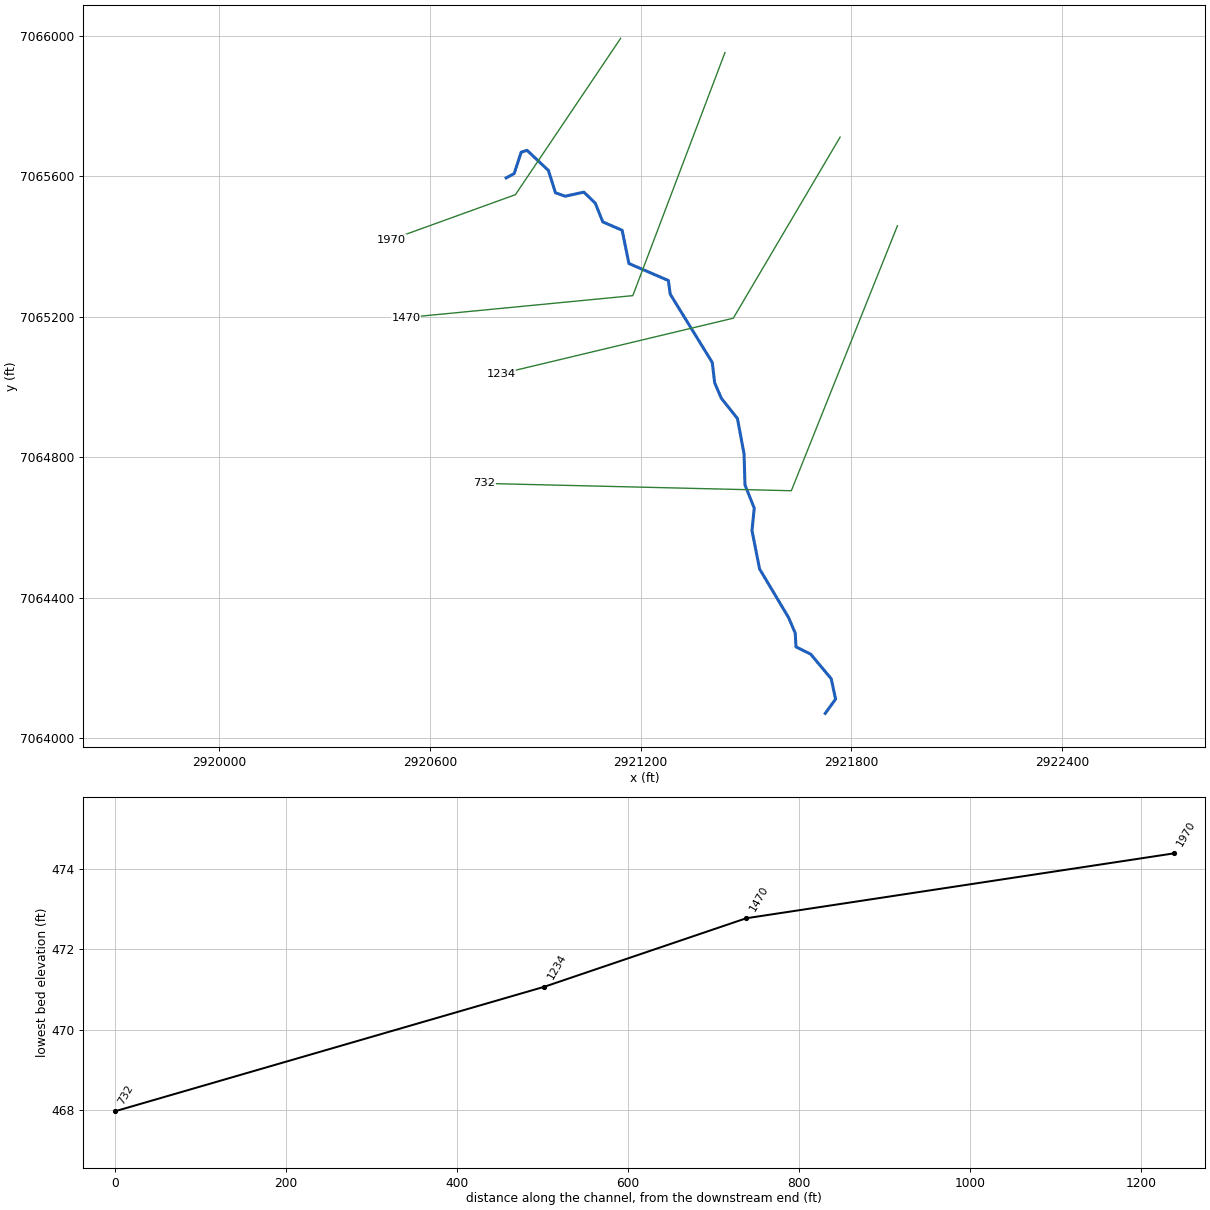
--- UNT 103 in Running Cr Watershed.prj (project) ---

Proj Title=UNT 103 in Running Cr Watershed Base Level Engineering
Current Plan=p01
Default Exp/Contr=0.3,0.1
English Units
Geom File=g01
Flow File=f01
Plan File=p01
BEGIN DESCRIPTION:
UNT 103 in Running Cr Watershed
END DESCRIPTION:

--- UNT 103 in Running Cr Watershed.p01 (plan) ---

Plan Title=Multiple Run
Short Identifier=Multiple
Geom File=g01
Flow File=f01
Subcritical Flow
K Sum by GR= 0
Std Step Tol= 0.01
Critical Tol= 0.01
Num of Std Step Trials= 20
Max Error Tol= 0.3
Flow Tol Ratio= 0.001
Split Flow NTrial= 30
Split Flow Tol= 0.02
Split Flow Ratio= 0.02
Log Output Level= 0
Friction Slope Method= 1
Unsteady Friction Slope Method= 2
Unsteady Bridges Friction Slope Method= 1
Parabolic Critical Depth
Global Vel Dist=  1 , 1 , 1
Global Log Level= 0
CheckData=True
Encroach Param= -1, 0, 0, 0
BEGIN DESCRIPTION:
Multiple Run
END DESCRIPTION:

--- UNT 103 in Running Cr Watershed.f01 (steady flow) ---

Flow Title=Multiple
Number of Profiles=7
Profile Names=10-year,25-year,50-year,1pct_min,100-year,1pct_plu,500-year
River Rch & RM= UNT 103 in Runni,Reach-1,1970
     620     823     986     586    1169    2333    1640
Boundary for River Rch & Prof#=UNT 103 in Runni,Reach-1,1
Up Type=0
Dn Type=3
Dn Slope=0.005
Boundary for River Rch & Prof#=UNT 103 in Runni,Reach-1,2
Up Type=0
Dn Type=3
Dn Slope=0.005
Boundary for River Rch & Prof#=UNT 103 in Runni,Reach-1,3
Up Type=0
Dn Type=3
Dn Slope=0.005
Boundary for River Rch & Prof#=UNT 103 in Runni,Reach-1,4
Up Type=0
Dn Type=3
Dn Slope=0.005
Boundary for River Rch & Prof#=UNT 103 in Runni,Reach-1,5
Up Type=0
Dn Type=3
Dn Slope=0.005
Boundary for River Rch & Prof#=UNT 103 in Runni,Reach-1,6
Up Type=0
Dn Type=3
Dn Slope=0.005
Boundary for River Rch & Prof#=UNT 103 in Runni,Reach-1,7
Up Type=0
Dn Type=3
Dn Slope=0.005

--- UNT 103 in Running Cr Watershed.g01 (geometry) ---

Geom Title=Existing Conditions

River Reach=UNT 103 in Runni,Reach-1
Reach XY= 30
      2920816.95      7065595.41      2920839.80      7065607.79
      2920859.79      7065668.68      2920876.45      7065674.05
      2920937.25      7065616.71      2920957.45      7065553.15
      2920985.09      7065543.31      2921038.20      7065554.99
      2921070.63      7065523.73      2921092.30      7065470.13
      2921147.31      7065446.36      2921166.50      7065351.72
      2921278.89      7065303.32      2921284.11      7065264.57
      2921403.87      7065069.90      2921410.78      7065011.75
      2921429.86      7064967.79      2921475.51      7064910.49
      2921494.32      7064810.19      2921497.08      7064721.30
      2921523.46      7064655.00      2921517.02      7064591.26
      2921538.66      7064481.98      2921621.20      7064343.48
      2921640.12      7064299.33      2921642.36      7064259.98
      2921684.15      7064239.38      2921742.59      7064169.40
      2921755.05      7064111.36      2921725.59      7064070.71

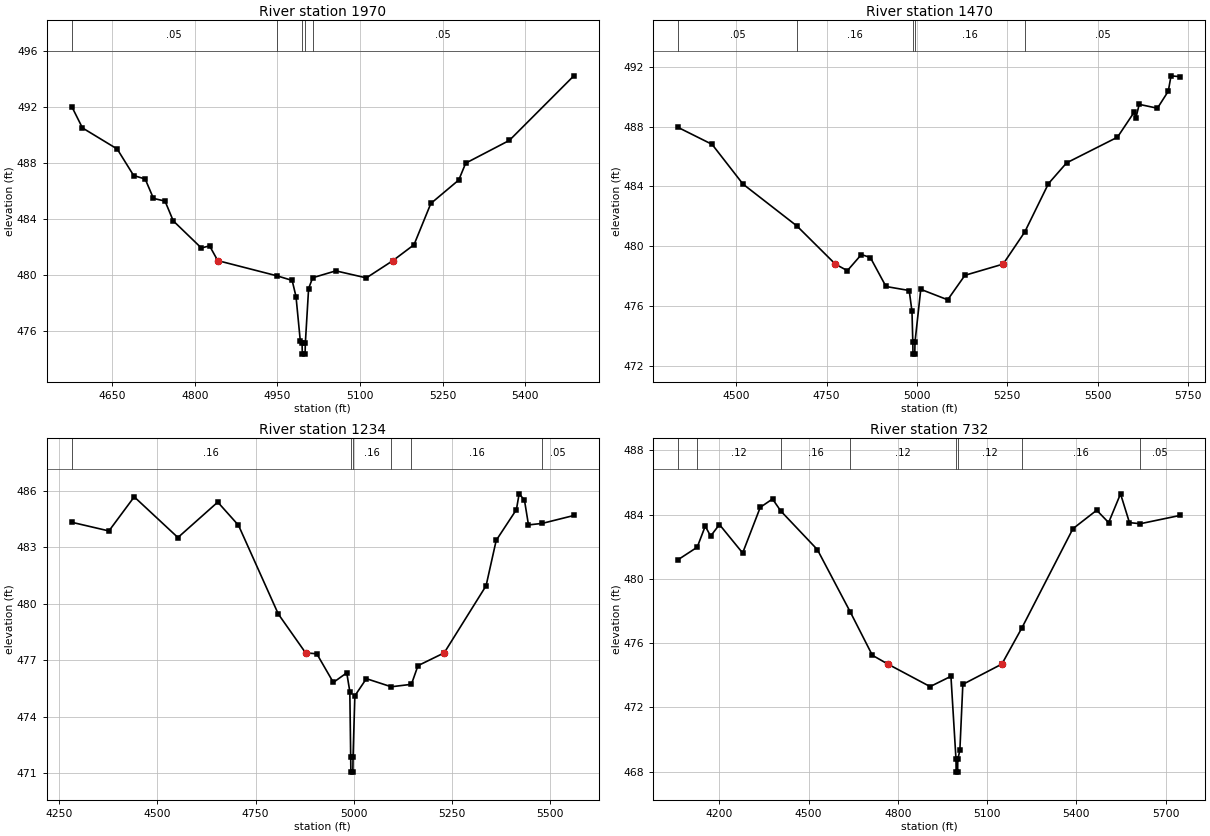
Type RM Length L Ch R = 1,1970,500,500,500
BEGIN DESCRIPTION:
UNT 103 in Running Cr Watershed 4.0
END DESCRIPTION:
XS GIS Cut Line= 3
      2921142.98      7065992.95      2920843.41      7065547.80
      2920490.18      7065419.99
#Sta/Elev= 30
  4576.4  492.01  4595.8  490.49  4658.9  488.99  4688.8  487.10  4709.8  486.85
  4724.8  485.47  4745.8  485.28  4760.8  483.87  4811.8  481.94  4826.8  482.09
  4841.6  481.04  4948.9  479.96  4976.8  479.63  4983.8  478.48  4991.7  475.28
  4994.8  475.18  4995.3  474.38  5000.3  474.38  5000.8  475.18  5006.7  479.05
  5014.1  479.82  5056.1  480.31  5111.6  479.81  5159.9  481.04  5198.2  482.17
  5228.8  485.11  5279.5  486.78  5292.1  487.98  5371.4  489.60  5488.6  494.20
#Mann=5,-1,0
  4576.4    0.05       0  4948.9    0.16       0  4994.8    0.07       0
  5000.8    0.16       0  5014.1    0.05       0
Bank Sta=4841.6,5159.9
Exp/Cntr=0.3,0.1

Type RM Length L Ch R = 1,1470,236,236,236
BEGIN DESCRIPTION:
UNT 103 in Running Cr Watershed 3.0
END DESCRIPTION:
XS GIS Cut Line= 3
      2921440.07      7065952.48      2921177.68      7065260.27
      2920531.87      7065197.77
#Sta/Elev= 30
  4339.6  487.95  4433.2  486.82  4518.7  484.16  4668.1  481.35  4774.2  478.80
  4807.5  478.36  4846.3  479.44  4871.1  479.24  4914.4  477.30  4978.6  477.03
  4986.3  475.64  4988.6  473.57  4989.1  472.77  4994.1  472.77  4994.6  473.57
  5010.6  477.11  5085.1  476.41  5132.8  478.05  5238.4  478.80  5298.3  480.95
  5363.9  484.19  5414.1  485.58  5554.8  487.30  5600.9  488.97  5605.9  488.60
  5615.0  489.50  5665.3  489.24  5695.4  490.38  5703.0  491.41  5728.7  491.35
#Mann=5,-1,0
  4339.6    0.05       0  4668.1    0.16       0  4988.6    0.07       0
  4994.6    0.16       0  5298.3    0.05       0
Bank Sta=4774.2,5238.4
Exp/Cntr=0.3,0.1

Type RM Length L Ch R = 1,1234,502,502,502
BEGIN DESCRIPTION:
UNT 103 in Running Cr Watershed 2.0
END DESCRIPTION:
XS GIS Cut Line= 3
      2921767.97      7065711.68      2921463.79      7065196.03
      2920802.68      7065038.05
#Sta/Elev= 30
  4282.0  484.33  4376.6  483.87  4441.0  485.68  4552.3  483.52  4653.7  485.40
  4706.5  484.17  4807.9  479.46  4877.4  477.40  4905.9  477.35  4948.0  475.83
  4982.2  476.34  4990.0  475.34  4992.2  471.87  4992.7  471.07  4997.7  471.07
  4998.2  471.87  5002.8  475.12  5032.1  476.03  5095.5  475.60  5146.8  475.73
  5163.5  476.72  5230.3  477.40  5336.9  480.96  5362.7  483.37  5414.1  485.00
  5421.1  485.84  5434.6  485.51  5444.9  484.19  5479.6  484.27  5560.4  484.69
#Mann=6,-1,0
  4282.0    0.16       0  4992.2    0.07       0  4998.2    0.16       0
  5095.5    0.12       0  5146.8    0.16       0  5479.6    0.05       0
Bank Sta=4877.4,5230.3
Exp/Cntr=0.3,0.1

Type RM Length L Ch R = 1,732,0,0,0
BEGIN DESCRIPTION:
UNT 103 in Running Cr Watershed 1.0
END DESCRIPTION:
XS GIS Cut Line= 3
      2921931.20      7065459.29      2921629.06      7064704.71
      2920754.03      7064725.55
#Sta/Elev= 30
  4061.5  481.20  4125.3  481.97  4152.3  483.28  4170.4  482.66  4200.0  483.38
  4278.1  481.61  4337.3  484.45  4378.5  484.97  4406.4  484.22  4529.3  481.82
  4640.0  477.94  4714.1  475.25  4766.3  474.70  4908.4  473.30  4978.4  473.94
  4995.4  468.78  4995.9  467.98  5000.9  467.98  5001.4  468.78  5008.4  469.33
  5018.4  473.44  5149.6  474.70  5217.5  476.97  5388.5  483.12  5468.5  484.27
  5508.6  483.50  5548.6  485.29  5578.6  483.50  5614.9  483.43  5749.6  483.95
#Mann=8,-1,0
  4061.5    0.16       0  4125.3    0.12       0  4406.4    0.16       0
  4640.0    0.12       0  4995.4    0.07       0  5001.4    0.12       0
  5217.5    0.16       0  5614.9    0.05       0
Bank Sta=4766.3,5149.6
Exp/Cntr=0.3,0.1

Chan Stop Cuts=-1