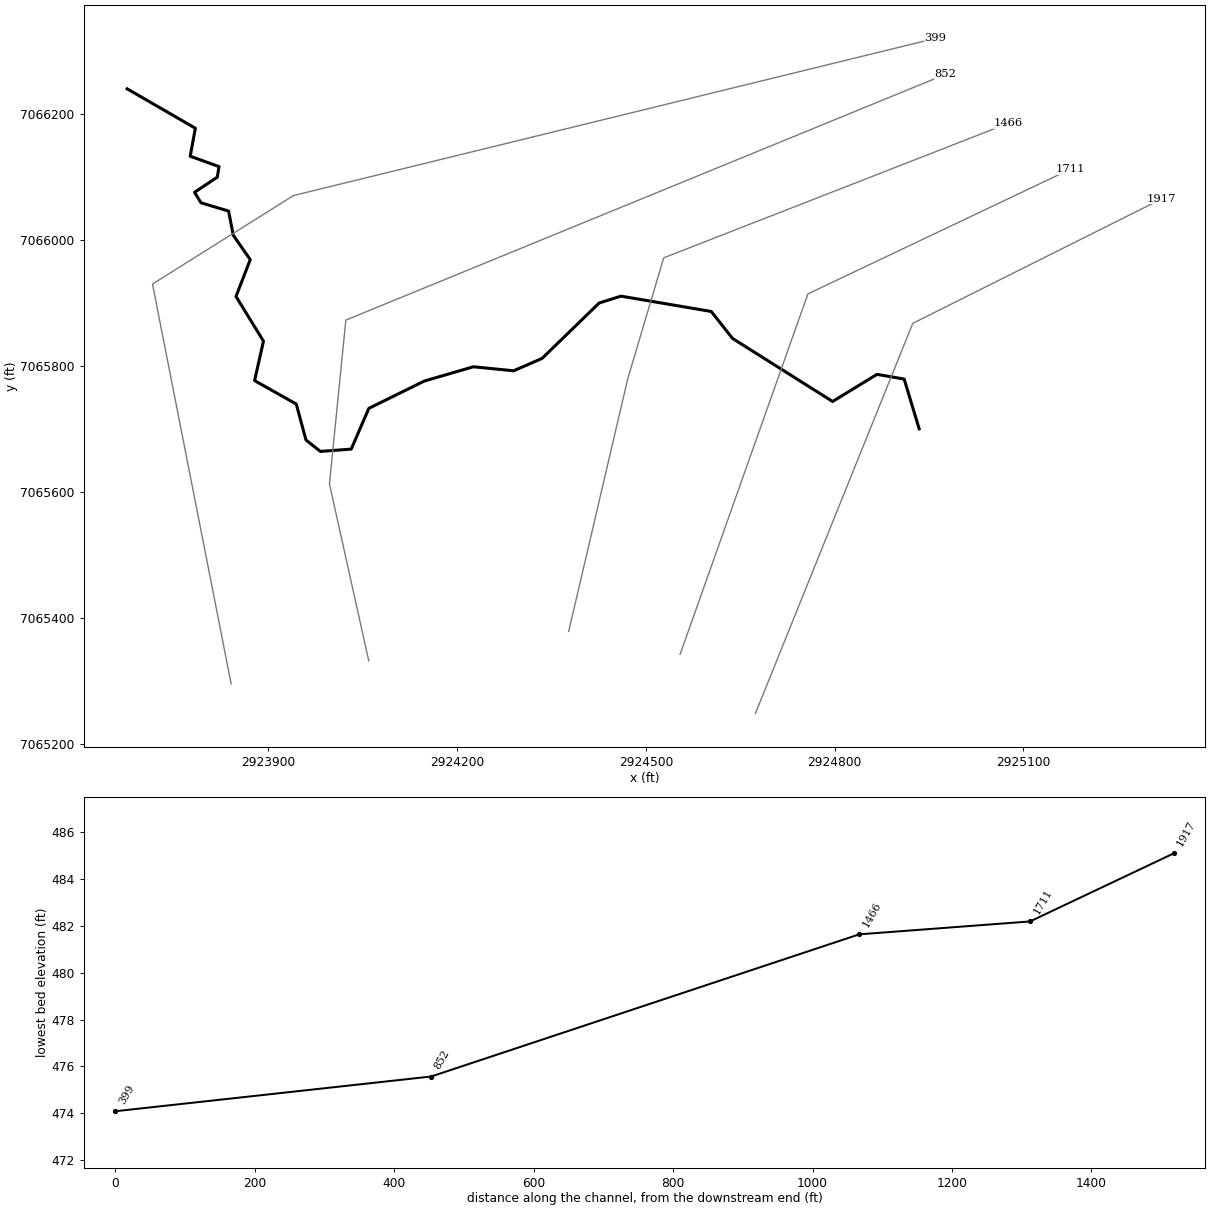
--- UNT 104 in Running Cr Watershed.prj (project) ---

Proj Title=UNT 104 in Running Cr Watershed Base Level Engineering
Current Plan=p01
Default Exp/Contr=0.3,0.1
English Units
Geom File=g01
Flow File=f01
Plan File=p01
BEGIN DESCRIPTION:
UNT 104 in Running Cr Watershed
END DESCRIPTION:

--- UNT 104 in Running Cr Watershed.p01 (plan) ---

Plan Title=Multiple Run
Short Identifier=Multiple
Geom File=g01
Flow File=f01
Subcritical Flow
K Sum by GR= 0
Std Step Tol= 0.01
Critical Tol= 0.01
Num of Std Step Trials= 20
Max Error Tol= 0.3
Flow Tol Ratio= 0.001
Split Flow NTrial= 30
Split Flow Tol= 0.02
Split Flow Ratio= 0.02
Log Output Level= 0
Friction Slope Method= 1
Unsteady Friction Slope Method= 2
Unsteady Bridges Friction Slope Method= 1
Parabolic Critical Depth
Global Vel Dist=  1 , 1 , 1
Global Log Level= 0
CheckData=True
Encroach Param= -1, 0, 0, 0
BEGIN DESCRIPTION:
Multiple Run
END DESCRIPTION:

--- UNT 104 in Running Cr Watershed.f01 (steady flow) ---

Flow Title=Multiple
Number of Profiles=7
Profile Names=10-year,25-year,50-year,1pct_min,100-year,1pct_plu,500-year
River Rch & RM= UNT 104 in Runni,Reach-1,1917
     583     773     924     549    1095    2185    1533
Boundary for River Rch & Prof#=UNT 104 in Runni,Reach-1,1
Up Type=0
Dn Type=3
Dn Slope=0.005
Boundary for River Rch & Prof#=UNT 104 in Runni,Reach-1,2
Up Type=0
Dn Type=3
Dn Slope=0.005
Boundary for River Rch & Prof#=UNT 104 in Runni,Reach-1,3
Up Type=0
Dn Type=3
Dn Slope=0.005
Boundary for River Rch & Prof#=UNT 104 in Runni,Reach-1,4
Up Type=0
Dn Type=3
Dn Slope=0.005
Boundary for River Rch & Prof#=UNT 104 in Runni,Reach-1,5
Up Type=0
Dn Type=3
Dn Slope=0.005
Boundary for River Rch & Prof#=UNT 104 in Runni,Reach-1,6
Up Type=0
Dn Type=3
Dn Slope=0.005
Boundary for River Rch & Prof#=UNT 104 in Runni,Reach-1,7
Up Type=0
Dn Type=3
Dn Slope=0.005

--- UNT 104 in Running Cr Watershed.g01 (geometry) ---

Geom Title=Existing Conditions

River Reach=UNT 104 in Runni,Reach-1
Reach XY= 30
      2924934.40      7065700.28      2924910.54      7065779.42
      2924867.35      7065786.90      2924796.81      7065743.78
      2924637.74      7065843.99      2924603.93      7065886.83
      2924460.49      7065911.20      2924425.75      7065900.29
      2924334.98      7065812.17      2924289.79      7065792.56
      2924225.93      7065798.95      2924148.02      7065776.33
      2924059.71      7065732.84      2924031.70      7065668.10
      2923982.70      7065664.42      2923959.82      7065682.51
      2923944.36      7065739.69      2923878.13      7065776.99
      2923892.24      7065839.71      2923848.56      7065910.67
      2923871.23      7065969.26      2923844.26      7066007.94
      2923836.79      7066046.40      2923792.98      7066059.57
      2923782.71      7066076.27      2923818.90      7066100.38
      2923821.57      7066117.10      2923775.81      7066133.59
      2923783.97      7066178.09      2923675.59      7066240.71

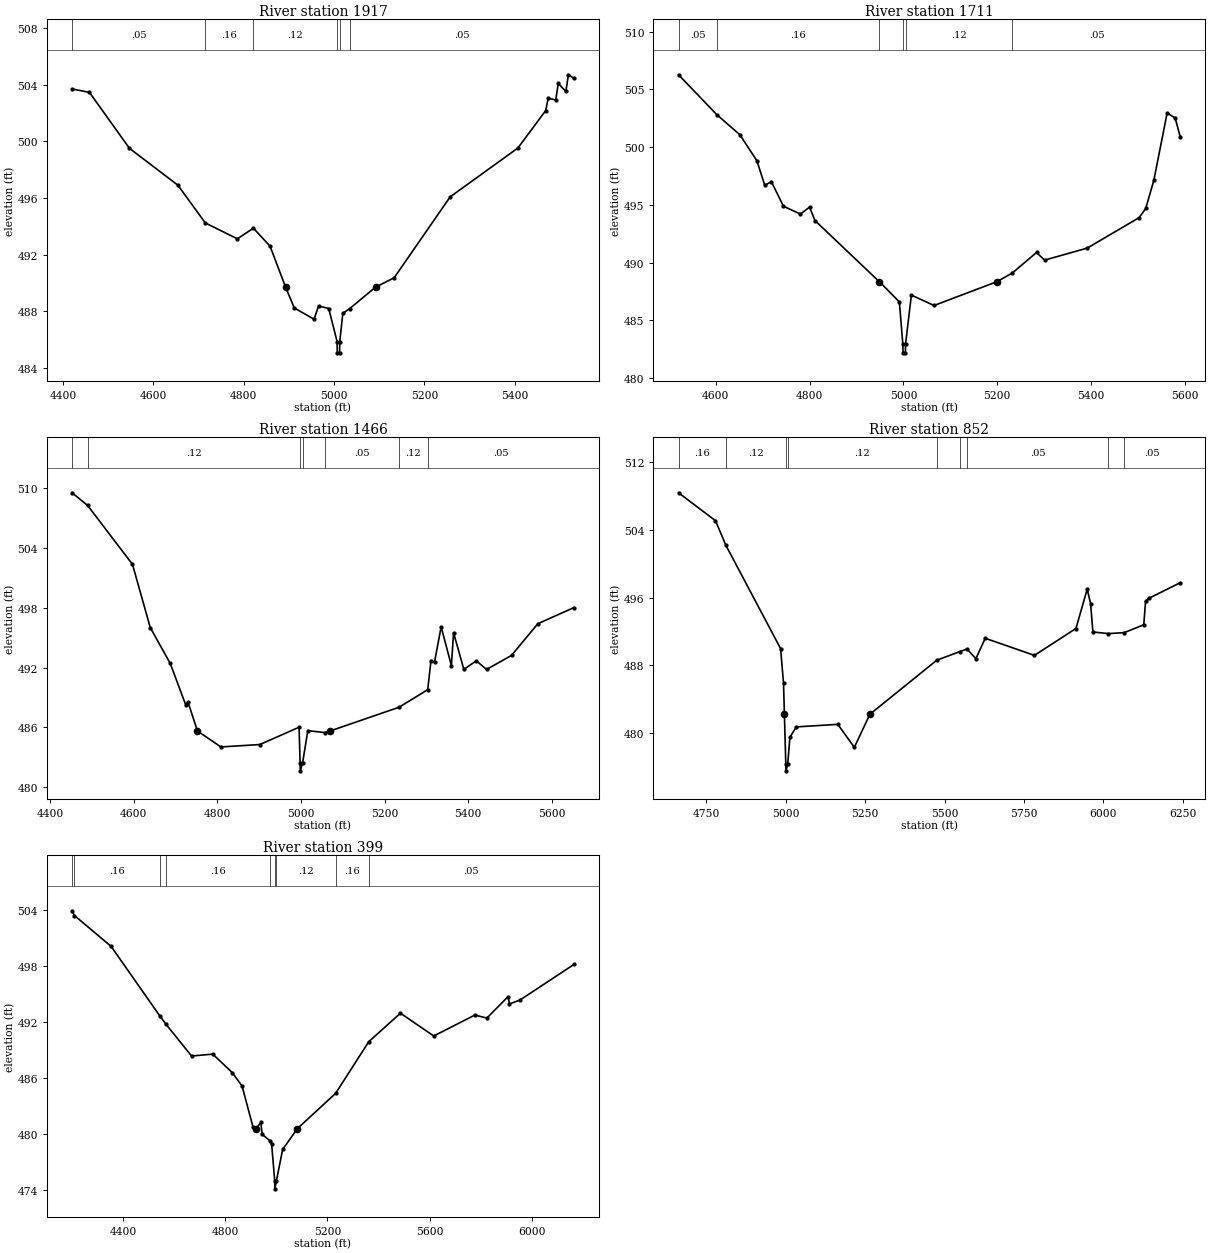
Type RM Length L Ch R = 1,1917,206,206,206
BEGIN DESCRIPTION:
UNT 104 in Running Cr Watershed 2.0
END DESCRIPTION:
XS GIS Cut Line= 3
      2924674.19      7065248.07      2924924.20      7065867.91
      2925320.02      7066065.82
#Sta/Elev= 30
  4419.9  503.71  4458.3  503.47  4546.9  499.52  4654.3  496.91  4714.9  494.25
  4785.8  493.13  4821.4  493.88  4858.2  492.61  4892.6  489.72  4911.9  488.25
  4955.7  487.45  4965.6  488.39  4988.1  488.21  5006.6  485.88  5007.1  485.08
  5012.1  485.08  5012.6  485.88  5019.3  487.87  5034.4  488.20  5091.9  489.72
  5133.0  490.38  5256.9  496.09  5406.9  499.54  5468.4  502.18  5474.0  503.06
  5490.7  502.93  5496.3  504.10  5513.1  503.53  5518.7  504.71  5530.8  504.47
#Mann=6,-1,0
  4419.9    0.05       0  4714.9    0.16       0  4821.4    0.12       0
  5006.6    0.07       0  5012.6    0.12       0  5034.4    0.05       0
Bank Sta=4892.6,5091.9
Exp/Cntr=0.3,0.1

Type RM Length L Ch R = 1,1711,245,245,245
BEGIN DESCRIPTION:
Mapping XS 5c2267cf
END DESCRIPTION:
XS GIS Cut Line= 3
      2924554.42      7065341.88      2924757.54      7065914.78
      2925174.18      7066112.69
#Sta/Elev= 30
  4520.9  506.26  4602.9  502.79  4651.5  501.07  4687.9  498.81  4704.6  496.69
  4718.8  497.00  4744.4  494.87  4780.6  494.20  4800.1  494.80  4811.5  493.64
  4947.9  488.37  4948.7  488.35  4991.4  486.59  4998.7  482.98  4999.2  482.18
  5004.2  482.18  5004.7  482.98  5017.0  487.18  5065.3  486.28  5199.8  488.35
  5232.3  489.10  5283.6  490.87  5300.8  490.21  5391.6  491.25  5502.3  493.89
  5516.4  494.69  5533.6  497.13  5561.8  502.93  5579.0  502.53  5590.0  500.85
#Mann=6,-1,0
  4520.9    0.05       0  4602.9    0.16       0  4947.9    0.12       0
  4998.7    0.07       0  5004.7    0.12       0  5232.3    0.05       0
Bank Sta=4948.7,5199.8
Exp/Cntr=0.3,0.1

Type RM Length L Ch R = 1,1466,614,614,614
BEGIN DESCRIPTION:
Mapping XS 3f0a1719
END DESCRIPTION:
XS GIS Cut Line= 4
      2924377.33      7065378.32      2924471.08      7065779.37
      2924528.37      7065972.07      2925075.25      7066185.62
#Sta/Elev= 30
  4452.8  509.55  4490.0  508.28  4597.3  502.36  4639.8  496.01  4687.5  492.42
  4724.8  488.23  4730.0  488.55  4752.6  485.63  4808.8  484.03  4901.8  484.27
  4995.7  486.01  4998.1  482.43  4998.6  481.63  5004.1  482.43  5016.6  485.67
  5056.8  485.47  5069.7  485.63  5234.5  488.01  5303.3  489.78  5310.9  492.62
  5319.7  492.58  5335.4  496.09  5359.9  492.20  5365.2  495.49  5389.7  491.81
  5419.6  492.68  5444.0  491.81  5503.7  493.22  5566.6  496.40  5652.8  498.02
#Mann=7,-1,0
  4452.8    0.16       0  4490.0    0.12       0  4998.1    0.07       0
  5004.1    0.12       0  5056.8    0.05       0  5234.5    0.12       0
  5303.3    0.05       0
Bank Sta=4752.6,5069.7
Exp/Cntr=0.3,0.1

Type RM Length L Ch R = 1,852,453,453,453
BEGIN DESCRIPTION:
Mapping XS 21c993fc
END DESCRIPTION:
XS GIS Cut Line= 4
      2924059.62      7065331.44      2923997.12      7065612.70
      2924023.16      7065873.12      2924976.29      7066263.74
#Sta/Elev= 30
  4662.5  508.35  4778.8  505.06  4811.6  502.16  4983.8  489.98  4993.1  485.90
  4995.8  482.24  5000.2  476.37  5000.7  475.57  5006.2  476.37  5013.2  479.53
  5033.3  480.75  5164.0  481.05  5216.0  478.34  5265.0  482.24  5475.5  488.61
  5547.7  489.62  5570.6  489.93  5598.8  488.80  5628.2  491.20  5783.0  489.18
  5913.7  492.35  5949.2  496.98  5960.0  495.27  5967.1  491.94  6016.0  491.75
  6065.6  491.86  6127.3  492.79  6132.9  495.55  6143.7  495.92  6242.4  497.75
#Mann=9,-1,0
  4662.5    0.16       0  4811.6    0.12       0  5000.2    0.07       0
  5006.2    0.12       0  5475.5    0.16       0  5547.7    0.12       0
  5570.6    0.05       0  6016.0    0.12       0  6065.6    0.05       0
Bank Sta=4995.8,5265
Exp/Cntr=0.3,0.1

Type RM Length L Ch R = 1,399,0,0,0
BEGIN DESCRIPTION:
UNT 104 in Running Cr Watershed 1.0
END DESCRIPTION:
XS GIS Cut Line= 4
      2923840.88      7065294.94      2923715.87      7065930.41
      2923939.83      7066071.03      2924960.38      7066320.96
#Sta/Elev= 30
  4201.0  503.96  4210.3  503.45  4353.9  500.13  4544.6  492.65  4569.1  491.75
  4668.3  488.36  4751.4  488.56  4827.5  486.58  4866.0  485.13  4908.4  480.77
  4921.6  480.57  4939.0  481.23  4944.9  479.94  4973.7  479.28  4981.5  478.95
  4993.8  474.89  4994.3  474.09  4999.8  474.89  5024.7  478.32  5082.7  480.57
  5232.0  484.35  5361.3  489.89  5485.5  492.96  5615.5  490.51  5776.8  492.76
  5823.5  492.43  5906.8  494.75  5911.9  493.95  5953.5  494.38  6163.8  498.19
#Mann=9,-1,0
  4201.0    0.12       0  4210.3    0.16       0  4544.6    0.12       0
  4569.1    0.16       0  4973.7    0.12       0  4993.8    0.07       0
  4999.8    0.12       0  5232.0    0.16       0  5361.3    0.05       0
Bank Sta=4921.6,5082.7
Exp/Cntr=0.3,0.1

Chan Stop Cuts=-1