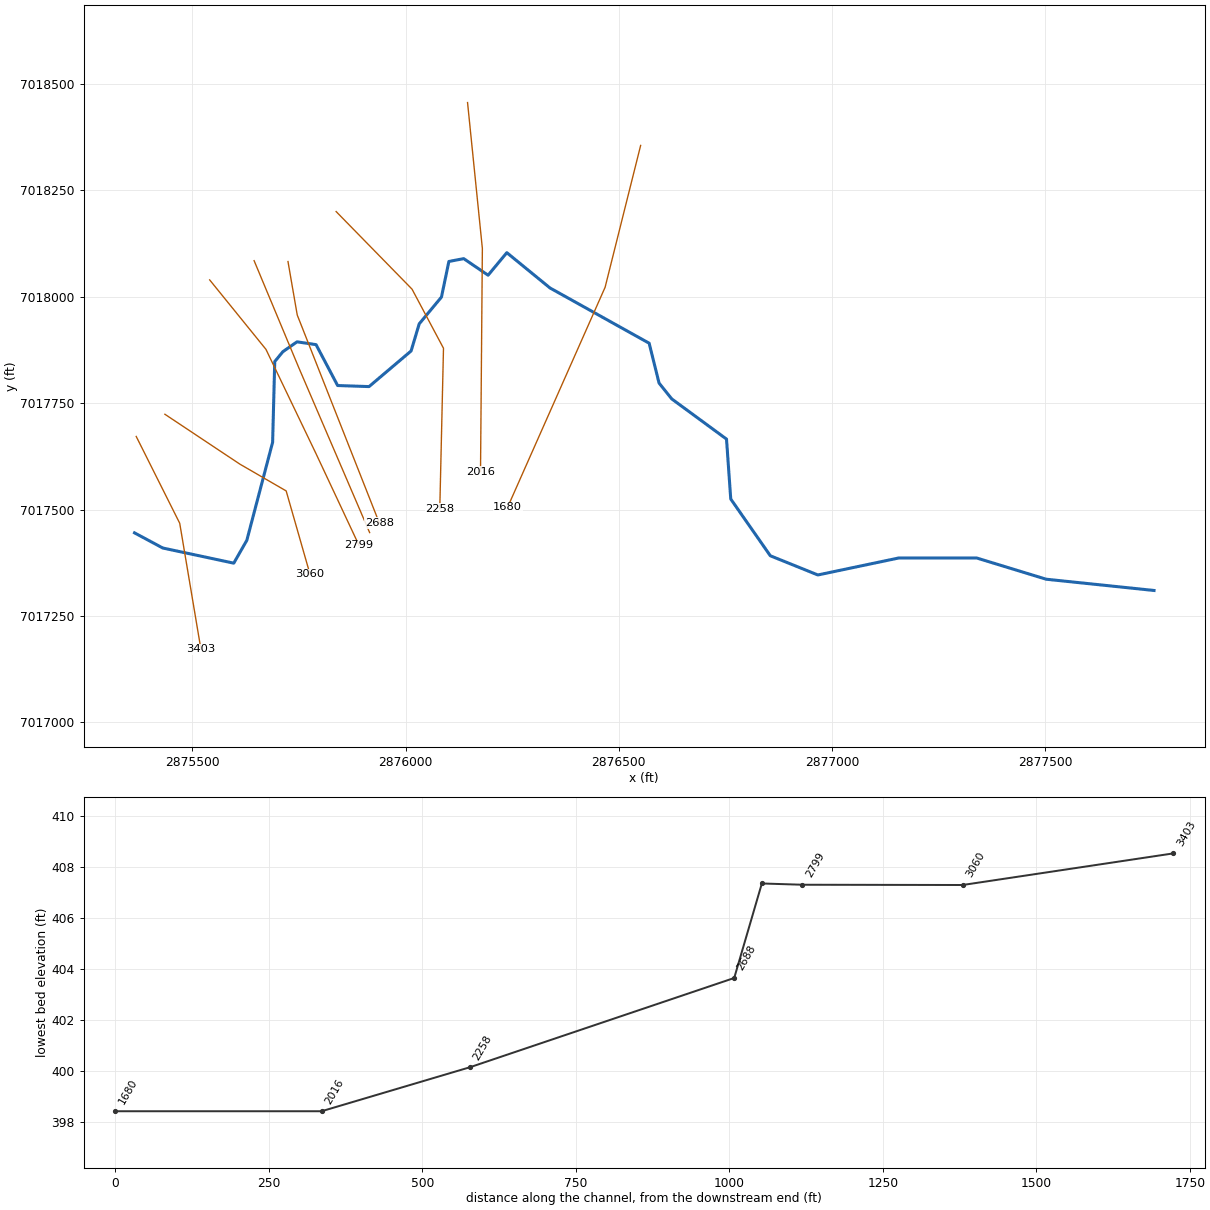
--- UNT 105 in Running Cr Watershed.prj (project) ---

Proj Title=UNT 105 in Running Cr Watershed Base Level Engineering
Current Plan=p01
Default Exp/Contr=0.3,0.1
English Units
Geom File=g01
Flow File=f01
Plan File=p01
BEGIN DESCRIPTION:
UNT 105 in Running Cr Watershed
END DESCRIPTION:

--- UNT 105 in Running Cr Watershed.p01 (plan) ---

Plan Title=Multiple Run
Short Identifier=Multiple
Geom File=g01
Flow File=f01
Subcritical Flow
K Sum by GR= 0
Std Step Tol= 0.01
Critical Tol= 0.01
Num of Std Step Trials= 20
Max Error Tol= 0.3
Flow Tol Ratio= 0.001
Split Flow NTrial= 30
Split Flow Tol= 0.02
Split Flow Ratio= 0.02
Log Output Level= 0
Friction Slope Method= 1
Unsteady Friction Slope Method= 2
Unsteady Bridges Friction Slope Method= 1
Parabolic Critical Depth
Global Vel Dist=  1 , 1 , 1
Global Log Level= 0
CheckData=True
Encroach Param= -1, 0, 0, 0
BEGIN DESCRIPTION:
Multiple Run
END DESCRIPTION:

--- UNT 105 in Running Cr Watershed.f01 (steady flow) ---

Flow Title=Multiple
Number of Profiles=7
Profile Names=10-year,25-year,50-year,1pct_min,100-year,1pct_plu,500-year
River Rch & RM= UNT 105 in Runni,Reach-1,3403
     160     194     220     124     248     495     314
Boundary for River Rch & Prof#=UNT 105 in Runni,Reach-1,1
Up Type=0
Dn Type=3
Dn Slope=0.005
Boundary for River Rch & Prof#=UNT 105 in Runni,Reach-1,2
Up Type=0
Dn Type=3
Dn Slope=0.005
Boundary for River Rch & Prof#=UNT 105 in Runni,Reach-1,3
Up Type=0
Dn Type=3
Dn Slope=0.005
Boundary for River Rch & Prof#=UNT 105 in Runni,Reach-1,4
Up Type=0
Dn Type=3
Dn Slope=0.005
Boundary for River Rch & Prof#=UNT 105 in Runni,Reach-1,5
Up Type=0
Dn Type=3
Dn Slope=0.005
Boundary for River Rch & Prof#=UNT 105 in Runni,Reach-1,6
Up Type=0
Dn Type=3
Dn Slope=0.005
Boundary for River Rch & Prof#=UNT 105 in Runni,Reach-1,7
Up Type=0
Dn Type=3
Dn Slope=0.005

--- UNT 105 in Running Cr Watershed.g01 (geometry) ---

Geom Title=Existing Conditions

River Reach=UNT 105 in Runni,Reach-1
Reach XY= 30
      2875364.62      7017445.21      2875430.87      7017409.60
      2875597.32      7017373.99      2875627.96      7017427.82
      2875688.41      7017658.04      2875693.38      7017847.68
      2875712.43      7017870.87      2875745.55      7017894.05
      2875790.27      7017887.43      2875840.79      7017791.37
      2875914.49      7017788.88      2876013.04      7017872.52
      2876032.08      7017936.29      2876084.26      7017999.22
      2876101.65      7018082.86      2876136.43      7018089.49
      2876193.57      7018050.57      2876237.46      7018103.57
      2876338.49      7018020.76      2876571.19      7017890.74
      2876594.38      7017797.16      2876624.19      7017759.90
      2876752.55      7017665.49      2876762.49      7017524.71
      2876855.24      7017391.38      2876966.74      7017346.25
      2877156.23      7017386.14      2877339.06      7017386.14
      2877501.96      7017336.28      2877754.80      7017309.82

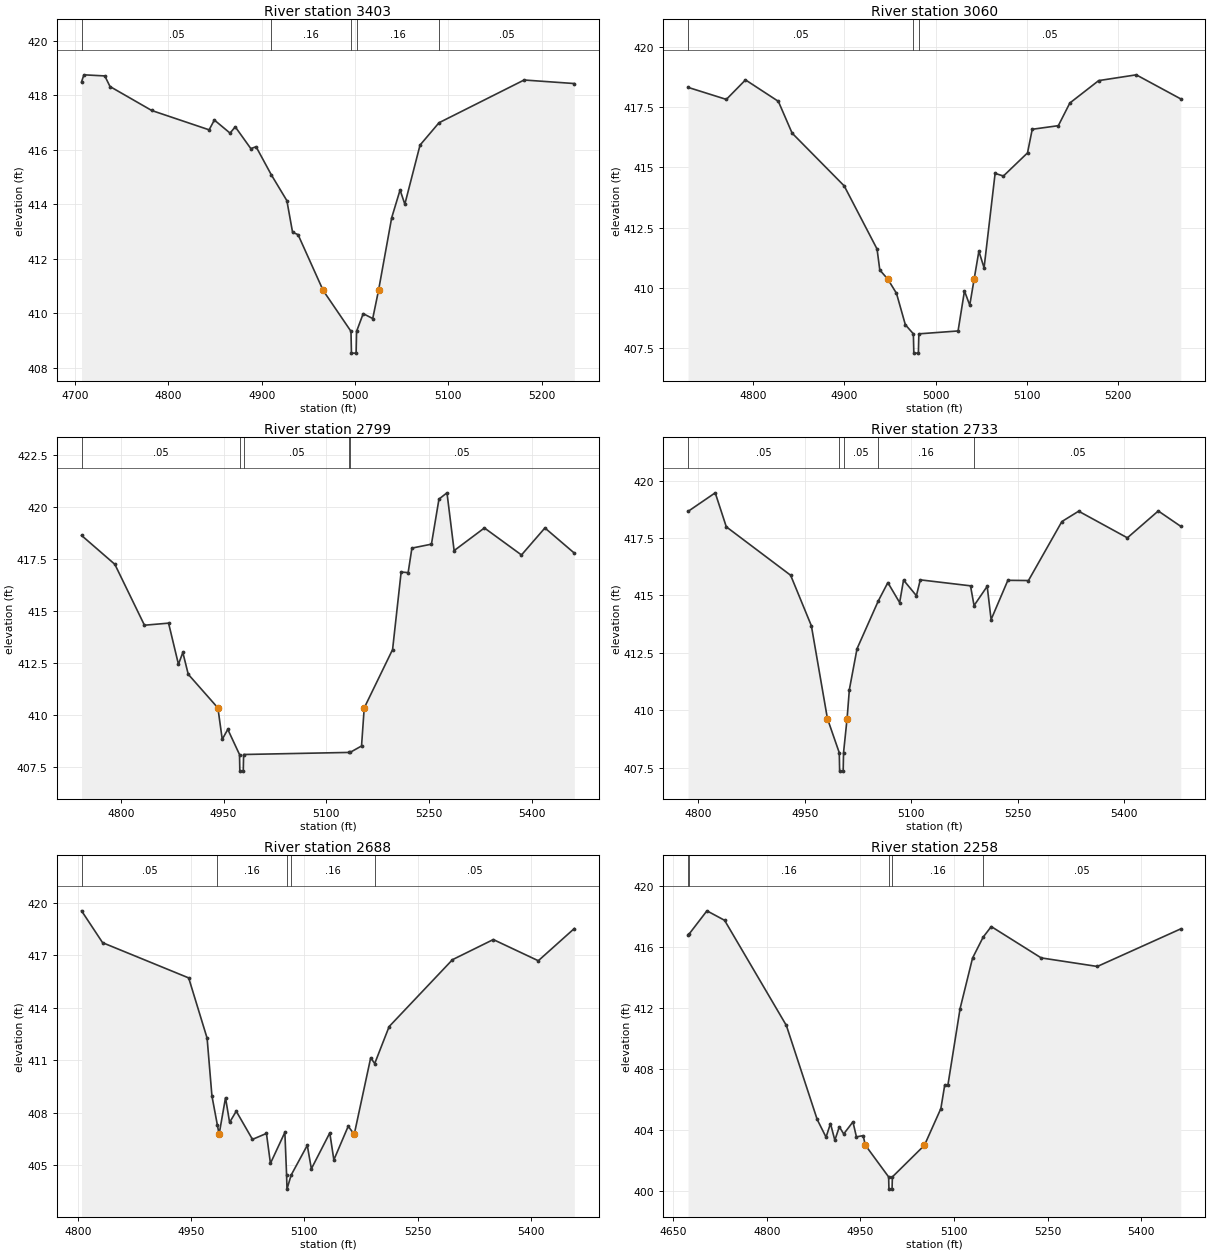
Type RM Length L Ch R = 1,3403,343,343,343
BEGIN DESCRIPTION:
UNT 105 in Running Cr Watershed 2.0
END DESCRIPTION:
XS GIS Cut Line= 3
      2875368.60      7017671.75      2875470.60      7017467.77
      2875520.26      7017171.97
#Sta/Elev= 30
  4707.0  418.49  4709.5  418.75  4731.9  418.71  4737.5  418.32  4782.2  417.44
  4843.7  416.73  4849.3  417.09  4866.1  416.61  4871.7  416.84  4888.4  416.04
  4894.0  416.11  4910.3  415.08  4927.0  414.13  4933.1  412.97  4939.0  412.88
  4965.9  410.83  4995.7  409.33  4996.2  408.53  5001.2  408.53  5001.7  409.33
  5008.8  409.98  5019.0  409.80  5025.2  410.83  5039.3  413.50  5048.3  414.52
  5053.4  414.00  5069.7  416.17  5090.0  416.99  5181.2  418.56  5235.0  418.43
#Mann=5,-1,0
  4707.0    0.05       0  4910.3    0.16       0  4995.7    0.07       0
  5001.7    0.16       0  5090.0    0.05       0
Bank Sta=4965.9,5025.2
Exp/Cntr=0.3,0.1

Type RM Length L Ch R = 1,3060,261,261,261
BEGIN DESCRIPTION:
Mapping XS ff7e93f3
END DESCRIPTION:
XS GIS Cut Line= 4
      2875435.91      7017723.82      2875611.66      7017606.66
      2875720.16      7017543.72      2875776.05      7017348.11
#Sta/Elev= 30
  4728.7  418.32  4770.7  417.82  4791.7  418.63  4827.7  417.74  4842.8  416.42
  4899.9  414.23  4935.9  411.61  4938.9  410.74  4947.7  410.36  4957.2  409.77
  4966.9  408.47  4975.7  408.09  4976.2  407.29  4981.2  407.29  4981.7  408.09
  5024.7  408.21  5031.7  409.87  5037.5  409.28  5042.3  410.36  5047.5  411.52
  5053.2  410.83  5065.3  414.75  5074.4  414.64  5100.8  415.60  5106.0  416.58
  5134.6  416.73  5147.2  417.67  5178.8  418.60  5220.0  418.84  5268.8  417.84
#Mann=3,-1,0
  4728.7    0.05       0  4975.7    0.03       0  4981.7    0.05       0
Bank Sta=4947.7,5042.3
Exp/Cntr=0.3,0.1

Type RM Length L Ch R = 1,2799,66,66,66
BEGIN DESCRIPTION:
Mapping XS 4f8f3b6c
END DESCRIPTION:
XS GIS Cut Line= 4
      2875540.83      7018039.55      2875672.77      7017876.37
      2875790.82      7017629.85      2875890.78      7017416.15
#Sta/Elev= 30
  4742.8  418.64  4791.4  417.25  4834.6  414.32  4869.8  414.42  4884.2  412.44
  4890.6  413.01  4898.5  411.96  4941.8  410.34  4948.1  408.83  4956.2  409.31
  4973.3  408.10  4973.8  407.30  4978.8  407.30  4979.3  408.10  5133.5  408.20
  5134.6  408.20  5151.4  408.51  5155.3  410.34  5196.7  413.15  5209.2  416.88
  5219.4  416.85  5224.9  418.03  5253.4  418.22  5264.4  420.39  5276.1  420.69
  5286.5  417.91  5330.7  419.00  5384.8  417.70  5419.0  419.00  5461.9  417.79
#Mann=5,-1,0
  4742.8    0.05       0  4973.3    0.03       0  4979.3    0.05       0
  5133.5    0.16       0  5134.6    0.05       0
Bank Sta=4941.8,5155.3
Exp/Cntr=0.3,0.1

Type RM Length L Ch R = 1,2733,45,45,45
BEGIN DESCRIPTION:
Mapping XS 73c17b36
END DESCRIPTION:
XS GIS Cut Line= 3
      2875644.99      7018084.71      2875749.16      7017834.71
      2875915.81      7017445.85
#Sta/Elev= 30
  4785.5  418.66  4823.8  419.47  4839.4  417.99  4930.0  415.88  4959.2  413.68
  4981.8  409.64  4998.5  408.15  4999.0  407.35  5004.0  407.35  5004.5  408.15
  5009.5  409.64  5012.7  410.90  5023.5  412.68  5053.4  414.76  5066.9  415.56
  5083.5  414.69  5089.0  415.67  5107.1  414.99  5112.6  415.68  5183.3  415.42
  5188.3  414.56  5206.8  415.40  5212.3  413.95  5235.9  415.66  5264.9  415.65
  5312.0  418.22  5335.6  418.67  5404.2  417.51  5447.7  418.68  5479.4  418.01
#Mann=5,-1,0
  4785.5    0.05       0  4998.5    0.03       0  5004.5    0.05       0
  5053.4    0.16       0  5188.3    0.05       0
Bank Sta=4981.8,5009.5
Exp/Cntr=0.3,0.1

Type RM Length L Ch R = 1,2688,430,430,430
BEGIN DESCRIPTION:
Mapping XS b903a085
END DESCRIPTION:
XS GIS Cut Line= 3
      2875724.43      7018082.68      2875746.12      7017957.10
      2875938.58      7017468.37
#Sta/Elev= 30
  4804.8  419.53  4832.7  417.71  4946.7  415.70  4971.1  412.26  4977.5  408.96
  4984.7  407.30  4987.0  406.77  4995.5  408.86  5000.9  407.45  5009.7  408.09
  5031.2  406.48  5049.7  406.82  5055.0  405.11  5074.1  406.88  5076.4  404.44
  5076.9  403.64  5082.4  404.44  5103.8  406.14  5109.2  404.80  5133.6  406.85
  5139.0  405.31  5158.0  407.23  5166.0  406.77  5187.8  411.14  5193.1  410.81
  5212.2  412.92  5296.1  416.74  5350.2  417.89  5409.8  416.68  5457.5  418.52
#Mann=5,-1,0
  4804.8    0.05       0  4984.7    0.16       0  5076.4    0.07       0
  5082.4    0.16       0  5193.1    0.05       0
Bank Sta=4987,5166
Exp/Cntr=0.3,0.1

Type RM Length L Ch R = 1,2258,242,242,242
BEGIN DESCRIPTION:
Mapping XS 3a953905
END DESCRIPTION:
XS GIS Cut Line= 4
      2875837.30      7018200.12      2876015.21      7018017.87
      2876089.00      7017878.98      2876080.32      7017501.35
#Sta/Elev= 30
  4673.6  416.78  4675.5  416.84  4703.9  418.35  4732.2  417.73  4831.2  410.85
  4880.6  404.70  4894.8  403.54  4901.9  404.43  4908.9  403.34  4916.1  404.22
  4923.1  403.75  4937.9  404.54  4943.5  403.56  4954.2  403.64  4957.9  403.01
  4995.1  400.94  4995.6  400.14  5000.6  400.14  5001.1  400.94  5052.5  403.01
  5078.8  405.41  5085.0  406.95  5090.1  406.95  5109.6  411.95  5129.6  415.26
  5146.6  416.63  5159.6  417.32  5239.6  415.27  5329.6  414.71  5463.3  417.17
#Mann=5,-1,0
  4673.6    0.05       0  4675.5    0.16       0  4995.1    0.07       0
  5001.1    0.16       0  5146.6    0.05       0
Bank Sta=4957.9,5052.5
Exp/Cntr=0.3,0.1

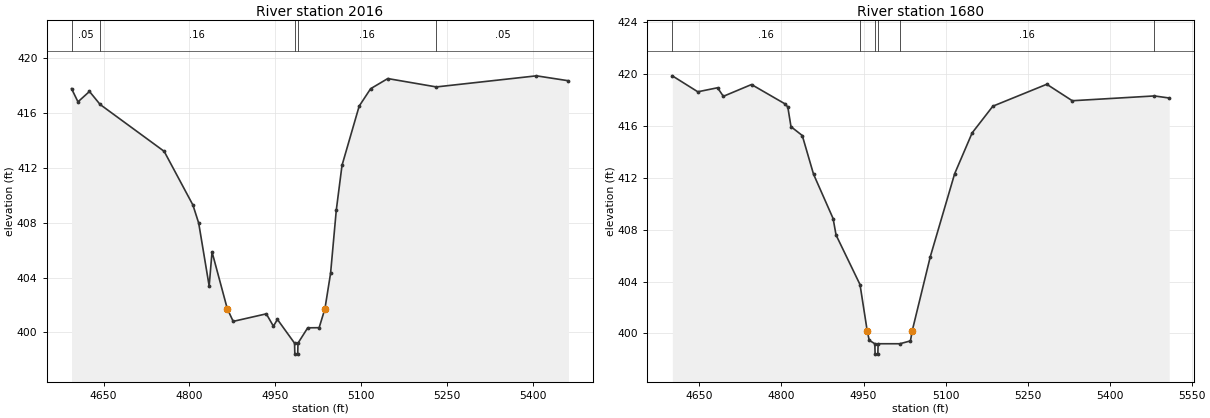
Type RM Length L Ch R = 1,2016,336,336,336
BEGIN DESCRIPTION:
Mapping XS 9d35dcda
END DESCRIPTION:
XS GIS Cut Line= 3
      2876145.42      7018456.22      2876180.15      7018113.35
      2876175.81      7017589.10
#Sta/Elev= 30
  4593.8  417.79  4605.1  416.82  4625.2  417.58  4643.8  416.63  4755.8  413.21
  4806.1  409.29  4816.2  407.97  4834.5  403.38  4839.5  405.87  4866.2  401.72
  4876.5  400.80  4934.4  401.35  4946.8  400.45  4953.9  400.94  4983.8  399.21
  4984.3  398.41  4989.3  398.41  4989.8  399.21  5006.8  400.33  5026.8  400.34
  5036.9  401.72  5046.8  404.31  5056.8  408.93  5066.8  412.19  5096.8  416.51
  5116.8  417.78  5146.8  418.52  5231.7  417.91  5406.8  418.72  5462.7  418.36
#Mann=5,-1,0
  4593.8    0.05       0  4643.8    0.16       0  4983.8    0.07       0
  4989.8    0.16       0  5231.7    0.05       0
Bank Sta=4866.2,5036.9
Exp/Cntr=0.3,0.1

Type RM Length L Ch R = 1,1680,0,0,0
BEGIN DESCRIPTION:
UNT 105 in Running Cr Watershed 1.0
END DESCRIPTION:
XS GIS Cut Line= 3
      2876551.23      7018355.49      2876467.91      7018022.21
      2876239.38      7017505.43
#Sta/Elev= 30
  4600.4  419.86  4647.0  418.63  4683.1  418.94  4693.7  418.28  4745.2  419.19
  4806.8  417.69  4811.6  417.45  4817.4  415.94  4838.0  415.26  4858.6  412.28
  4894.4  408.86  4899.8  407.59  4943.6  403.77  4956.7  400.22  4960.4  399.48
  4970.7  399.21  4971.2  398.41  4976.2  398.41  4976.7  399.21  5016.5  399.21
  5035.8  399.43  5039.1  400.22  5072.1  405.92  5116.6  412.31  5148.6  415.46
  5186.5  417.52  5285.1  419.21  5331.7  417.94  5481.8  418.31  5509.0  418.15
#Mann=6,-1,0
  4600.4    0.16       0  4943.6    0.05       0  4970.7   0.033       0
  4976.7    0.05       0  5016.5    0.16       0  5481.8    0.05       0
Bank Sta=4956.7,5039.1
Exp/Cntr=0.3,0.1

Chan Stop Cuts=-1