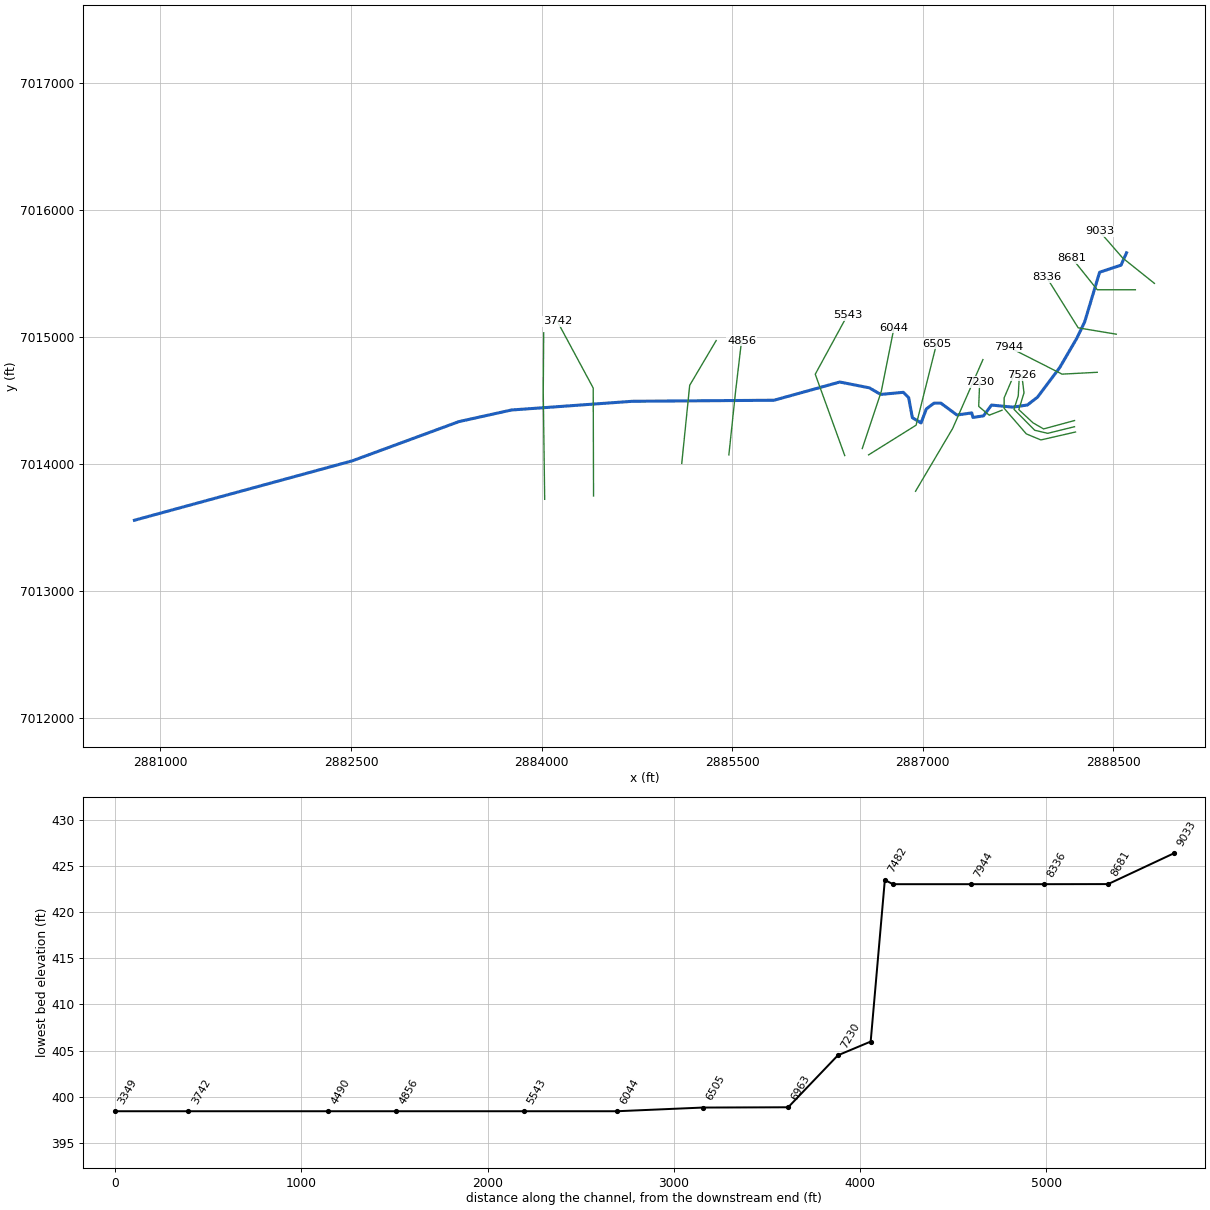
--- UNT 106 in Running Cr Watershed.prj (project) ---

Proj Title=UNT 106 in Running Cr Watershed Base Level Engineering
Current Plan=p01
Default Exp/Contr=0.3,0.1
English Units
Geom File=g01
Flow File=f01
Plan File=p01
BEGIN DESCRIPTION:
UNT 106 in Running Cr Watershed
END DESCRIPTION:

--- UNT 106 in Running Cr Watershed.p01 (plan) ---

Plan Title=Multiple Run
Short Identifier=Multiple
Geom File=g01
Flow File=f01
Subcritical Flow
K Sum by GR= 0
Std Step Tol= 0.01
Critical Tol= 0.01
Num of Std Step Trials= 20
Max Error Tol= 0.3
Flow Tol Ratio= 0.001
Split Flow NTrial= 30
Split Flow Tol= 0.02
Split Flow Ratio= 0.02
Log Output Level= 0
Friction Slope Method= 1
Unsteady Friction Slope Method= 2
Unsteady Bridges Friction Slope Method= 1
Parabolic Critical Depth
Global Vel Dist=  1 , 1 , 1
Global Log Level= 0
CheckData=True
Encroach Param= -1, 0, 0, 0
BEGIN DESCRIPTION:
Multiple Run
END DESCRIPTION:

--- UNT 106 in Running Cr Watershed.f01 (steady flow) ---

Flow Title=Multiple
Number of Profiles=7
Profile Names=10-year,25-year,50-year,1pct_min,100-year,1pct_plu,500-year
River Rch & RM= UNT 106 in Runni,Reach-1,9033
     196     246     284     164     327     653     433
River Rch & RM= UNT 106 in Runni,Reach-1,6963
     708     961    1170     708    1413    2819    2064
River Rch & RM= UNT 106 in Runni,Reach-1,4856
     822    1124    1375     836    1667    3327    2456
River Rch & RM= UNT 106 in Runni,Reach-1,3742
     833    1137    1388     842    1679    3350    2463
Boundary for River Rch & Prof#=UNT 106 in Runni,Reach-1,1
Up Type=0
Dn Type=3
Dn Slope=0.005
Boundary for River Rch & Prof#=UNT 106 in Runni,Reach-1,2
Up Type=0
Dn Type=3
Dn Slope=0.005
Boundary for River Rch & Prof#=UNT 106 in Runni,Reach-1,3
Up Type=0
Dn Type=3
Dn Slope=0.005
Boundary for River Rch & Prof#=UNT 106 in Runni,Reach-1,4
Up Type=0
Dn Type=3
Dn Slope=0.005
Boundary for River Rch & Prof#=UNT 106 in Runni,Reach-1,5
Up Type=0
Dn Type=3
Dn Slope=0.005
Boundary for River Rch & Prof#=UNT 106 in Runni,Reach-1,6
Up Type=0
Dn Type=3
Dn Slope=0.005
Boundary for River Rch & Prof#=UNT 106 in Runni,Reach-1,7
Up Type=0
Dn Type=3
Dn Slope=0.005

--- UNT 106 in Running Cr Watershed.g01 (geometry) ---

Geom Title=Existing Conditions

River Reach=UNT 106 in Runni,Reach-1
Reach XY= 30
      2888605.59      7015665.71      2888562.07      7015568.37
      2888393.65      7015512.70      2888275.51      7015120.24
      2888213.44      7014992.09      2888079.29      7014761.83
      2887905.09      7014529.56      2887824.99      7014467.49
      2887710.72      7014450.73      2887542.31      7014466.95
      2887479.43      7014382.01      2887396.12      7014369.65
      2887386.86      7014405.30      2887270.50      7014388.68
      2887143.76      7014482.18      2887089.73      7014482.18
      2887029.47      7014436.47      2886987.92      7014326.35
      2886919.35      7014367.90      2886890.26      7014525.82
      2886848.70      7014567.38      2886670.01      7014550.75
      2886580.66      7014602.70      2886347.94      7014648.41
      2885830.56      7014505.04      2884714.76      7014496.73
      2883763.11      7014428.16      2883349.62      7014336.74
      2882511.22      7014028.25      2880795.23      7013560.25

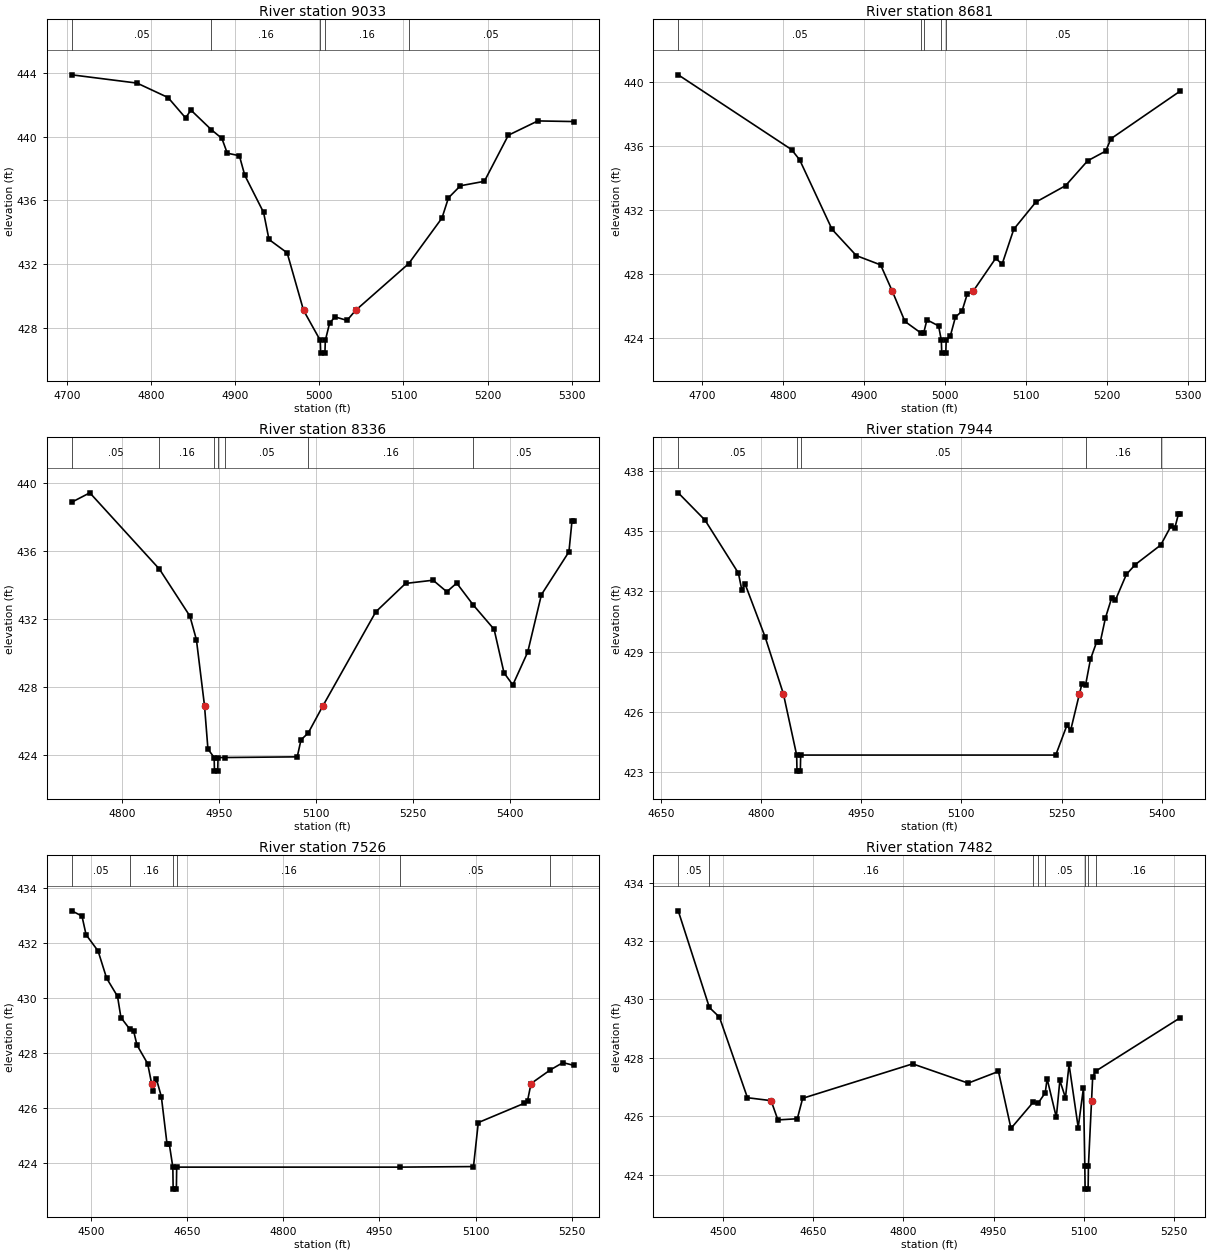
Type RM Length L Ch R = 1,9033,352,352,352
BEGIN DESCRIPTION:
UNT 106 in Running Cr Watershed 13.0
END DESCRIPTION:
XS GIS Cut Line= 3
      2888825.00      7015425.00      2888575.00      7015625.00
      2888393.13      7015833.72
#Sta/Elev= 30
  4705.6  443.90  4783.2  443.38  4820.1  442.47  4840.9  441.19  4847.3  441.68
  4871.5  440.45  4884.1  439.90  4890.5  438.97  4904.9  438.81  4911.3  437.58
  4933.7  435.24  4940.1  433.54  4961.7  432.70  4981.2  429.08  5001.1  427.19
  5001.6  426.39  5006.6  426.39  5007.1  427.19  5012.2  428.28  5018.6  428.67
  5032.9  428.45  5043.1  429.08  5106.2  432.02  5145.8  434.89  5153.5  436.16
  5167.7  436.92  5196.2  437.20  5224.7  440.10  5259.8  441.00  5302.6  440.96
#Mann=5,-1,0
  4705.6    0.05       0  4871.5    0.16       0  5001.1    0.07       0
  5007.1    0.16       0  5106.2    0.05       0
Bank Sta=4981.2,5043.1
Exp/Cntr=0.3,0.1

Type RM Length L Ch R = 1,8681,345,345,345
BEGIN DESCRIPTION:
UNT 106 in Running Cr Watershed 12.0
END DESCRIPTION:
XS GIS Cut Line= 3
      2888675.03      7015375.00      2888375.00      7015375.00
      2888174.99      7015625.01
#Sta/Elev= 30
  4670.1  440.44  4810.1  435.77  4820.1  435.13  4860.1  430.79  4890.1  429.15
  4920.1  428.57  4934.6  426.92  4950.1  425.04  4969.8  424.32  4973.3  424.32
  4977.3  425.14  4991.7  424.76  4995.1  423.86  4995.6  423.06  5000.6  423.06
  5001.1  423.86  5006.1  424.11  5012.5  425.31  5020.6  425.68  5027.0  426.73
  5034.3  426.92  5062.2  428.98  5070.2  428.62  5084.6  430.80  5111.8  432.49
  5148.6  433.52  5175.8  435.07  5198.2  435.68  5204.6  436.45  5290.3  439.43
#Mann=5,-1,0
  4670.1    0.05       0  4969.8    0.16       0  4973.3    0.05       0
  4995.1    0.03       0  5001.1    0.05       0
Bank Sta=4934.6,5034.3
Exp/Cntr=0.3,0.1

Type RM Length L Ch R = 1,8336,392,392,392
BEGIN DESCRIPTION:
UNT 106 in Running Cr Watershed 11.0
END DESCRIPTION:
XS GIS Cut Line= 3
      2888524.99      7015025.00      2888225.00      7015075.00
      2887975.01      7015474.98
#Sta/Elev= 30
  4722.7  438.87  4750.6  439.42  4858.2  434.93  4905.2  432.17  4915.3  430.78
  4927.8  426.90  4933.1  424.35  4942.7  423.85  4943.2  423.05  4948.2  423.05
  4948.7  423.85  4959.0  423.85  5071.1  423.89  5076.9  424.89  5088.0  425.29
  5110.9  426.90  5192.5  432.42  5238.5  434.09  5281.0  434.28  5302.2  433.60
  5317.5  434.11  5342.9  432.83  5375.3  431.39  5390.6  428.83  5404.2  428.12
  5427.2  430.05  5448.4  433.43  5490.9  435.95  5495.6  437.75  5498.5  437.75
#Mann=7,-1,0
  4722.7    0.05       0  4858.2    0.16       0  4942.7   0.033       0
  4948.7    0.16       0  4959.0    0.05       0  5088.0    0.16       0
  5342.9    0.05       0
Bank Sta=4927.8,5110.9
Exp/Cntr=0.3,0.1

Type RM Length L Ch R = 1,7944,418,418,418
BEGIN DESCRIPTION:
UNT 106 in Running Cr Watershed 10.0
END DESCRIPTION:
XS GIS Cut Line= 3
      2888375.02      7014725.00      2888098.00      7014710.45
      2887675.00      7014925.00
#Sta/Elev= 30
  4676.1  436.91  4716.2  435.55  4766.2  432.91  4771.3  432.07  4776.3  432.36
  4806.3  429.72  4833.6  426.89  4853.4  423.85  4853.9  423.05  4858.9  423.05
  4859.4  423.85  5241.3  423.85  5258.0  425.33  5263.6  425.08  5276.7  426.89
  5280.3  427.37  5286.1  427.36  5293.2  428.61  5302.5  429.48  5308.1  429.50
  5315.7  430.68  5324.8  431.65  5330.4  431.55  5347.1  432.85  5360.5  433.34
  5398.5  434.31  5413.9  435.26  5419.5  435.15  5425.0  435.85  5427.8  435.85
#Mann=5,-1,0
  4676.1    0.05       0  4853.4   0.033       0  4859.4    0.05       0
  5286.1    0.16       0  5398.5    0.05       0
Bank Sta=4833.6,5276.7
Exp/Cntr=0.3,0.1

Type RM Length L Ch R = 1,7526,44,44,44
BEGIN DESCRIPTION:
Mapping XS 398775b4
END DESCRIPTION:
XS GIS Cut Line= 6
      2888195.87      7014345.21      2887952.82      7014279.24
      2887869.48      7014326.98      2887757.50      7014431.15
      2887798.30      7014563.09      2887781.17      7014701.84
#Sta/Elev= 30
  4470.5  433.17  4486.4  432.98  4492.8  432.30  4511.5  431.71  4524.8  430.72
  4541.8  430.06  4547.1  429.29  4560.8  428.87  4566.8  428.81  4572.1  428.29
  4588.8  427.61  4594.9  426.89  4597.2  426.62  4602.5  427.05  4610.1  426.41
  4618.9  424.70  4622.4  424.70  4628.0  423.85  4628.5  423.05  4633.5  423.05
  4634.0  423.85  4982.3  423.85  5096.5  423.87  5104.0  425.47  5175.5  426.17
  5180.7  426.26  5186.2  426.89  5216.5  427.39  5235.9  427.65  5252.9  427.55
#Mann=6,-1,0
  4470.5    0.05       0  4560.8    0.16       0  4628.0   0.033       0
  4634.0    0.16       0  4982.3    0.05       0  5216.5    0.16       0
Bank Sta=4594.9,5186.2
Exp/Cntr=0.3,0.1

Type RM Length L Ch R = 1,7482,76,76,76
BEGIN DESCRIPTION:
Mapping XS 1c49e592
END DESCRIPTION:
XS GIS Cut Line= 6
      2888195.82      7014296.59      2887984.93      7014244.52
      2887882.50      7014268.82      2887719.31      7014433.75
      2887753.16      7014539.66      2887761.81      7014700.53
#Sta/Elev= 30
  4425.7  433.03  4477.5  429.72  4494.2  429.39  4540.8  426.63  4580.1  426.53
  4591.4  425.87  4623.7  425.91  4632.6  426.61  4815.5  427.79  4907.8  427.13
  4958.2  427.53  4979.0  425.58  5015.7  426.47  5024.4  426.45  5036.0  426.80
  5039.1  427.28  5054.4  425.96  5060.3  427.22  5069.6  426.63  5075.6  427.77
  5090.8  425.61  5099.5  426.96  5101.8  424.30  5102.3  423.50  5107.3  423.50
  5107.8  424.30  5113.0  426.53  5114.9  427.35  5119.9  427.54  5260.6  429.37
#Mann=8,-1,0
  4425.7    0.05       0  4477.5    0.16       0  5015.7    0.05       0
  5024.4    0.16       0  5036.0    0.05       0  5101.8    0.07       0
  5107.8    0.05       0  5119.9    0.16       0
Bank Sta=4580.1,5113
Exp/Cntr=0.3,0.1

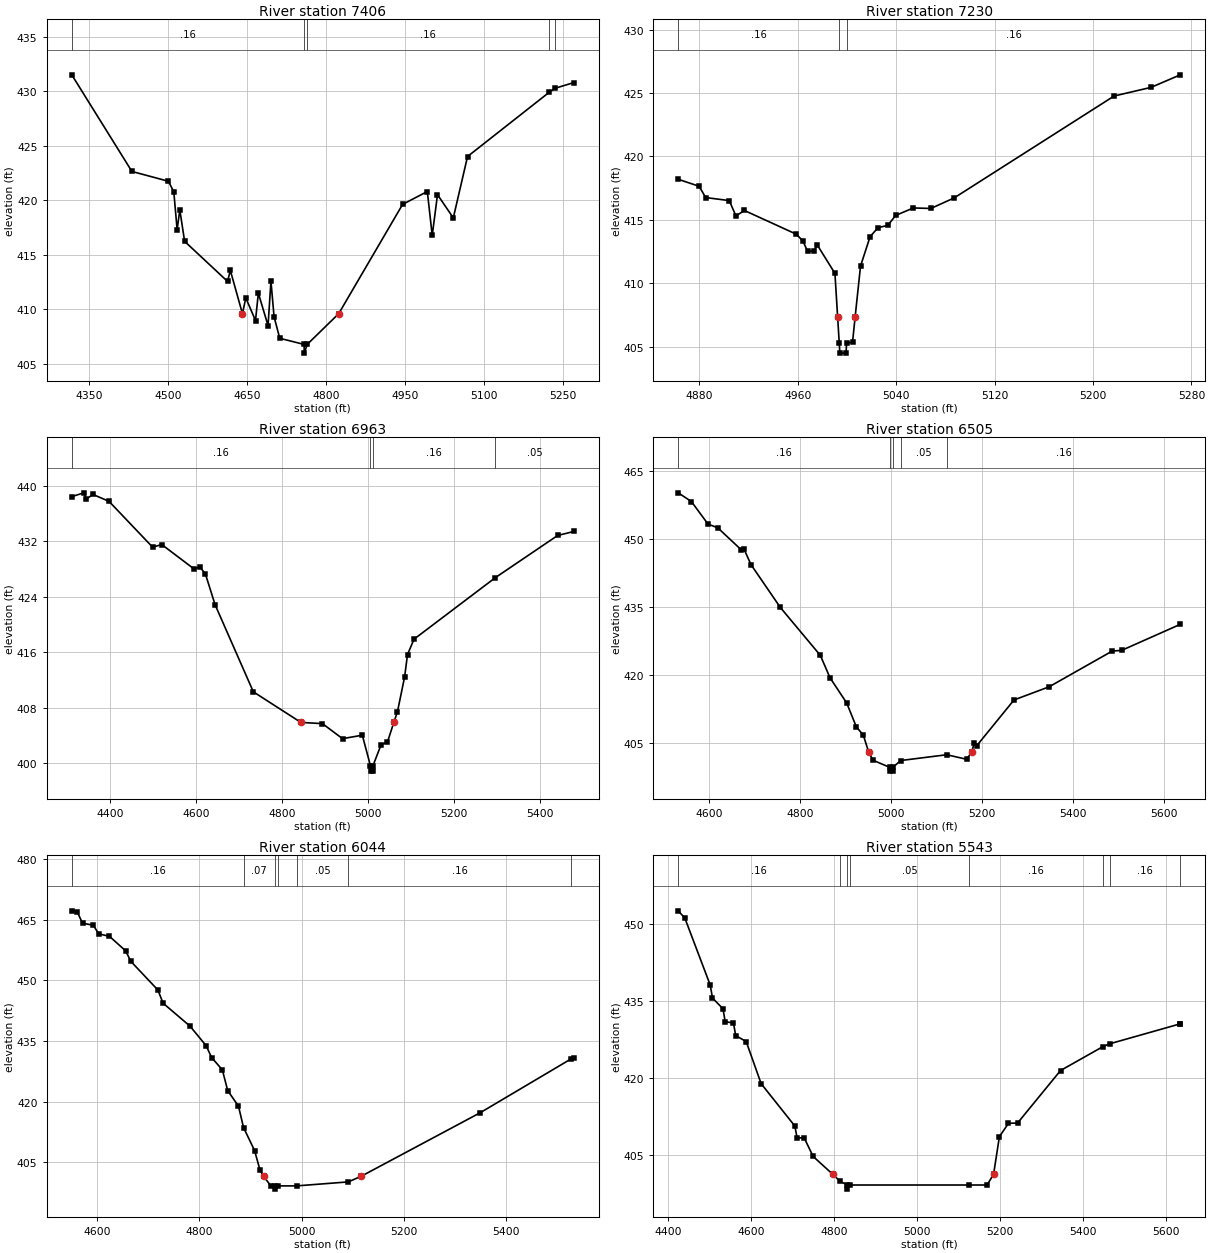
Type RM Length L Ch R = 1,7406,176,176,176
BEGIN DESCRIPTION:
Mapping XS f9df3e1b
END DESCRIPTION:
XS GIS Cut Line= 6
      2888203.72      7014254.94      2887931.11      7014192.43
      2887816.53      7014240.18      2887642.05      7014441.57
      2887642.05      7014524.03      2887720.51      7014707.68
#Sta/Elev= 30
  4317.6  431.49  4431.7  422.63  4501.0  421.73  4511.2  420.76  4517.5  417.29
  4522.6  419.10  4531.7  416.22  4613.1  412.55  4618.5  413.55  4641.4  409.59
  4647.8  411.03  4666.2  408.96  4671.6  411.47  4690.0  408.49  4695.5  412.57
  4701.4  409.31  4712.2  407.33  4758.3  406.77  4758.8  405.97  4764.3  406.77
  4824.1  409.59  4945.3  419.61  4992.2  420.79  5001.5  416.76  5011.5  420.50
  5041.5  418.37  5068.5  424.00  5224.0  429.91  5234.9  430.26  5270.2  430.78
#Mann=5,-1,0
  4317.6    0.16       0  4758.3    0.07       0  4764.3    0.16       0
  5224.0    0.05       0  5234.9    0.16       0
Bank Sta=4641.4,4824.1
Exp/Cntr=0.3,0.1

Type RM Length L Ch R = 1,7230,267,267,267
BEGIN DESCRIPTION:
UNT 106 in Running Cr Watershed 9.0
END DESCRIPTION:
XS GIS Cut Line= 4
      2887625.14      7014426.38      2887524.21      7014387.31
      2887441.75      7014456.76      2887449.34      7014648.77
#Sta/Elev= 30
  4862.8  418.19  4879.8  417.64  4885.1  416.75  4904.3  416.51  4909.7  415.30
  4916.6  415.73  4958.8  413.86  4964.2  413.32  4967.9  412.52  4973.1  412.52
  4975.9  413.00  4990.2  410.77  4992.4  407.32  4993.7  405.28  4994.2  404.48
  4999.2  404.48  4999.7  405.28  5004.5  405.33  5006.6  407.32  5011.0  411.34
  5018.8  413.67  5025.3  414.38  5033.1  414.55  5039.6  415.34  5053.9  415.93
  5068.2  415.89  5087.1  416.72  5217.2  424.76  5247.2  425.44  5271.0  426.43
#Mann=3,-1,0
  4862.8    0.16       0  4993.7    0.07       0  4999.7    0.16       0
Bank Sta=4992.4,5006.6
Exp/Cntr=0.3,0.1

Type RM Length L Ch R = 1,6963,458,458,458
BEGIN DESCRIPTION:
UNT 106 in Running Cr Watershed 8.0
END DESCRIPTION:
XS GIS Cut Line= 3
      2886944.38      7013788.39      2887236.62      7014282.63
      2887474.99      7014824.98
#Sta/Elev= 30
  4311.7  438.41  4339.6  438.96  4345.4  438.06  4361.0  438.72  4398.1  437.74
  4499.5  431.13  4520.9  431.50  4595.1  428.02  4609.8  428.24  4622.3  427.25
  4644.7  422.83  4733.6  410.27  4844.2  405.86  4894.1  405.69  4940.8  403.52
  4986.8  404.02  5005.6  399.64  5006.1  398.84  5011.2  398.84  5011.7  399.64
  5030.5  402.66  5045.1  403.01  5060.0  405.86  5068.5  407.42  5085.1  412.43
  5091.8  415.64  5106.9  417.86  5296.1  426.74  5440.6  432.81  5478.3  433.39
#Mann=4,-1,0
  4311.7    0.16       0  5005.6    0.07       0  5011.7    0.16       0
  5296.1    0.05       0
Bank Sta=4844.2,5060
Exp/Cntr=0.3,0.1

Type RM Length L Ch R = 1,6505,461,461,461
BEGIN DESCRIPTION:
UNT 106 in Running Cr Watershed 7.0
END DESCRIPTION:
XS GIS Cut Line= 3
      2886575.02      7014075.01      2886948.77      7014308.60
      2887110.03      7014949.90
#Sta/Elev= 30
  4533.0  460.12  4561.9  458.20  4598.4  453.23  4619.7  452.42  4671.5  447.55
  4677.4  447.71  4692.8  444.29  4757.0  434.88  4844.9  424.31  4866.1  419.38
  4902.7  413.83  4923.9  408.57  4939.2  406.74  4951.2  402.96  4960.5  401.21
  4997.9  399.61  4998.4  398.81  5003.5  398.81  5004.0  399.61  5020.9  401.14
  5122.4  402.42  5165.9  401.42  5176.9  402.96  5182.6  404.97  5187.8  404.36
  5270.0  414.49  5347.1  417.39  5485.6  425.26  5506.2  425.41  5635.0  431.15
#Mann=5,-1,0
  4533.0    0.16       0  4997.9    0.07       0  5004.0    0.16       0
  5020.9    0.05       0  5122.4    0.16       0
Bank Sta=4951.2,5176.9
Exp/Cntr=0.3,0.1

Type RM Length L Ch R = 1,6044,501,501,501
BEGIN DESCRIPTION:
UNT 106 in Running Cr Watershed 6.0
END DESCRIPTION:
XS GIS Cut Line= 3
      2886524.99      7014124.97      2886675.00      7014575.00
      2886775.00      7015075.02
#Sta/Elev= 30
  4549.6  467.22  4560.2  467.00  4570.7  464.15  4591.8  463.67  4602.3  461.53
  4623.4  460.92  4655.0  457.35  4665.6  454.70  4718.3  447.66  4728.8  444.36
  4781.5  438.70  4813.2  433.84  4823.7  430.95  4844.8  427.91  4855.3  422.77
  4876.4  418.93  4886.4  413.63  4908.0  407.94  4918.6  403.12  4925.6  401.63
  4939.6  399.23  4947.1  399.21  4947.6  398.41  4953.3  399.21  4990.3  399.21
  5091.8  400.20  5117.6  401.63  5350.3  417.30  5528.5  430.61  5533.9  430.78
#Mann=7,-1,0
  4549.6    0.16       0  4886.4    0.07       0  4947.1   0.033       0
  4953.3    0.07       0  4990.3    0.05       0  5091.8    0.16       0
  5528.5    0.05       0
Bank Sta=4925.6,5117.6
Exp/Cntr=0.3,0.1

Type RM Length L Ch R = 1,5543,687,687,687
BEGIN DESCRIPTION:
UNT 106 in Running Cr Watershed 5.0
END DESCRIPTION:
XS GIS Cut Line= 3
      2886387.07      7014069.57      2886154.94      7014709.73
      2886407.92      7015173.81
#Sta/Elev= 30
  4425.4  452.53  4441.3  451.12  4502.6  438.06  4507.9  435.57  4533.2  433.48
  4538.5  430.98  4558.5  430.71  4563.8  428.27  4589.1  427.11  4625.1  418.92
  4706.3  410.68  4711.6  408.42  4729.0  408.35  4750.3  404.77  4798.0  401.27
  4814.8  399.97  4832.3  399.21  4832.8  398.41  4838.5  399.21  5126.1  399.21
  5169.3  399.21  5185.0  401.27  5199.1  408.62  5221.0  411.21  5242.8  411.26
  5346.3  421.47  5447.5  426.08  5464.7  426.67  5634.1  430.54  5634.9  430.54
#Mann=8,-1,0
  4425.4    0.16       0  4814.8    0.05       0  4832.3   0.033       0
  4838.5    0.05       0  5126.1    0.16       0  5447.5     0.1       0
  5464.7    0.16       0  5634.1     0.1       0
Bank Sta=4798,5185
Exp/Cntr=0.3,0.1

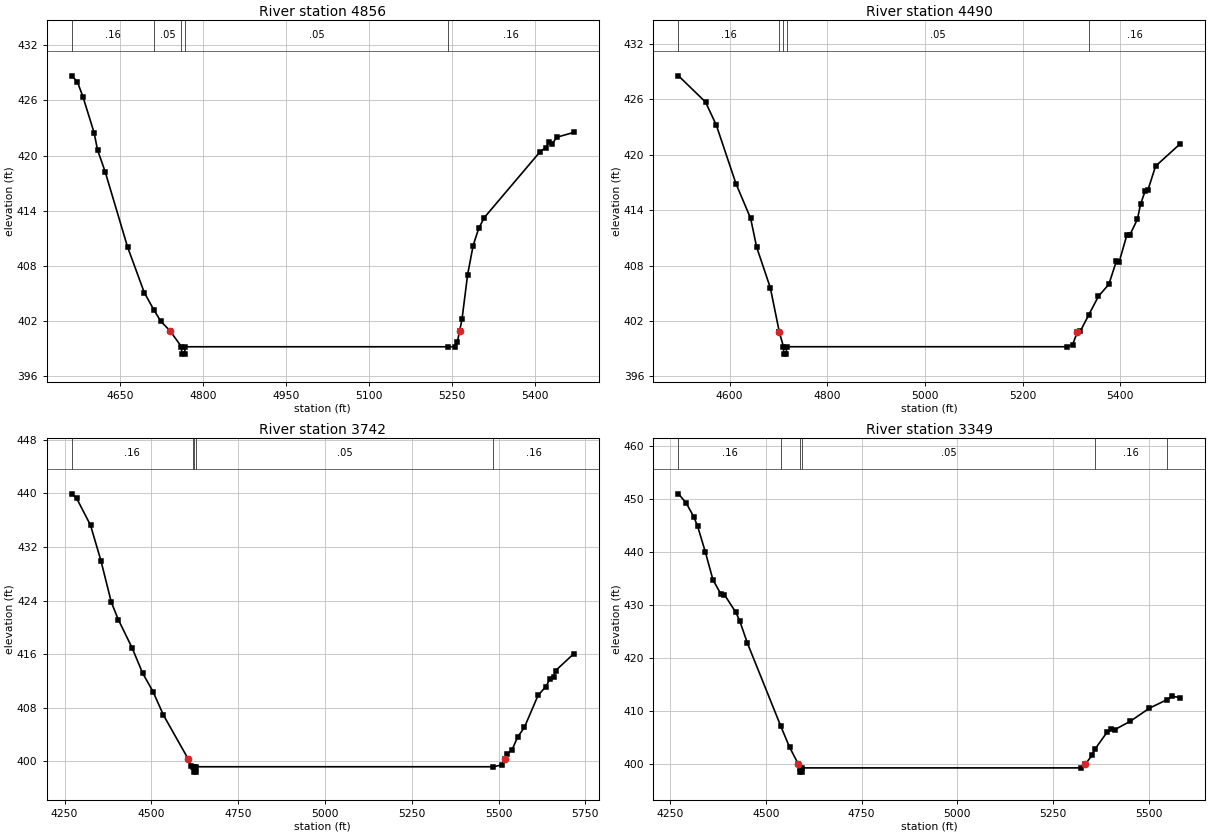
Type RM Length L Ch R = 1,4856,366,366,366
BEGIN DESCRIPTION:
UNT 106 in Running Cr Watershed 4.0
END DESCRIPTION:
XS GIS Cut Line= 3
      2885475.00      7014074.96      2885527.69      7014573.94
      2885575.00      7014975.00
#Sta/Elev= 30
  4563.5  428.67  4573.6  428.03  4583.7  426.39  4603.8  422.49  4610.0  420.62
  4623.9  418.22  4664.1  410.08  4694.3  405.11  4711.5  403.24  4724.4  401.96
  4740.8  400.95  4761.5  399.21  4762.0  398.41  4767.4  398.41  4767.9  399.21
  5242.8  399.21  5254.2  399.21  5259.2  399.71  5263.5  400.95  5267.7  402.19
  5277.8  407.04  5287.8  410.22  5297.9  412.09  5308.0  413.26  5408.7  420.42
  5418.8  420.86  5425.1  421.52  5430.1  421.25  5438.9  422.00  5469.1  422.51
#Mann=5,-1,0
  4563.5    0.16       0  4711.5    0.05       0  4761.5   0.033       0
  4767.9    0.05       0  5242.8    0.16       0
Bank Sta=4740.8,5263.5
Exp/Cntr=0.3,0.1

Type RM Length L Ch R = 1,4490,748,748,748
BEGIN DESCRIPTION:
UNT 106 in Running Cr Watershed 3.0
END DESCRIPTION:
XS GIS Cut Line= 3
      2885104.08      7014008.01      2885166.57      7014622.56
      2885375.01      7014975.02
#Sta/Elev= 30
  4495.4  428.53  4550.8  425.69  4572.8  423.20  4613.0  416.87  4643.1  413.10
  4655.5  409.97  4683.4  405.59  4701.9  400.78  4702.0  400.76  4710.3  399.21
  4710.8  398.41  4716.2  398.41  4716.7  399.21  5290.2  399.21  5302.1  399.45
  5311.8  400.78  5317.8  400.88  5335.1  402.65  5354.9  404.66  5376.3  405.97
  5391.9  408.50  5397.7  408.43  5413.4  411.34  5419.2  411.30  5434.8  413.01
  5441.2  414.64  5450.4  416.03  5456.2  416.15  5471.9  418.75  5522.6  421.19
#Mann=5,-1,0
  4495.4    0.16       0  4702.0    0.05       0  4710.3   0.033       0
  4716.7    0.05       0  5335.1    0.16       0
Bank Sta=4701.9,5311.8
Exp/Cntr=0.3,0.1

Type RM Length L Ch R = 1,3742,393,393,393
BEGIN DESCRIPTION:
UNT 106 in Running Cr Watershed 2.0
END DESCRIPTION:
XS GIS Cut Line= 3
      2884409.63      7013750.99      2884407.07      7014601.15
      2884125.01      7015124.97
#Sta/Elev= 30
  4270.9  439.93  4284.9  439.27  4324.9  435.25  4354.9  429.95  4384.9  423.74
  4404.9  421.17  4444.9  416.92  4474.9  413.19  4504.9  410.42  4534.9  406.92
  4605.8  400.41  4614.9  399.25  4618.9  399.23  4621.6  399.21  4622.1  398.41
  4627.7  398.41  4628.2  399.21  5485.1  399.21  5510.8  399.51  5519.7  400.41
  5523.0  401.05  5538.4  401.70  5554.6  403.62  5574.1  405.07  5613.8  409.88
  5636.5  411.18  5647.9  412.36  5658.4  412.57  5664.1  413.55  5716.0  416.05
#Mann=5,-1,0
  4270.9    0.16       0  4618.9    0.05       0  4621.6   0.033       0
  4628.2    0.05       0  5485.1    0.16       0
Bank Sta=4605.8,5519.7
Exp/Cntr=0.3,0.1

Type RM Length L Ch R = 1,3349,0,0,0
BEGIN DESCRIPTION:
UNT 106 in Running Cr Watershed 1.0
END DESCRIPTION:
XS GIS Cut Line= 3
      2884025.00      7013725.00      2884013.80      7014563.53
      2884017.27      7015035.71
#Sta/Elev= 30
  4271.7  451.03  4291.7  449.30  4311.7  446.69  4321.7  444.89  4341.7  440.08
  4361.7  434.78  4381.7  432.17  4391.7  431.96  4421.7  428.60  4431.7  427.00
  4451.7  422.81  4538.8  407.12  4561.7  403.15  4585.1  399.88  4588.4  399.21
  4588.9  398.41  4594.5  398.41  4595.0  399.21  5321.8  399.21  5334.2  399.88
  5351.8  401.60  5359.2  402.72  5391.8  406.02  5401.8  406.50  5411.8  406.46
  5451.8  408.03  5501.8  410.50  5548.6  412.14  5561.8  412.74  5582.5  412.50
#Mann=6,-1,0
  4271.7    0.16       0  4538.8    0.05       0  4588.4   0.033       0
  4595.0    0.05       0  5359.2    0.16       0  5548.6    0.08       0
Bank Sta=4585.1,5334.2
Exp/Cntr=0.3,0.1

Chan Stop Cuts=-1