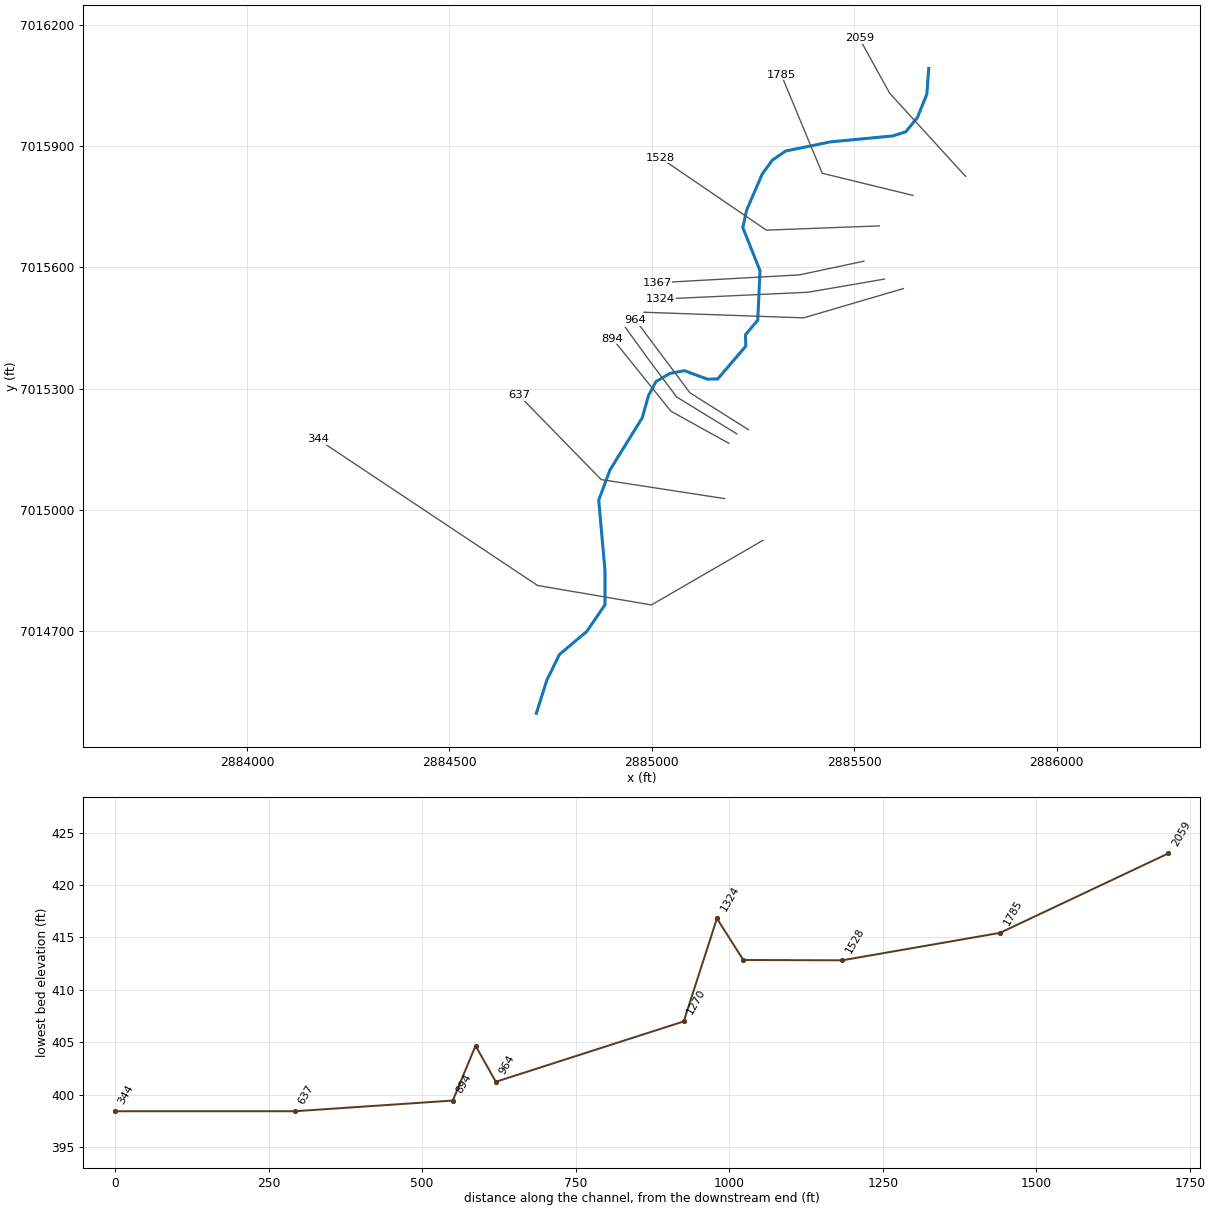
--- UNT 107 in Running Cr Watershed.prj (project) ---

Proj Title=UNT 107 in Running Cr Watershed Base Level Engineering
Current Plan=p01
Default Exp/Contr=0.3,0.1
English Units
Geom File=g01
Flow File=f01
Plan File=p01
BEGIN DESCRIPTION:
UNT 107 in Running Cr Watershed
END DESCRIPTION:

--- UNT 107 in Running Cr Watershed.p01 (plan) ---

Plan Title=Multiple Run
Short Identifier=Multiple
Geom File=g01
Flow File=f01
Subcritical Flow
K Sum by GR= 0
Std Step Tol= 0.01
Critical Tol= 0.01
Num of Std Step Trials= 20
Max Error Tol= 0.3
Flow Tol Ratio= 0.001
Split Flow NTrial= 30
Split Flow Tol= 0.02
Split Flow Ratio= 0.02
Log Output Level= 0
Friction Slope Method= 1
Unsteady Friction Slope Method= 2
Unsteady Bridges Friction Slope Method= 1
Parabolic Critical Depth
Global Vel Dist=  1 , 1 , 1
Global Log Level= 0
CheckData=True
Encroach Param= -1, 0, 0, 0
BEGIN DESCRIPTION:
Multiple Run
END DESCRIPTION:

--- UNT 107 in Running Cr Watershed.f01 (steady flow) ---

Flow Title=Multiple
Number of Profiles=7
Profile Names=10-year,25-year,50-year,1pct_min,100-year,1pct_plu,500-year
River Rch & RM= UNT 107 in Runni,Reach-1,2059
      76      87      96      52     105     209     125
Boundary for River Rch & Prof#=UNT 107 in Runni,Reach-1,1
Up Type=0
Dn Type=3
Dn Slope=0.005
Boundary for River Rch & Prof#=UNT 107 in Runni,Reach-1,2
Up Type=0
Dn Type=3
Dn Slope=0.005
Boundary for River Rch & Prof#=UNT 107 in Runni,Reach-1,3
Up Type=0
Dn Type=3
Dn Slope=0.005
Boundary for River Rch & Prof#=UNT 107 in Runni,Reach-1,4
Up Type=0
Dn Type=3
Dn Slope=0.005
Boundary for River Rch & Prof#=UNT 107 in Runni,Reach-1,5
Up Type=0
Dn Type=3
Dn Slope=0.005
Boundary for River Rch & Prof#=UNT 107 in Runni,Reach-1,6
Up Type=0
Dn Type=3
Dn Slope=0.005
Boundary for River Rch & Prof#=UNT 107 in Runni,Reach-1,7
Up Type=0
Dn Type=3
Dn Slope=0.005

--- UNT 107 in Running Cr Watershed.g01 (geometry) ---

Geom Title=Existing Conditions

River Reach=UNT 107 in Runni,Reach-1
Reach XY= 30
      2885683.99      7016092.00      2885679.30      7016028.46
      2885656.21      7015970.99      2885627.57      7015935.40
      2885595.45      7015924.98      2885440.94      7015910.23
      2885330.69      7015887.66      2885297.71      7015865.09
      2885272.53      7015830.37      2885234.34      7015741.82
      2885224.79      7015698.42      2885267.32      7015591.65
      2885261.68      7015469.25      2885231.30      7015433.23
      2885232.17      7015405.02      2885162.72      7015323.85
      2885137.12      7015323.42      2885080.69      7015344.36
      2885044.23      7015337.42      2885010.38      7015317.45
      2884992.15      7015283.60      2884976.53      7015228.04
      2884896.67      7015098.70      2884868.89      7015024.05
      2884884.51      7014848.70      2884884.51      7014765.37
      2884839.37      7014699.40      2884771.67      7014642.11
      2884740.42      7014577.87      2884714.76      7014496.73

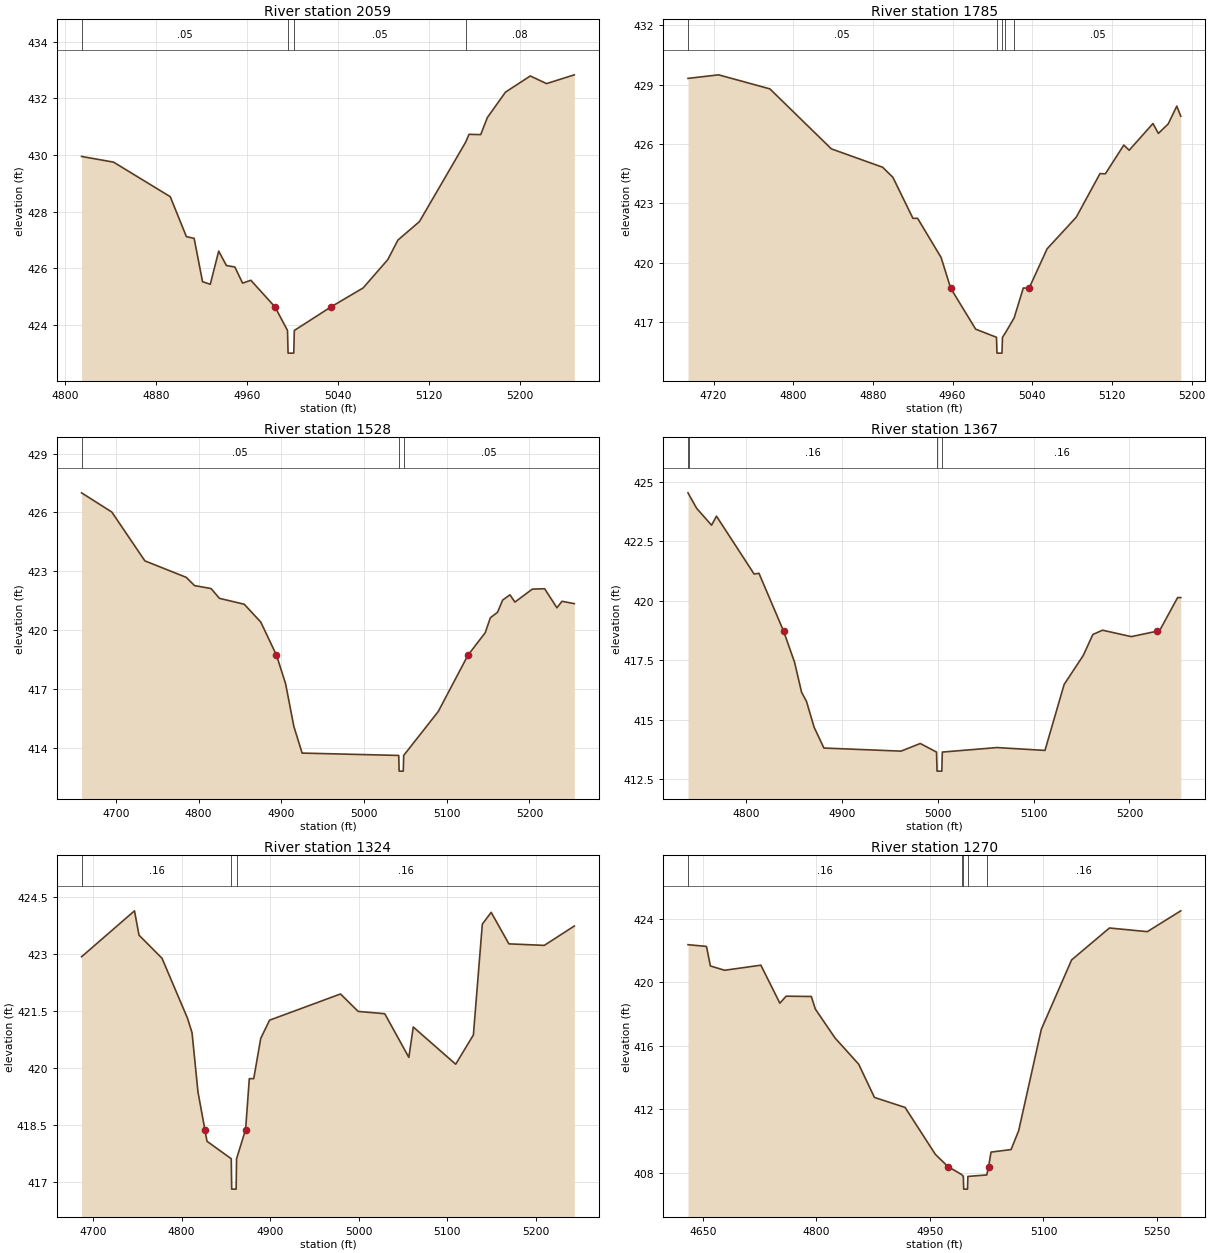
Type RM Length L Ch R = 1,2059,274,274,274
BEGIN DESCRIPTION:
UNT 107 in Running Cr Watershed 6.0
END DESCRIPTION:
XS GIS Cut Line= 3
      2885775.01      7015824.99      2885587.58      7016030.54
      2885512.69      7016166.39
#Sta/Elev= 30
  4814.8  429.95  4842.9  429.75  4892.8  428.53  4907.0  427.12  4913.8  427.06
  4921.2  425.53  4928.0  425.44  4935.4  426.61  4942.2  426.10  4949.6  426.05
  4956.4  425.48  4963.7  425.58  4984.9  424.64  4995.9  423.81  4996.4  423.01
  5001.4  423.01  5001.9  423.81  5034.1  424.64  5062.4  425.31  5084.1  426.31
  5093.0  427.00  5111.9  427.65  5152.5  430.45  5155.5  430.73  5165.8  430.72
  5171.6  431.32  5187.6  432.22  5209.4  432.79  5223.7  432.52  5248.1  432.83
#Mann=4,-1,0
  4814.8    0.05       0  4995.9    0.03       0  5001.9    0.05       0
  5152.5    0.08       0
Bank Sta=4984.9,5034.1
Exp/Cntr=0.3,0.1

Type RM Length L Ch R = 1,1785,257,257,257
BEGIN DESCRIPTION:
Mapping XS 4958252a
END DESCRIPTION:
XS GIS Cut Line= 3
      2885644.83      7015777.95      2885420.91      7015832.62
      2885319.67      7016076.66
#Sta/Elev= 30
  4694.4  429.31  4725.1  429.49  4776.6  428.78  4838.3  425.75  4889.8  424.82
  4900.1  424.31  4920.2  422.24  4924.9  422.24  4948.5  420.26  4958.1  418.71
  4983.2  416.64  5004.1  416.23  5004.6  415.43  5009.6  415.43  5010.1  416.23
  5013.0  416.45  5021.8  417.21  5031.0  418.72  5036.8  418.71  5054.9  420.70
  5084.2  422.30  5108.0  424.50  5113.4  424.49  5131.9  425.94  5137.3  425.68
  5161.2  427.03  5166.6  426.53  5176.5  427.01  5185.1  427.91  5189.1  427.40
#Mann=5,-1,0
  4694.4    0.05       0  5004.1    0.03       0  5010.1    0.05       0
  5013.0    0.16       0  5021.8    0.05       0
Bank Sta=4958.1,5036.8
Exp/Cntr=0.3,0.1

Type RM Length L Ch R = 1,1528,161,161,161
BEGIN DESCRIPTION:
UNT 107 in Running Cr Watershed 5.0
END DESCRIPTION:
XS GIS Cut Line= 3
      2885561.54      7015702.42      2885282.89      7015692.00
      2885021.18      7015870.80
#Sta/Elev= 30
  4658.5  427.00  4695.1  426.02  4735.1  423.53  4785.1  422.69  4795.1  422.27
  4815.1  422.12  4825.2  421.62  4855.2  421.32  4875.2  420.41  4894.2  418.72
  4905.2  417.27  4915.2  415.09  4925.2  413.73  5042.0  413.61  5042.5  412.81
  5047.5  412.81  5048.0  413.61  5089.8  415.85  5125.7  418.72  5146.6  419.87
  5152.8  420.63  5161.5  420.91  5167.6  421.53  5176.5  421.80  5182.5  421.43
  5203.5  422.09  5218.4  422.11  5233.3  421.14  5239.4  421.47  5254.3  421.35
#Mann=3,-1,0
  4658.5    0.05       0  5042.0   0.033       0  5048.0    0.05       0
Bank Sta=4894.2,5125.7
Exp/Cntr=0.3,0.1

Type RM Length L Ch R = 1,1367,43,43,43
BEGIN DESCRIPTION:
Mapping XS b5726ebf
END DESCRIPTION:
XS GIS Cut Line= 3
      2885523.78      7015615.18      2885364.93      7015581.32
      2885013.39      7015561.79
#Sta/Elev= 30
  4739.1  424.53  4740.3  424.44  4748.1  423.88  4763.7  423.17  4768.8  423.55
  4808.1  421.12  4813.2  421.15  4838.9  418.72  4850.3  417.42  4857.7  416.15
  4862.8  415.77  4870.8  414.68  4881.0  413.81  4961.5  413.68  4981.6  414.00
  4998.6  413.64  4999.1  412.84  5004.1  412.84  5004.6  413.64  5061.7  413.83
  5111.8  413.71  5131.8  416.48  5151.8  417.70  5161.8  418.58  5171.9  418.76
  5201.9  418.49  5229.1  418.72  5232.0  418.78  5250.3  420.13  5253.6  420.13
#Mann=4,-1,0
  4739.1    0.05       0  4740.3    0.16       0  4998.6    0.07       0
  5004.6    0.16       0
Bank Sta=4838.9,5229.1
Exp/Cntr=0.3,0.1

Type RM Length L Ch R = 1,1324,54,54,54
BEGIN DESCRIPTION:
Mapping XS 3a4c964d
END DESCRIPTION:
XS GIS Cut Line= 3
      2885574.59      7015570.91      2885385.76      7015538.35
      2885021.17      7015521.43
#Sta/Elev= 30
  4687.1  422.92  4746.9  424.13  4752.0  423.49  4778.0  422.88  4806.8  421.30
  4811.9  420.92  4818.6  419.36  4826.4  418.37  4828.8  418.06  4856.2  417.60
  4856.7  416.80  4861.7  416.80  4862.2  417.60  4872.4  418.37  4876.6  419.71
  4881.6  419.71  4889.5  420.77  4899.5  421.25  4979.6  421.94  4999.6  421.48
  5029.6  421.42  5056.8  420.27  5061.8  421.07  5109.7  420.09  5129.7  420.86
  5139.8  423.78  5149.8  424.09  5169.8  423.26  5209.8  423.22  5243.7  423.73
#Mann=3,-1,0
  4687.1    0.16       0  4856.2    0.07       0  4862.2    0.16       0
Bank Sta=4826.4,4872.4
Exp/Cntr=0.3,0.1

Type RM Length L Ch R = 1,1270,306,306,306
BEGIN DESCRIPTION:
UNT 107 in Running Cr Watershed 4.0
END DESCRIPTION:
XS GIS Cut Line= 3
      2885621.43      7015547.47      2885375.00      7015475.00
      2884980.80      7015488.88
#Sta/Elev= 30
  4630.2  422.36  4654.6  422.25  4659.8  421.02  4678.6  420.75  4726.5  421.07
  4751.6  418.68  4759.9  419.12  4793.2  419.10  4798.5  418.31  4824.5  416.49
  4855.8  414.84  4876.6  412.75  4917.1  412.12  4957.1  409.17  4973.7  408.40
  4991.8  407.90  4994.1  407.78  4994.6  406.98  4999.6  406.98  5000.1  407.78
  5025.0  407.87  5027.5  408.40  5030.7  409.31  5057.2  409.47  5067.2  410.65
  5097.2  417.04  5137.2  421.40  5187.2  423.41  5237.3  423.18  5281.5  424.49
#Mann=5,-1,0
  4630.2    0.16       0  4991.8    0.12       0  4994.1    0.07       0
  5000.1    0.12       0  5025.0    0.16       0
Bank Sta=4973.7,5027.5
Exp/Cntr=0.3,0.1

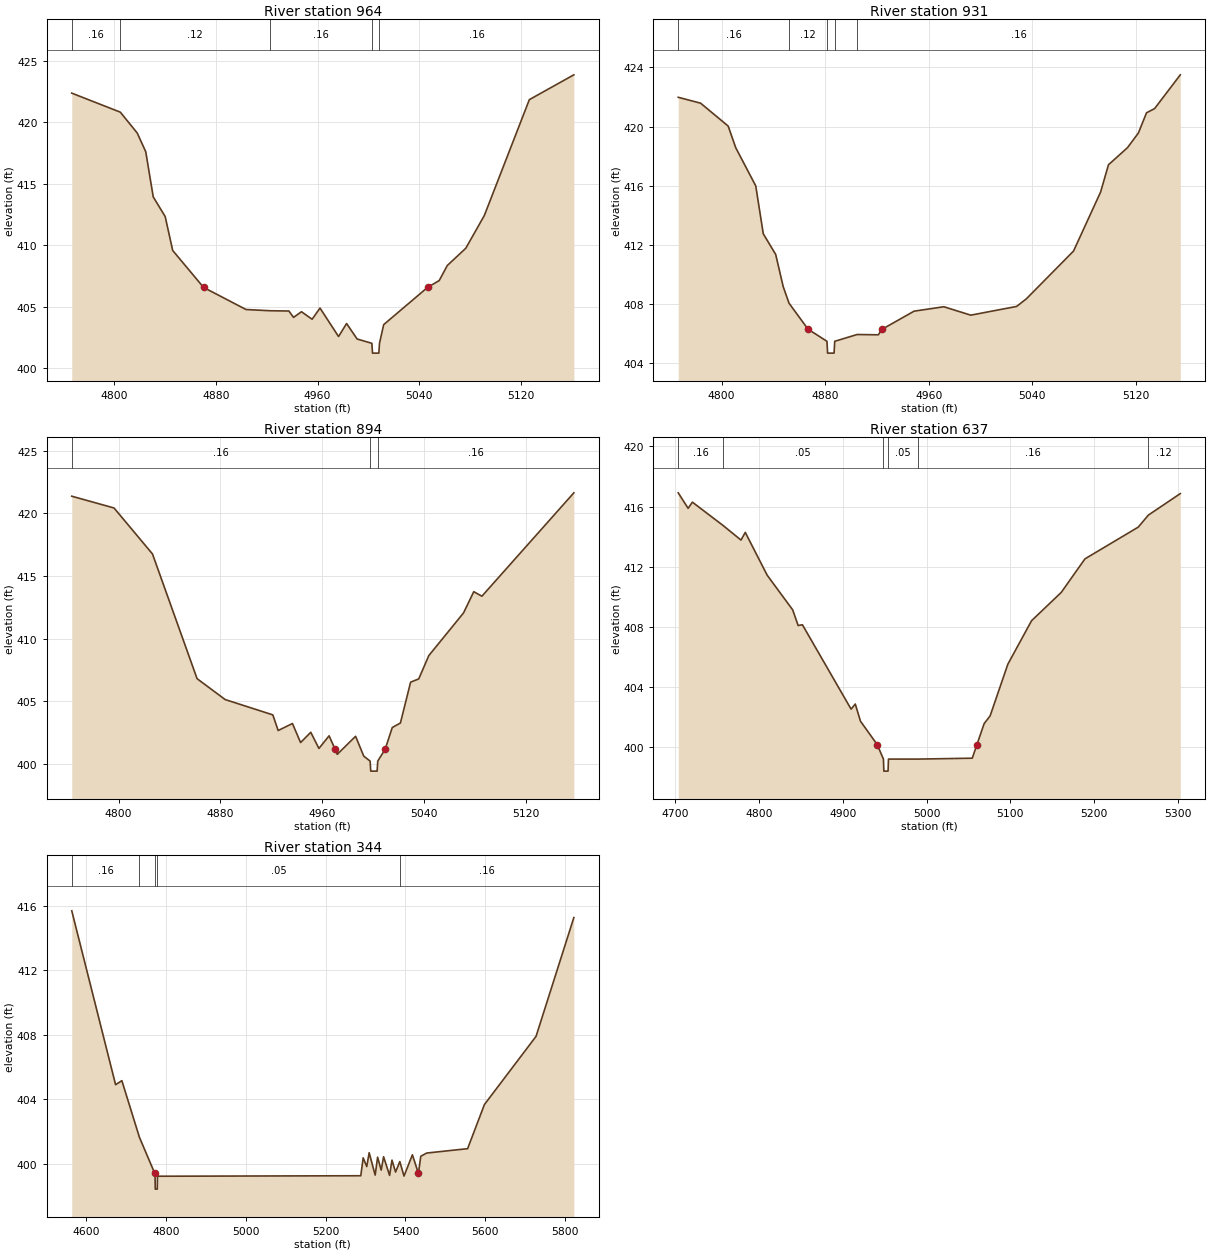
Type RM Length L Ch R = 1,964,33,33,33
BEGIN DESCRIPTION:
UNT 107 in Running Cr Watershed 3.0
END DESCRIPTION:
XS GIS Cut Line= 3
      2885238.60      7015198.52      2885094.09      7015289.66
      2884960.02      7015469.29
#Sta/Elev= 30
  4766.6  422.39  4804.8  420.84  4818.1  419.14  4824.8  417.62  4830.7  413.94
  4840.1  412.34  4846.0  409.58  4870.3  406.57  4903.7  404.77  4922.8  404.67
  4937.4  404.65  4941.1  404.13  4947.3  404.59  4955.7  403.98  4961.9  404.89
  4976.5  402.57  4982.8  403.63  4991.1  402.37  5002.7  402.02  5003.2  401.22
  5008.2  401.22  5008.7  402.02  5012.0  403.54  5046.5  406.57  5055.7  407.13
  5062.0  408.35  5076.6  409.76  5091.2  412.43  5126.6  421.86  5161.6  423.88
#Mann=5,-1,0
  4766.6    0.16       0  4804.8    0.12       0  4922.8    0.16       0
  5002.7    0.07       0  5008.7    0.16       0
Bank Sta=4870.3,5046.5
Exp/Cntr=0.3,0.1

Type RM Length L Ch R = 1,931,37,37,37
BEGIN DESCRIPTION:
Mapping XS 2fd53b59
END DESCRIPTION:
XS GIS Cut Line= 4
      2885210.02      7015188.07      2885061.54      7015279.24
      2884999.04      7015362.57      2884934.79      7015451.24
#Sta/Elev= 30
  4766.5  421.98  4783.8  421.58  4805.1  420.03  4810.9  418.57  4826.4  415.98
  4832.2  412.74  4841.8  411.34  4847.6  409.16  4852.1  408.04  4866.8  406.28
  4881.4  405.46  4881.9  404.66  4886.9  404.66  4887.4  405.46  4904.7  405.92
  4921.1  405.90  4924.1  406.28  4948.7  407.50  4971.7  407.80  4992.5  407.23
  5027.9  407.82  5035.4  408.33  5071.9  411.57  5092.8  415.56  5098.9  417.41
  5113.6  418.57  5122.0  419.56  5128.3  420.93  5134.5  421.21  5154.4  423.50
#Mann=5,-1,0
  4766.5    0.16       0  4852.1    0.12       0  4881.4    0.07       0
  4887.4    0.12       0  4904.7    0.16       0
Bank Sta=4866.8,4924.1
Exp/Cntr=0.3,0.1

Type RM Length L Ch R = 1,894,257,257,257
BEGIN DESCRIPTION:
Mapping XS 15662833
END DESCRIPTION:
XS GIS Cut Line= 3
      2885190.41      7015164.68      2885047.22      7015244.08
      2884902.71      7015423.74
#Sta/Elev= 30
  4763.3  421.37  4796.5  420.43  4826.7  416.76  4861.7  406.81  4883.8  405.14
  4921.2  403.92  4925.4  402.67  4936.6  403.23  4943.0  401.71  4951.0  402.53
  4957.4  401.24  4965.4  402.25  4970.1  401.17  4971.8  400.77  4986.2  402.21
  4992.6  400.63  4997.6  400.23  4998.1  399.43  5003.1  399.43  5003.6  400.23
  5009.4  401.17  5015.0  402.91  5021.4  403.27  5029.4  406.53  5035.8  406.79
  5043.7  408.65  5071.0  412.06  5079.0  413.75  5085.4  413.39  5157.6  421.64
#Mann=3,-1,0
  4763.3    0.16       0  4997.6    0.07       0  5003.6    0.16       0
Bank Sta=4970.1,5009.4
Exp/Cntr=0.3,0.1

Type RM Length L Ch R = 1,637,293,293,293
BEGIN DESCRIPTION:
UNT 107 in Running Cr Watershed 2.0
END DESCRIPTION:
XS GIS Cut Line= 3
      2885179.98      7015027.94      2884875.00      7015075.00
      2884672.21      7015283.16
#Sta/Elev= 30
  4703.7  416.91  4715.5  415.88  4720.6  416.29  4757.2  414.74  4778.6  413.77
  4783.7  414.28  4809.9  411.43  4840.3  409.13  4846.8  408.09  4851.9  408.14
  4910.0  402.53  4915.0  402.87  4921.2  401.73  4941.1  400.18  4948.6  399.21
  4949.1  398.41  4954.1  398.41  4954.6  399.21  4989.9  399.21  5054.6  399.27
  5060.2  400.18  5068.8  401.57  5075.9  402.08  5097.1  405.52  5125.4  408.41
  5160.8  410.29  5189.1  412.52  5252.7  414.63  5264.8  415.43  5302.9  416.86
#Mann=6,-1,0
  4703.7    0.16       0  4757.2    0.05       0  4948.6    0.07       0
  4954.6    0.05       0  4989.9    0.16       0  5264.8    0.12       0
Bank Sta=4941.1,5060.2
Exp/Cntr=0.3,0.1

Type RM Length L Ch R = 1,344,0,0,0
BEGIN DESCRIPTION:
UNT 107 in Running Cr Watershed 1.0
END DESCRIPTION:
XS GIS Cut Line= 4
      2885274.97      7014924.99      2884999.04      7014764.92
      2884717.81      7014813.13      2884175.01      7015174.99
#Sta/Elev= 30
  4564.8  415.68  4674.5  404.89  4690.2  405.14  4734.1  401.63  4772.5  399.39
  4773.3  399.21  4773.8  398.41  4778.8  398.41  4779.3  399.21  5288.2  399.24
  5294.2  400.35  5303.2  399.81  5309.2  400.67  5324.2  399.28  5330.3  400.39
  5339.3  399.59  5345.3  400.42  5360.3  399.26  5366.3  400.21  5375.3  399.47
  5385.9  400.12  5396.4  399.22  5417.4  400.54  5432.5  399.39  5438.4  400.45
  5453.4  400.65  5555.6  400.92  5597.7  403.66  5726.9  407.89  5821.5  415.26
#Mann=5,-1,0
  4564.8    0.16       0  4734.1    0.05       0  4773.3   0.033       0
  4779.3    0.05       0  5385.9    0.16       0
Bank Sta=4772.5,5432.5
Exp/Cntr=0.3,0.1

Chan Stop Cuts=-1