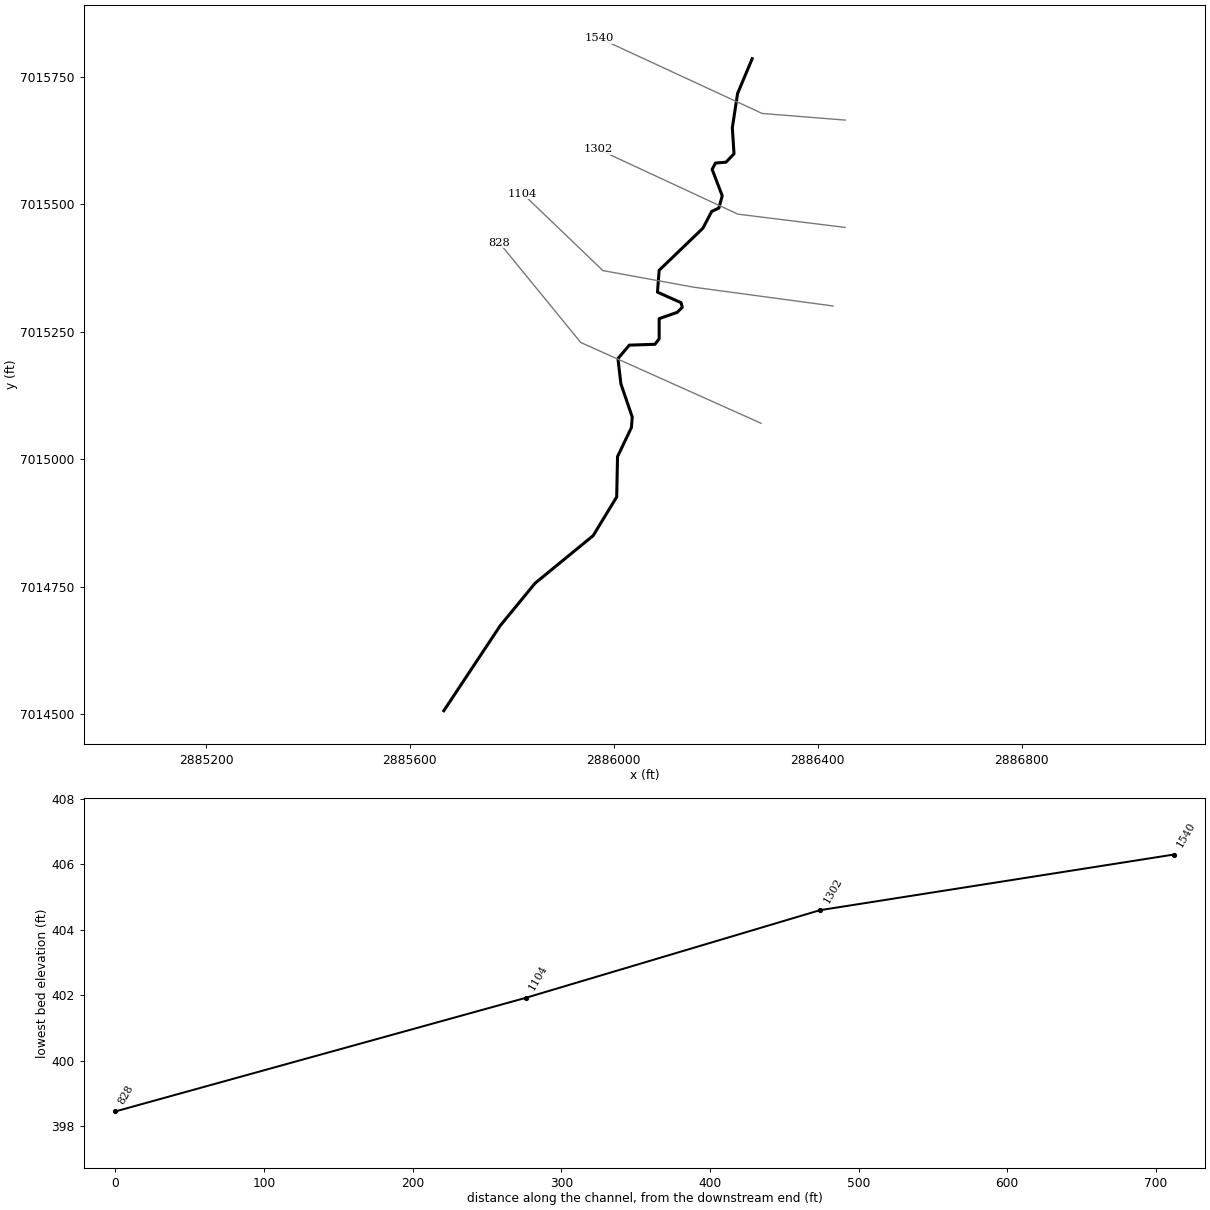
--- UNT 108 in Running Cr Watershed.prj (project) ---

Proj Title=UNT 108 in Running Cr Watershed Base Level Engineering
Current Plan=p01
Default Exp/Contr=0.3,0.1
English Units
Geom File=g01
Flow File=f01
Plan File=p01
BEGIN DESCRIPTION:
UNT 108 in Running Cr Watershed
END DESCRIPTION:

--- UNT 108 in Running Cr Watershed.p01 (plan) ---

Plan Title=Multiple Run
Short Identifier=Multiple
Geom File=g01
Flow File=f01
Subcritical Flow
K Sum by GR= 0
Std Step Tol= 0.01
Critical Tol= 0.01
Num of Std Step Trials= 20
Max Error Tol= 0.3
Flow Tol Ratio= 0.001
Split Flow NTrial= 30
Split Flow Tol= 0.02
Split Flow Ratio= 0.02
Log Output Level= 0
Friction Slope Method= 1
Unsteady Friction Slope Method= 2
Unsteady Bridges Friction Slope Method= 1
Parabolic Critical Depth
Global Vel Dist=  1 , 1 , 1
Global Log Level= 0
CheckData=True
Encroach Param= -1, 0, 0, 0
BEGIN DESCRIPTION:
Multiple Run
END DESCRIPTION:

--- UNT 108 in Running Cr Watershed.f01 (steady flow) ---

Flow Title=Multiple
Number of Profiles=7
Profile Names=10-year,25-year,50-year,1pct_min,100-year,1pct_plu,500-year
River Rch & RM= UNT 108 in Runni,Reach-1,1540
     138     168     191     108     216     431     275
Boundary for River Rch & Prof#=UNT 108 in Runni,Reach-1,1
Up Type=0
Dn Type=3
Dn Slope=0.005
Boundary for River Rch & Prof#=UNT 108 in Runni,Reach-1,2
Up Type=0
Dn Type=3
Dn Slope=0.005
Boundary for River Rch & Prof#=UNT 108 in Runni,Reach-1,3
Up Type=0
Dn Type=3
Dn Slope=0.005
Boundary for River Rch & Prof#=UNT 108 in Runni,Reach-1,4
Up Type=0
Dn Type=3
Dn Slope=0.005
Boundary for River Rch & Prof#=UNT 108 in Runni,Reach-1,5
Up Type=0
Dn Type=3
Dn Slope=0.005
Boundary for River Rch & Prof#=UNT 108 in Runni,Reach-1,6
Up Type=0
Dn Type=3
Dn Slope=0.005
Boundary for River Rch & Prof#=UNT 108 in Runni,Reach-1,7
Up Type=0
Dn Type=3
Dn Slope=0.005

--- UNT 108 in Running Cr Watershed.g01 (geometry) ---

Geom Title=Existing Conditions

River Reach=UNT 108 in Runni,Reach-1
Reach XY= 30
      2886271.56      7015785.53      2886242.88      7015717.26
      2886232.57      7015650.16      2886235.87      7015599.02
      2886220.20      7015582.52      2886199.58      7015580.87
      2886192.98      7015568.49      2886212.78      7015516.53
      2886206.18      7015492.60      2886192.15      7015486.00
      2886174.83      7015453.01      2886089.04      7015370.52
      2886085.74      7015327.62      2886131.94      7015307.00
      2886134.41      7015297.93      2886124.51      7015288.03
      2886089.04      7015275.66      2886089.04      7015236.06
      2886080.79      7015225.34      2886030.47      7015223.69
      2886008.20      7015197.29      2886013.98      7015147.80
      2886036.25      7015082.63      2886034.60      7015062.01
      2886007.38      7015005.09      2886005.73      7014925.90
      2885959.53      7014850.01      2885845.70      7014756.80
      2885777.23      7014673.48      2885666.58      7014506.59

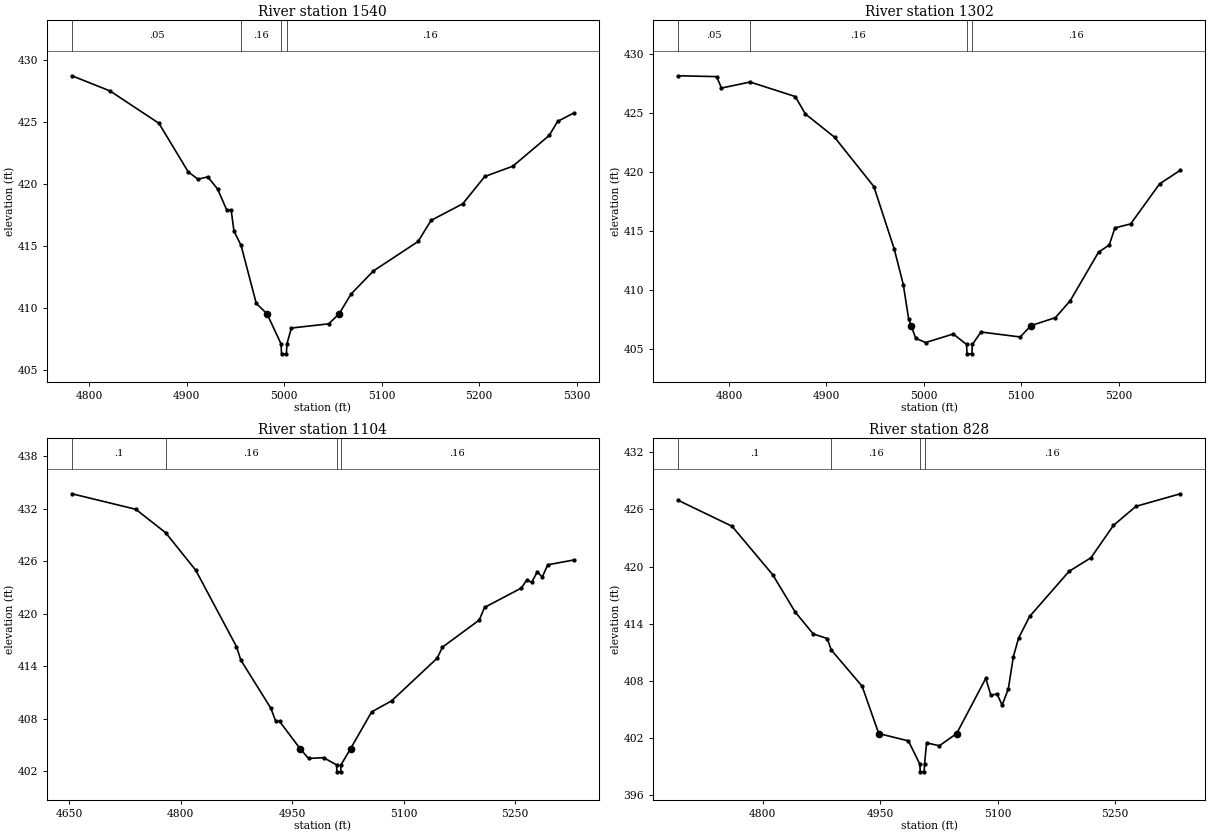
Type RM Length L Ch R = 1,1540,238,238,238
BEGIN DESCRIPTION:
UNT 108 in Running Cr Watershed 2.0
END DESCRIPTION:
XS GIS Cut Line= 3
      2886453.90      7015665.09      2886291.14      7015678.11
      2885972.10      7015825.70
#Sta/Elev= 30
  4782.3  428.72  4821.3  427.50  4871.5  424.89  4901.6  420.97  4911.6  420.38
  4921.6  420.57  4931.7  419.59  4941.1  417.90  4945.6  417.90  4948.5  416.20
  4955.8  415.04  4971.4  410.36  4982.4  409.53  4996.8  407.10  4997.3  406.30
  5002.3  406.30  5002.8  407.10  5007.4  408.38  5045.7  408.72  5056.4  409.53
  5068.6  411.12  5091.5  412.98  5137.4  415.36  5150.7  417.06  5183.2  418.40
  5205.8  420.60  5234.6  421.43  5271.9  423.91  5280.5  425.04  5297.1  425.72
#Mann=4,-1,0
  4782.3    0.05       0  4955.8    0.16       0  4996.8    0.07       0
  5002.8    0.16       0
Bank Sta=4982.4,5056.4
Exp/Cntr=0.3,0.1

Type RM Length L Ch R = 1,1302,198,198,198
BEGIN DESCRIPTION:
Mapping XS f3754313
END DESCRIPTION:
XS GIS Cut Line= 3
      2886453.88      7015454.59      2886243.40      7015480.63
      2885968.87      7015608.17
#Sta/Elev= 30
  4748.3  428.18  4787.4  428.11  4792.4  427.14  4821.8  427.65  4868.1  426.42
  4878.5  424.94  4908.4  422.97  4948.7  418.79  4969.7  413.47  4978.9  410.48
  4984.4  407.57  4986.9  406.99  4991.7  405.92  5001.8  405.56  5030.2  406.28
  5043.8  405.40  5044.3  404.60  5049.3  404.60  5049.8  405.40  5058.6  406.45
  5098.9  406.03  5109.8  406.99  5135.0  407.67  5150.2  409.11  5179.2  413.22
  5190.2  413.83  5196.0  415.28  5212.2  415.62  5241.8  419.01  5263.1  420.17
#Mann=4,-1,0
  4748.3    0.05       0  4821.8    0.16       0  5043.8    0.07       0
  5049.8    0.16       0
Bank Sta=4986.9,5109.8
Exp/Cntr=0.3,0.1

Type RM Length L Ch R = 1,1104,276,276,276
BEGIN DESCRIPTION:
Mapping XS 8b548d85
END DESCRIPTION:
XS GIS Cut Line= 4
      2886430.04      7015300.51      2886156.59      7015337.40
      2885978.64      7015369.95      2885821.17      7015520.95
#Sta/Elev= 30
  4653.8  433.71  4739.6  431.94  4779.8  429.26  4820.3  424.97  4875.1  416.24
  4880.9  414.70  4921.2  409.21  4928.0  407.69  4933.1  407.69  4960.7  404.56
  4972.0  403.45  4992.3  403.54  5009.7  402.72  5010.2  401.92  5015.2  401.92
  5015.7  402.72  5028.5  404.56  5056.9  408.77  5083.8  410.04  5145.0  414.91
  5152.2  416.18  5201.6  419.27  5208.8  420.72  5258.2  422.93  5265.4  423.83
  5272.3  423.60  5279.5  424.76  5286.5  424.20  5293.7  425.59  5328.8  426.14
#Mann=4,-1,0
  4653.8     0.1       0  4779.8    0.16       0  5009.7    0.07       0
  5015.7    0.16       0
Bank Sta=4960.7,5028.5
Exp/Cntr=0.3,0.1

Type RM Length L Ch R = 1,828,0,0,0
BEGIN DESCRIPTION:
UNT 108 in Running Cr Watershed 1.0
END DESCRIPTION:
XS GIS Cut Line= 3
      2886288.97      7015070.47      2885935.24      7015228.89
      2885775.02      7015424.97
#Sta/Elev= 30
  4692.3  426.95  4760.7  424.24  4812.6  419.15  4841.3  415.24  4864.4  412.93
  4882.2  412.45  4887.4  411.25  4926.8  407.44  4948.0  402.47  4985.9  401.70
  5000.5  399.25  5001.0  398.45  5006.0  398.45  5006.5  399.25  5009.1  401.49
  5025.4  401.19  5047.5  402.47  5084.7  408.27  5091.2  406.49  5099.1  406.63
  5105.6  405.45  5113.5  407.17  5119.9  410.54  5126.5  412.48  5140.7  414.77
  5191.1  419.51  5219.0  420.93  5247.7  424.33  5276.4  426.33  5333.1  427.65
#Mann=4,-1,0
  4692.3     0.1       0  4887.4    0.16       0  5000.5    0.07       0
  5006.5    0.16       0
Bank Sta=4948,5047.5
Exp/Cntr=0.3,0.1

Chan Stop Cuts=-1