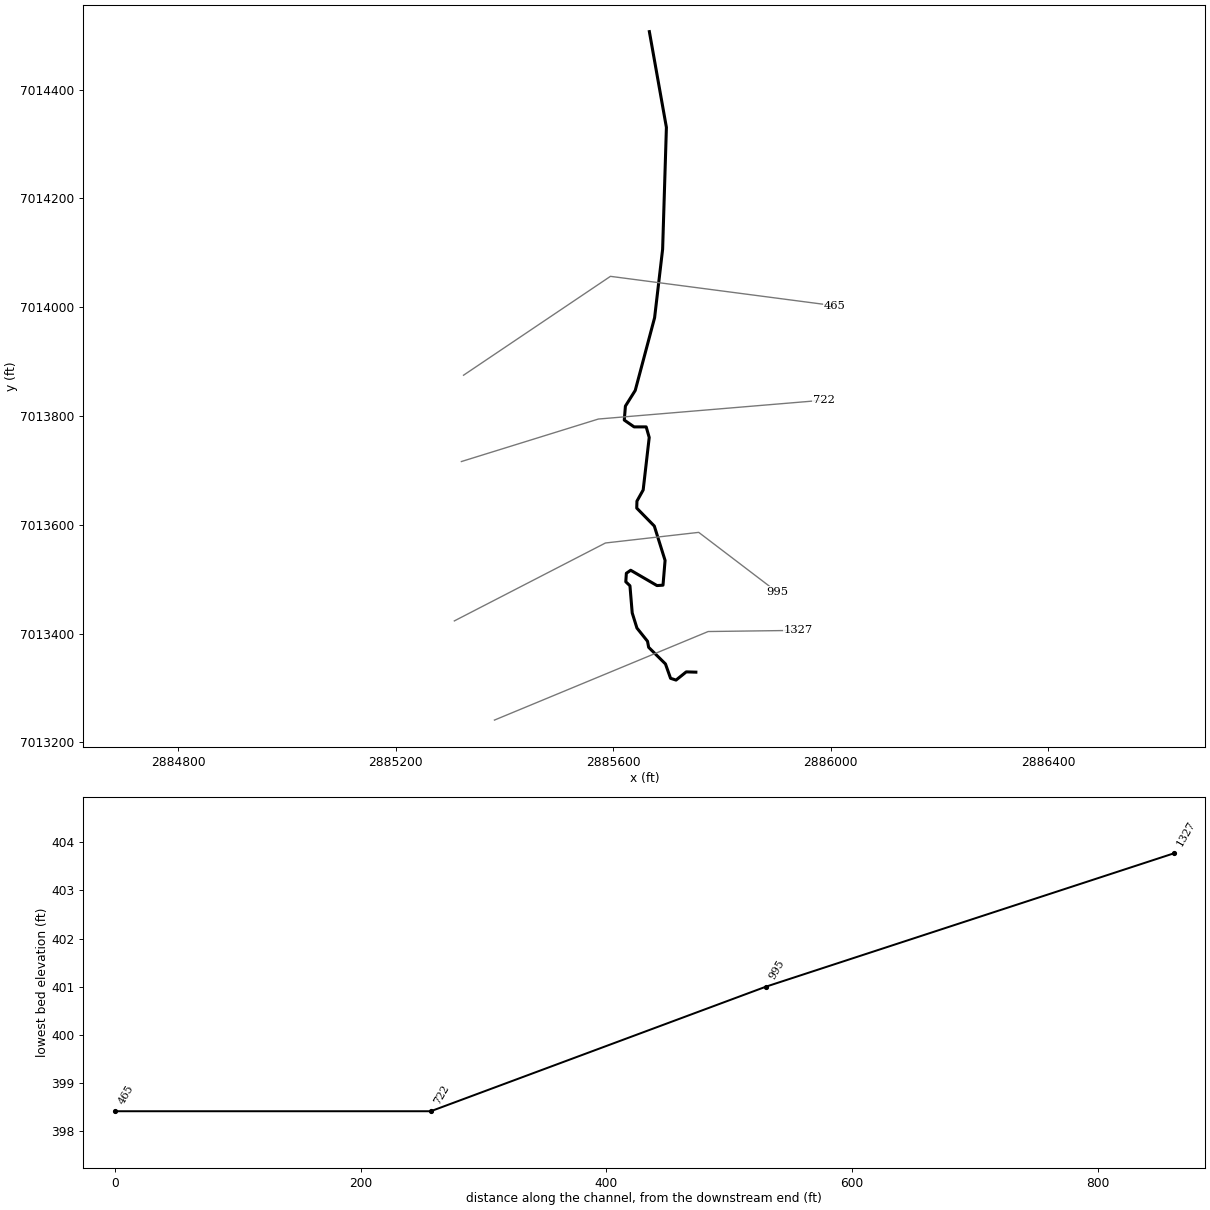
--- UNT 109 in Running Cr Watershed.prj (project) ---

Proj Title=UNT 109 in Running Cr Watershed Base Level Engineering
Current Plan=p01
Default Exp/Contr=0.3,0.1
English Units
Geom File=g01
Flow File=f01
Plan File=p01
BEGIN DESCRIPTION:
UNT 109 in Running Cr Watershed
END DESCRIPTION:

--- UNT 109 in Running Cr Watershed.p01 (plan) ---

Plan Title=Multiple Run
Short Identifier=Multiple
Geom File=g01
Flow File=f01
Subcritical Flow
K Sum by GR= 0
Std Step Tol= 0.01
Critical Tol= 0.01
Num of Std Step Trials= 20
Max Error Tol= 0.3
Flow Tol Ratio= 0.001
Split Flow NTrial= 30
Split Flow Tol= 0.02
Split Flow Ratio= 0.02
Log Output Level= 0
Friction Slope Method= 1
Unsteady Friction Slope Method= 2
Unsteady Bridges Friction Slope Method= 1
Parabolic Critical Depth
Global Vel Dist=  1 , 1 , 1
Global Log Level= 0
CheckData=True
Encroach Param= -1, 0, 0, 0
BEGIN DESCRIPTION:
Multiple Run
END DESCRIPTION:

--- UNT 109 in Running Cr Watershed.f01 (steady flow) ---

Flow Title=Multiple
Number of Profiles=7
Profile Names=10-year,25-year,50-year,1pct_min,100-year,1pct_plu,500-year
River Rch & RM= UNT 109 in Runni,Reach-1,1327
     125     152     172      97     194     388     248
Boundary for River Rch & Prof#=UNT 109 in Runni,Reach-1,1
Up Type=0
Dn Type=3
Dn Slope=0.005
Boundary for River Rch & Prof#=UNT 109 in Runni,Reach-1,2
Up Type=0
Dn Type=3
Dn Slope=0.005
Boundary for River Rch & Prof#=UNT 109 in Runni,Reach-1,3
Up Type=0
Dn Type=3
Dn Slope=0.005
Boundary for River Rch & Prof#=UNT 109 in Runni,Reach-1,4
Up Type=0
Dn Type=3
Dn Slope=0.005
Boundary for River Rch & Prof#=UNT 109 in Runni,Reach-1,5
Up Type=0
Dn Type=3
Dn Slope=0.005
Boundary for River Rch & Prof#=UNT 109 in Runni,Reach-1,6
Up Type=0
Dn Type=3
Dn Slope=0.005
Boundary for River Rch & Prof#=UNT 109 in Runni,Reach-1,7
Up Type=0
Dn Type=3
Dn Slope=0.005

--- UNT 109 in Running Cr Watershed.g01 (geometry) ---

Geom Title=Existing Conditions

River Reach=UNT 109 in Runni,Reach-1
Reach XY= 30
      2885752.07      7013329.13      2885734.37      7013329.65
      2885715.62      7013314.55      2885705.55      7013317.84
      2885696.17      7013344.23      2885665.27      7013374.79
      2885663.19      7013385.90      2885643.74      7013410.20
      2885635.06      7013437.98      2885630.89      7013487.98
      2885623.25      7013495.27      2885624.30      7013510.90
      2885632.28      7013516.45      2885680.55      7013488.33
      2885691.66      7013489.02      2885695.48      7013534.51
      2885675.69      7013597.70      2885643.39      7013630.69
      2885643.74      7013643.54      2885655.20      7013664.02
      2885666.31      7013760.55      2885660.75      7013780.00
      2885638.53      7013780.00      2885620.48      7013792.50
      2885622.56      7013818.19      2885640.62      7013847.01
      2885676.21      7013980.69      2885690.96      7014106.56
      2885697.91      7014330.52      2885666.58      7014506.59

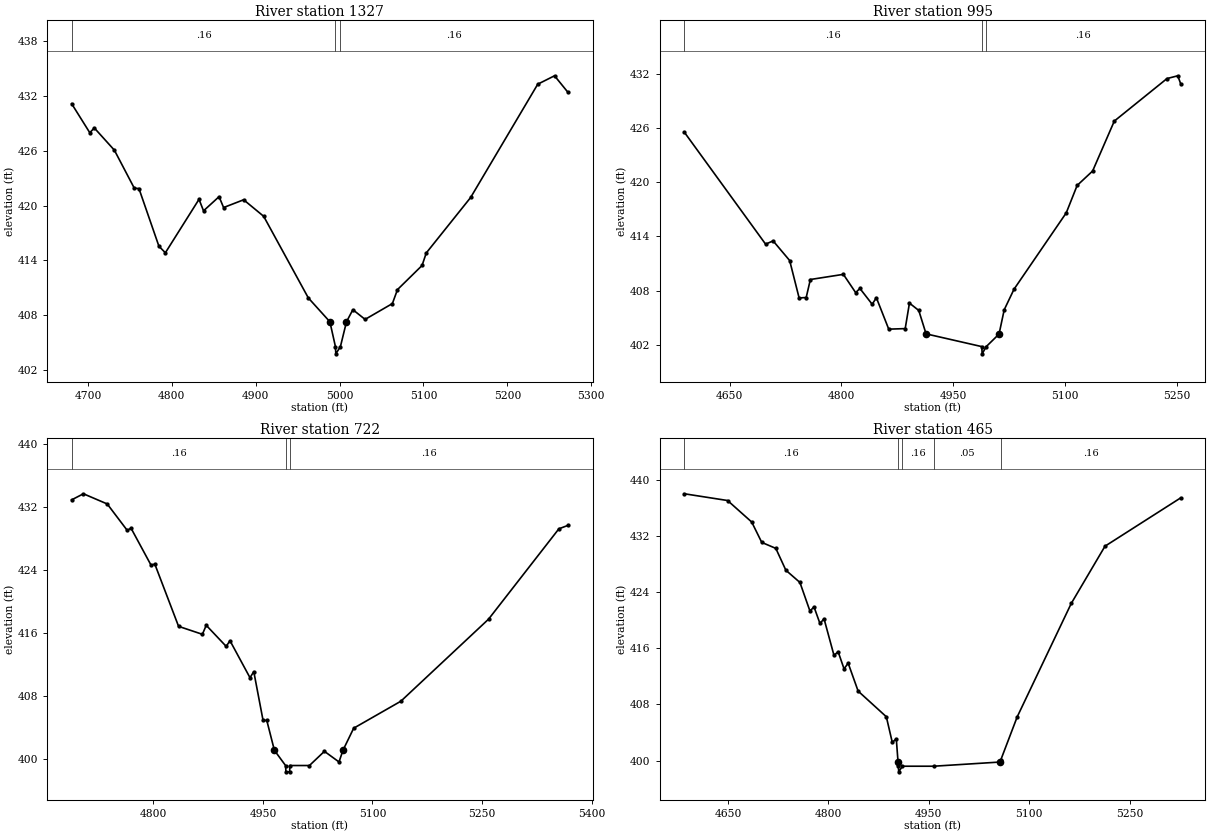
Type RM Length L Ch R = 1,1327,332,332,332
BEGIN DESCRIPTION:
UNT 109 in Running Cr Watershed 2.0
END DESCRIPTION:
XS GIS Cut Line= 3
      2885381.82      7013241.03      2885774.65      7013403.81
      2885940.92      7013405.96
#Sta/Elev= 30
  4680.6  431.14  4702.2  427.97  4707.6  428.49  4731.5  426.06  4755.3  421.89
  4760.8  421.86  4784.6  415.55  4792.3  414.83  4832.4  420.68  4837.8  419.42
  4856.3  420.97  4861.7  419.78  4885.6  420.63  4909.5  418.82  4962.7  409.89
  4988.4  407.28  4995.0  404.57  4995.5  403.77  5001.0  404.57  5008.2  407.28
  5015.8  408.60  5030.4  407.54  5062.9  409.27  5069.0  410.80  5098.3  413.44
  5103.3  414.81  5156.2  420.88  5236.2  433.28  5256.2  434.20  5272.1  432.40
#Mann=3,-1,0
  4680.6    0.16       0  4995.0    0.07       0  5001.0    0.16       0
Bank Sta=4988.4,5008.2
Exp/Cntr=0.3,0.1

Type RM Length L Ch R = 1,995,273,273,273
BEGIN DESCRIPTION:
Mapping XS e0716463
END DESCRIPTION:
XS GIS Cut Line= 4
      2885308.09      7013423.35      2885585.85      7013566.57
      2885757.29      7013586.10      2885901.34      7013476.44
#Sta/Elev= 30
  4589.4  425.50  4698.4  413.13  4708.5  413.49  4730.7  411.32  4743.4  407.18
  4752.9  407.23  4758.5  409.22  4802.8  409.79  4819.3  407.77  4825.0  408.23
  4841.5  406.48  4847.1  407.21  4863.7  403.73  4885.8  403.79  4891.5  406.61
  4904.0  405.80  4913.8  403.21  4988.6  401.80  4989.1  401.00  4994.6  401.80
  5011.8  403.19  5018.7  405.87  5031.9  408.15  5102.0  416.59  5116.6  419.62
  5137.4  421.22  5166.5  426.74  5237.2  431.44  5251.7  431.75  5255.5  430.89
#Mann=3,-1,0
  4589.4    0.16       0  4988.6    0.07       0  4994.6    0.16       0
Bank Sta=4913.8,5011.8
Exp/Cntr=0.3,0.1

Type RM Length L Ch R = 1,722,257,257,257
BEGIN DESCRIPTION:
Mapping XS 3334bbef
END DESCRIPTION:
XS GIS Cut Line= 3
      2885321.07      7013716.30      2885572.82      7013794.43
      2885987.28      7013829.15
#Sta/Elev= 30
  4688.1  432.88  4704.2  433.65  4736.8  432.36  4764.2  429.01  4769.4  429.29
  4796.7  424.62  4802.0  424.73  4834.5  416.85  4867.1  415.84  4872.4  416.98
  4899.7  414.31  4904.9  415.03  4932.3  410.34  4937.5  411.11  4950.2  404.93
  4955.3  404.93  4965.7  401.14  4981.0  399.21  4981.5  398.41  4986.5  398.41
  4987.0  399.21  5013.7  399.21  5034.2  401.01  5054.2  399.66  5059.6  401.14
  5074.3  403.94  5138.9  407.36  5259.0  417.76  5355.3  429.21  5367.6  429.64
#Mann=3,-1,0
  4688.1    0.16       0  4981.0    0.07       0  4987.0    0.16       0
Bank Sta=4965.7,5059.6
Exp/Cntr=0.3,0.1

Type RM Length L Ch R = 1,465,0,0,0
BEGIN DESCRIPTION:
UNT 109 in Running Cr Watershed 1.0
END DESCRIPTION:
XS GIS Cut Line= 3
      2885324.99      7013874.99      2885595.04      7014056.75
      2886006.89      7014002.76
#Sta/Elev= 30
  4585.0  437.98  4649.5  437.02  4685.5  433.96  4700.5  431.06  4721.5  430.21
  4736.5  427.10  4757.5  425.36  4772.5  421.28  4778.5  421.89  4787.4  419.52
  4793.5  420.19  4808.4  414.97  4814.5  415.52  4823.4  413.06  4829.5  413.88
  4844.4  409.90  4886.5  406.25  4895.4  402.60  4901.4  403.11  4904.0  399.80
  4904.5  399.21  4905.0  398.41  4910.5  399.21  4957.2  399.21  5055.5  399.80
  5057.4  400.10  5081.9  406.23  5162.6  422.37  5213.0  430.52  5325.9  437.39
#Mann=5,-1,0
  4585.0    0.16       0  4904.5   0.033       0  4910.5    0.16       0
  4957.2    0.05       0  5057.4    0.16       0
Bank Sta=4904,5055.5
Exp/Cntr=0.3,0.1

Chan Stop Cuts=-1