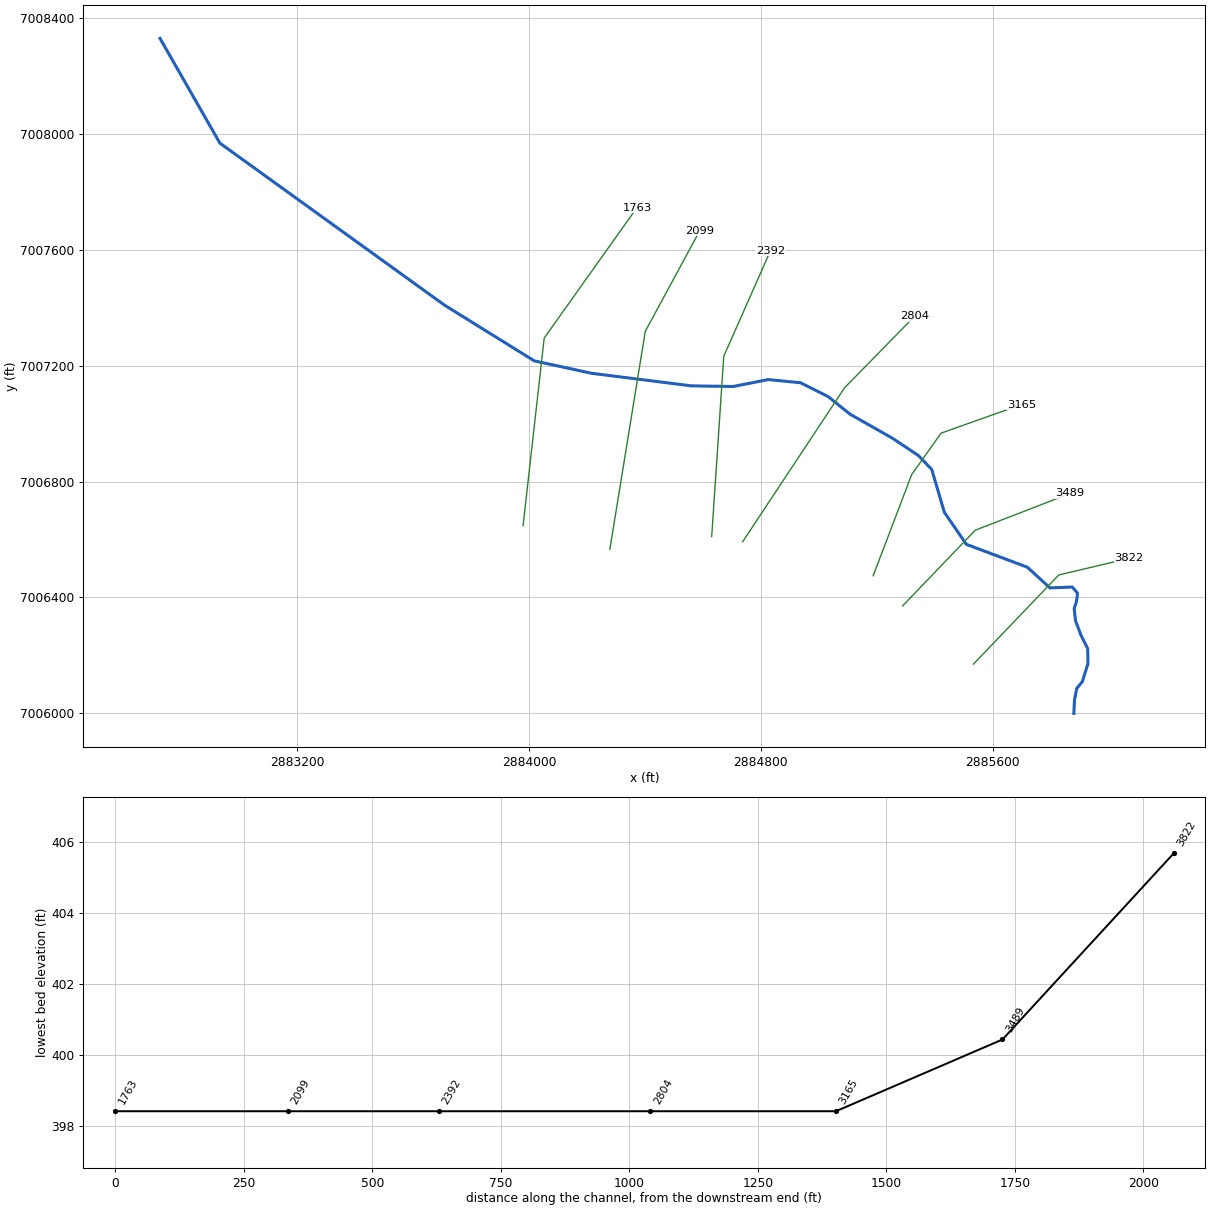
--- UNT 110 in Running Cr Watershed.prj (project) ---

Proj Title=UNT 110 in Running Cr Watershed Base Level Engineering
Current Plan=p01
Default Exp/Contr=0.3,0.1
English Units
Geom File=g01
Flow File=f01
Plan File=p01
BEGIN DESCRIPTION:
UNT 110 in Running Cr Watershed
END DESCRIPTION:

--- UNT 110 in Running Cr Watershed.p01 (plan) ---

Plan Title=Multiple Run
Short Identifier=Multiple
Geom File=g01
Flow File=f01
Subcritical Flow
K Sum by GR= 0
Std Step Tol= 0.01
Critical Tol= 0.01
Num of Std Step Trials= 20
Max Error Tol= 0.3
Flow Tol Ratio= 0.001
Split Flow NTrial= 30
Split Flow Tol= 0.02
Split Flow Ratio= 0.02
Log Output Level= 0
Friction Slope Method= 1
Unsteady Friction Slope Method= 2
Unsteady Bridges Friction Slope Method= 1
Parabolic Critical Depth
Global Vel Dist=  1 , 1 , 1
Global Log Level= 0
CheckData=True
Encroach Param= -1, 0, 0, 0
BEGIN DESCRIPTION:
Multiple Run
END DESCRIPTION:

--- UNT 110 in Running Cr Watershed.f01 (steady flow) ---

Flow Title=Multiple
Number of Profiles=7
Profile Names=10-year,25-year,50-year,1pct_min,100-year,1pct_plu,500-year
River Rch & RM= UNT 110 in Runni,Reach-1,3822
     211     264     305     176     352     702     465
Boundary for River Rch & Prof#=UNT 110 in Runni,Reach-1,1
Up Type=0
Dn Type=3
Dn Slope=0.005
Boundary for River Rch & Prof#=UNT 110 in Runni,Reach-1,2
Up Type=0
Dn Type=3
Dn Slope=0.005
Boundary for River Rch & Prof#=UNT 110 in Runni,Reach-1,3
Up Type=0
Dn Type=3
Dn Slope=0.005
Boundary for River Rch & Prof#=UNT 110 in Runni,Reach-1,4
Up Type=0
Dn Type=3
Dn Slope=0.005
Boundary for River Rch & Prof#=UNT 110 in Runni,Reach-1,5
Up Type=0
Dn Type=3
Dn Slope=0.005
Boundary for River Rch & Prof#=UNT 110 in Runni,Reach-1,6
Up Type=0
Dn Type=3
Dn Slope=0.005
Boundary for River Rch & Prof#=UNT 110 in Runni,Reach-1,7
Up Type=0
Dn Type=3
Dn Slope=0.005

--- UNT 110 in Running Cr Watershed.g01 (geometry) ---

Geom Title=Existing Conditions

River Reach=UNT 110 in Runni,Reach-1
Reach XY= 30
      2885880.69      7005999.70      2885882.86      7006045.27
      2885890.46      7006085.42      2885909.99      7006109.29
      2885929.52      7006172.22      2885928.43      7006223.22
      2885904.56      7006270.97      2885886.12      7006320.88
      2885881.78      7006362.11      2885889.37      7006384.90
      2885893.71      7006414.19      2885875.27      7006435.90
      2885798.23      7006432.64      2885720.10      7006504.26
      2885509.60      7006583.19      2885433.64      7006693.87
      2885390.24      7006841.44      2885344.67      7006889.18
      2885253.52      7006949.95      2885108.12      7007032.41
      2885032.17      7007093.18      2884936.68      7007140.92
      2884826.00      7007151.77      2884704.48      7007127.90
      2884561.25      7007130.07      2884216.19      7007173.47
      2884018.21      7007216.35      2883708.21      7007408.93
      2882933.18      7007967.88      2882726.51      7008329.56

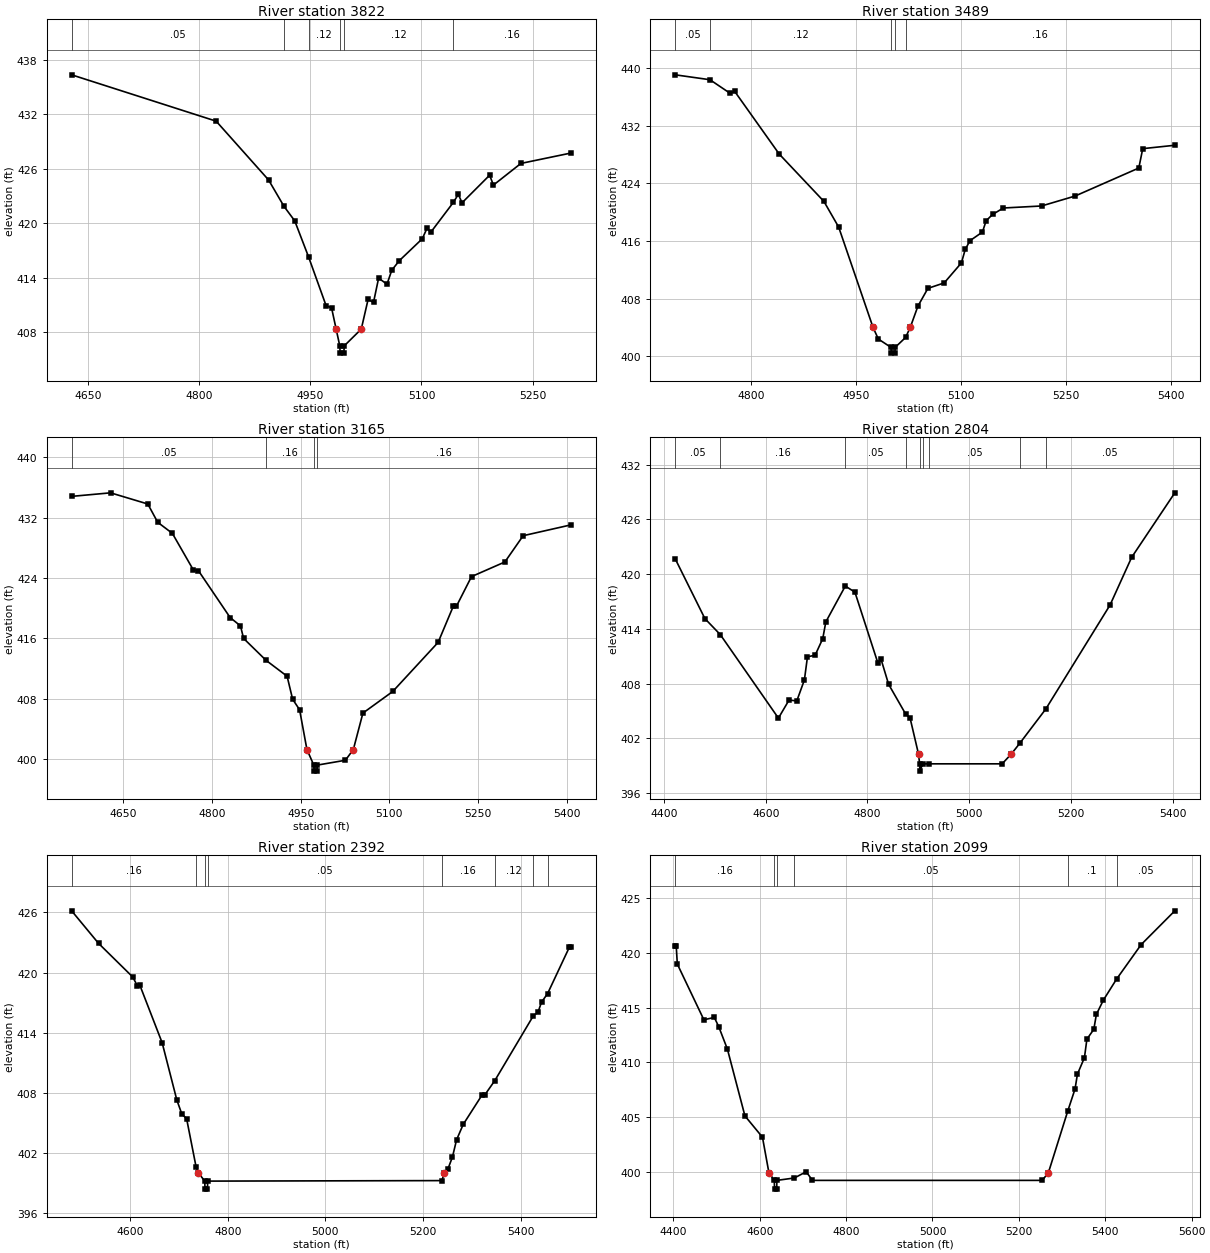
Type RM Length L Ch R = 1,3822,333,333,333
BEGIN DESCRIPTION:
UNT 110 in Running Cr Watershed 5.0
END DESCRIPTION:
XS GIS Cut Line= 3
      2885534.35      7006170.01      2885828.65      7006477.33
      2886070.46      7006534.53
#Sta/Elev= 30
  4628.0  436.36  4823.0  431.25  4893.7  424.77  4914.5  421.86  4929.0  420.26
  4947.7  416.28  4971.4  410.89  4978.7  410.67  4984.9  408.32  4989.8  406.47
  4990.3  405.67  4995.3  405.67  4995.8  406.47  5018.8  408.32  5028.0  411.59
  5035.3  411.26  5042.2  413.94  5053.5  413.27  5060.0  414.82  5070.3  415.88
  5101.1  418.28  5107.4  419.42  5112.6  419.00  5143.2  422.31  5149.7  423.18
  5154.8  422.25  5192.0  425.29  5197.1  424.20  5234.2  426.59  5302.0  427.74
#Mann=6,-1,0
  4628.0    0.05       0  4914.5    0.16       0  4947.7    0.12       0
  4989.8    0.07       0  4995.8    0.12       0  5143.2    0.16       0
Bank Sta=4984.9,5018.8
Exp/Cntr=0.3,0.1

Type RM Length L Ch R = 1,3489,324,324,324
BEGIN DESCRIPTION:
UNT 110 in Running Cr Watershed 4.0
END DESCRIPTION:
XS GIS Cut Line= 3
      2885289.56      7006370.53      2885540.07      7006631.73
      2885867.76      7006758.60
#Sta/Elev= 30
  4691.8  439.07  4741.3  438.39  4769.4  436.55  4776.7  436.76  4840.2  428.07
  4904.0  421.50  4925.1  417.93  4974.0  404.05  4981.7  402.39  4999.8  401.23
  5000.3  400.43  5005.3  400.43  5005.8  401.23  5020.7  402.61  5027.5  404.05
  5038.3  406.96  5052.5  409.42  5075.8  410.18  5100.4  412.96  5105.8  414.82
  5112.6  416.04  5130.4  417.24  5135.7  418.81  5144.8  419.68  5160.3  420.58
  5214.8  420.86  5262.7  422.24  5353.7  426.13  5359.3  428.82  5405.1  429.29
#Mann=5,-1,0
  4691.8    0.05       0  4741.3    0.12       0  4999.8    0.07       0
  5005.8    0.12       0  5020.7    0.16       0
Bank Sta=4974,5027.5
Exp/Cntr=0.3,0.1

Type RM Length L Ch R = 1,3165,361,361,361
BEGIN DESCRIPTION:
Mapping XS 5ef4b267
END DESCRIPTION:
XS GIS Cut Line= 4
      2885188.03      7006474.73      2885320.84      7006823.68
      2885422.40      7006966.91      2885700.53      7007065.69
#Sta/Elev= 30
  4563.0  434.81  4628.8  435.28  4691.7  433.80  4708.4  431.38  4733.2  429.91
  4768.6  425.07  4777.3  424.96  4830.8  418.76  4848.3  417.65  4853.6  415.99
  4891.5  413.09  4927.1  410.98  4936.4  407.94  4948.2  406.54  4960.6  401.27
  4972.2  399.21  4972.7  398.41  4977.7  398.41  4978.2  399.21  5025.6  399.85
  5039.0  401.27  5055.2  406.10  5105.6  408.96  5182.3  415.47  5207.9  420.25
  5213.2  420.25  5238.7  424.18  5295.1  426.12  5326.0  429.60  5407.1  431.04
#Mann=4,-1,0
  4563.0    0.05       0  4891.5    0.16       0  4972.2    0.07       0
  4978.2    0.16       0
Bank Sta=4960.6,5039
Exp/Cntr=0.3,0.1

Type RM Length L Ch R = 1,2804,412,412,412
BEGIN DESCRIPTION:
Mapping XS 818cebb5
END DESCRIPTION:
XS GIS Cut Line= 3
      2884737.53      7006591.95      2885089.06      7007123.16
      2885330.34      7007369.62
#Sta/Elev= 30
  4422.2  421.67  4480.4  415.13  4510.6  413.38  4624.9  404.22  4645.9  406.21
  4661.0  406.10  4676.0  408.41  4682.0  410.94  4697.1  411.12  4712.1  412.94
  4718.1  414.77  4756.4  418.70  4775.3  418.03  4820.5  410.25  4826.4  410.72
  4841.5  407.93  4875.5  404.62  4883.6  404.26  4900.3  400.28  4902.5  399.21
  4903.0  398.41  4908.5  399.21  4920.9  399.21  5064.7  399.21  5082.6  400.28
  5099.2  401.45  5150.5  405.22  5276.8  416.62  5319.3  421.85  5404.1  428.92
#Mann=9,-1,0
  4422.2    0.05       0  4510.6    0.16       0  4756.4    0.05       0
  4875.5    0.12       0  4902.5   0.033       0  4908.5    0.12       0
  4920.9    0.05       0  5099.2    0.16       0  5150.5    0.05       0
Bank Sta=4900.3,5082.6
Exp/Cntr=0.3,0.1

Type RM Length L Ch R = 1,2392,293,293,293
BEGIN DESCRIPTION:
UNT 110 in Running Cr Watershed 3.0
END DESCRIPTION:
XS GIS Cut Line= 3
      2884630.73      7006610.15      2884672.40      7007232.54
      2884833.85      7007597.11
#Sta/Elev= 30
  4480.5  426.16  4535.5  422.92  4605.6  419.56  4614.9  418.70  4620.0  418.76
  4665.8  413.00  4695.8  407.30  4705.9  405.92  4715.9  405.42  4735.1  400.66
  4739.8  400.04  4753.0  399.21  4753.5  398.41  4758.5  398.41  4759.0  399.21
  5238.5  399.26  5243.3  400.04  5250.6  400.40  5260.1  401.63  5268.4  403.32
  5282.0  404.86  5320.4  407.78  5325.9  407.78  5346.7  409.23  5425.8  415.71
  5435.1  416.05  5442.3  417.05  5454.8  417.91  5499.1  422.51  5503.0  422.51
#Mann=8,-1,0
  4480.5    0.16       0  4735.1    0.05       0  4753.0   0.033       0
  4759.0    0.05       0  5238.5    0.16       0  5346.7    0.12       0
  5425.8     0.1       0  5454.8    0.05       0
Bank Sta=4739.8,5243.3
Exp/Cntr=0.3,0.1

Type RM Length L Ch R = 1,2099,336,336,336
BEGIN DESCRIPTION:
UNT 110 in Running Cr Watershed 2.0
END DESCRIPTION:
XS GIS Cut Line= 3
      2884279.17      7006565.85      2884401.56      7007318.47
      2884589.08      7007664.86
#Sta/Elev= 30
  4404.6  420.69  4406.7  420.69  4409.3  419.00  4470.8  413.90  4494.9  414.12
  4505.1  413.28  4525.3  411.21  4565.8  405.11  4606.4  403.16  4621.3  399.92
  4633.8  399.21  4634.3  398.41  4639.3  398.41  4639.8  399.21  4680.2  399.43
  4707.7  400.00  4722.1  399.21  5254.1  399.21  5268.4  399.92  5313.4  405.58
  5330.0  407.57  5335.6  408.93  5351.8  410.44  5357.5  412.13  5373.5  413.03
  5379.4  414.39  5395.6  415.70  5426.1  417.62  5483.1  420.78  5561.0  423.87
#Mann=6,-1,0
  4404.6    0.16       0  4633.8   0.033       0  4639.8    0.16       0
  4680.2    0.05       0  5313.4     0.1       0  5426.1    0.05       0
Bank Sta=4621.3,5268.4
Exp/Cntr=0.3,0.1

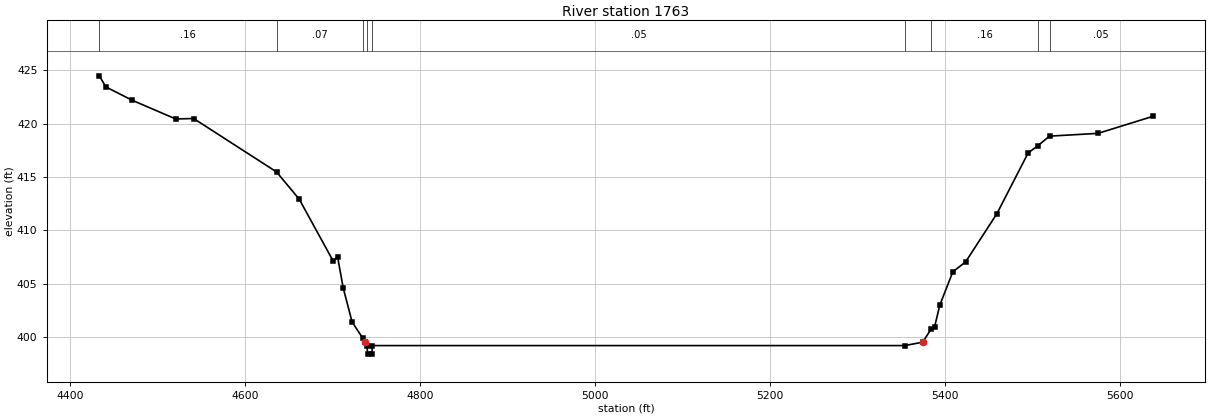
Type RM Length L Ch R = 1,1763,0,0,0
BEGIN DESCRIPTION:
UNT 110 in Running Cr Watershed 1.0
END DESCRIPTION:
XS GIS Cut Line= 3
      2883979.69      7006647.92      2884052.61      7007295.04
      2884372.92      7007745.56
#Sta/Elev= 30
  4433.4  424.48  4440.9  423.44  4470.7  422.20  4520.7  420.44  4541.2  420.48
  4635.9  415.48  4661.9  412.92  4700.6  407.14  4705.7  407.52  4712.2  404.59
  4722.3  401.42  4734.6  399.89  4737.2  399.52  4739.4  399.21  4739.9  398.41
  4744.9  398.41  4745.4  399.21  5353.9  399.21  5374.5  399.53  5384.3  400.79
  5388.0  400.95  5394.1  403.02  5408.9  406.12  5423.6  407.06  5459.3  411.57
  5495.0  417.26  5506.4  417.95  5519.4  418.83  5574.9  419.09  5637.4  420.68
#Mann=9,-1,0
  4433.4    0.16       0  4635.9    0.07       0  4734.6    0.05       0
  4739.4   0.033       0  4745.4    0.05       0  5353.9    0.07       0
  5384.3    0.16       0  5506.4    0.12       0  5519.4    0.05       0
Bank Sta=4737.2,5374.5
Exp/Cntr=0.3,0.1

Chan Stop Cuts=-1