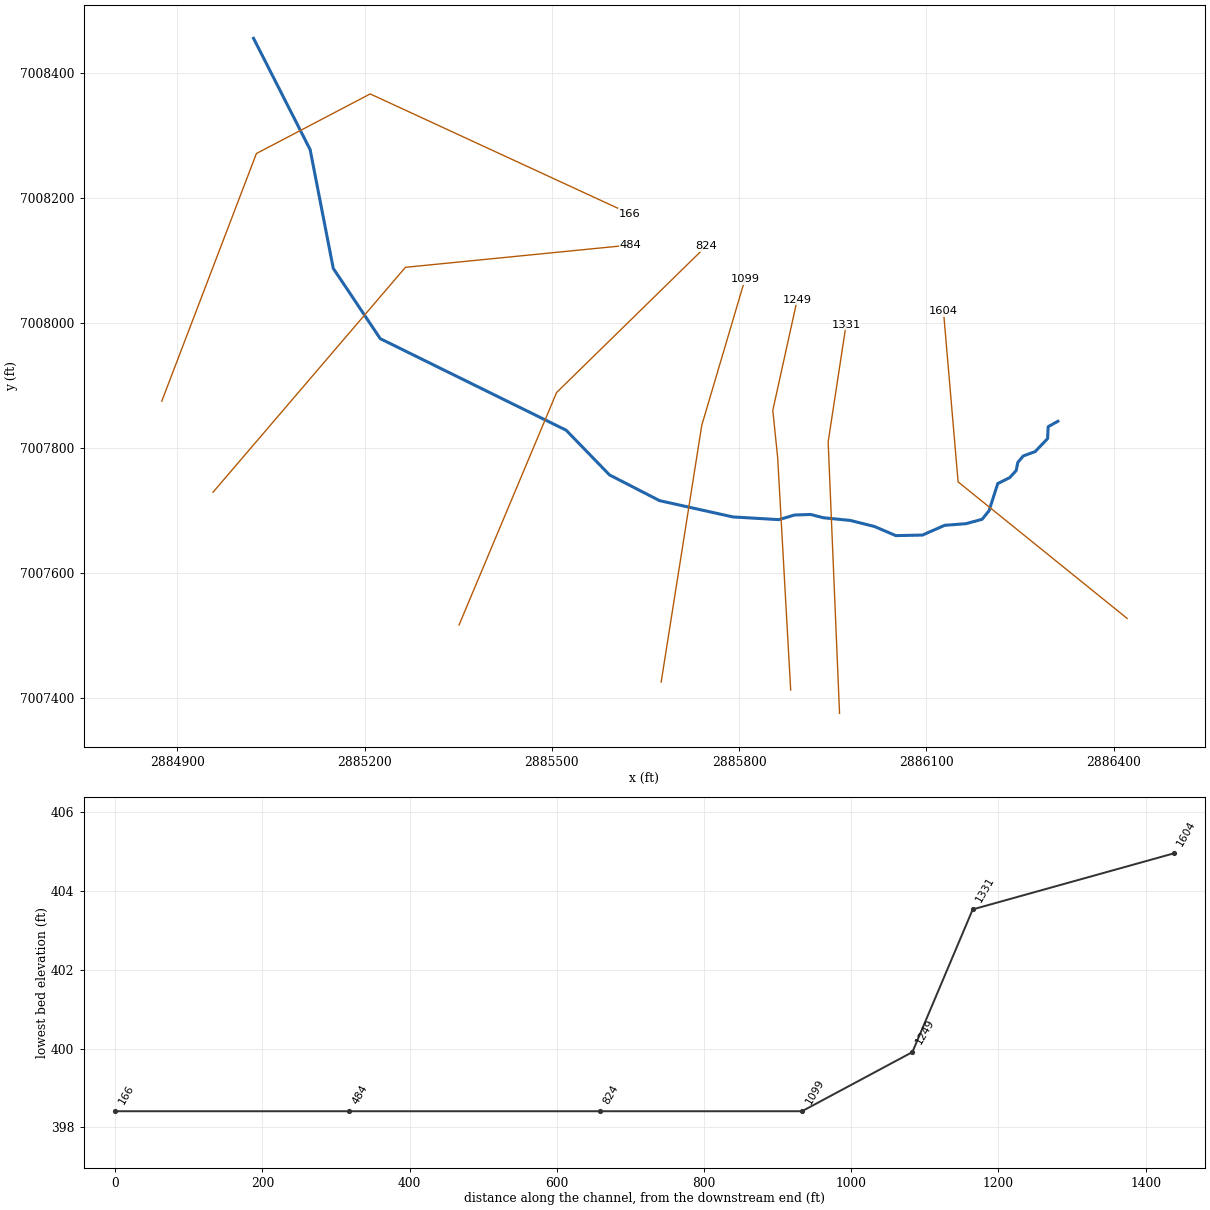
--- UNT 111 in Running Cr Watershed.prj (project) ---

Proj Title=UNT 111 in Running Cr Watershed Base Level Engineering
Current Plan=p01
Default Exp/Contr=0.3,0.1
English Units
Geom File=g01
Flow File=f01
Plan File=p01
BEGIN DESCRIPTION:
UNT 111 in Running Cr Watershed
END DESCRIPTION:

--- UNT 111 in Running Cr Watershed.p01 (plan) ---

Plan Title=Multiple Run
Short Identifier=Multiple
Geom File=g01
Flow File=f01
Subcritical Flow
K Sum by GR= 0
Std Step Tol= 0.01
Critical Tol= 0.01
Num of Std Step Trials= 20
Max Error Tol= 0.3
Flow Tol Ratio= 0.001
Split Flow NTrial= 30
Split Flow Tol= 0.02
Split Flow Ratio= 0.02
Log Output Level= 0
Friction Slope Method= 1
Unsteady Friction Slope Method= 2
Unsteady Bridges Friction Slope Method= 1
Parabolic Critical Depth
Global Vel Dist=  1 , 1 , 1
Global Log Level= 0
CheckData=True
Encroach Param= -1, 0, 0, 0
BEGIN DESCRIPTION:
Multiple Run
END DESCRIPTION:

--- UNT 111 in Running Cr Watershed.f01 (steady flow) ---

Flow Title=Multiple
Number of Profiles=7
Profile Names=10-year,25-year,50-year,1pct_min,100-year,1pct_plu,500-year
River Rch & RM= UNT 111 in Runni,Reach-1,1604
     115     138     155      88     175     349     220
Boundary for River Rch & Prof#=UNT 111 in Runni,Reach-1,1
Up Type=0
Dn Type=3
Dn Slope=0.005
Boundary for River Rch & Prof#=UNT 111 in Runni,Reach-1,2
Up Type=0
Dn Type=3
Dn Slope=0.005
Boundary for River Rch & Prof#=UNT 111 in Runni,Reach-1,3
Up Type=0
Dn Type=3
Dn Slope=0.005
Boundary for River Rch & Prof#=UNT 111 in Runni,Reach-1,4
Up Type=0
Dn Type=3
Dn Slope=0.005
Boundary for River Rch & Prof#=UNT 111 in Runni,Reach-1,5
Up Type=0
Dn Type=3
Dn Slope=0.005
Boundary for River Rch & Prof#=UNT 111 in Runni,Reach-1,6
Up Type=0
Dn Type=3
Dn Slope=0.005
Boundary for River Rch & Prof#=UNT 111 in Runni,Reach-1,7
Up Type=0
Dn Type=3
Dn Slope=0.005

--- UNT 111 in Running Cr Watershed.g01 (geometry) ---

Geom Title=Existing Conditions

River Reach=UNT 111 in Runni,Reach-1
Reach XY= 29
      2886310.55      7007842.66      2886294.93      7007833.98
      2886294.06      7007814.88      2886274.09      7007794.04
      2886255.00      7007787.10      2886246.32      7007776.68
      2886243.71      7007763.66      2886233.30      7007752.38
      2886214.20      7007742.83      2886200.31      7007699.43
      2886189.02      7007685.54      2886162.98      7007678.59
      2886129.13      7007675.99      2886093.54      7007660.36
      2886051.00      7007659.50      2886016.28      7007674.25
      2885978.09      7007683.80      2885934.68      7007688.14
      2885914.72      7007693.35      2885888.68      7007692.48
      2885863.50      7007685.10      2885789.72      7007689.44
      2885672.53      7007715.49      2885592.24      7007756.72
      2885522.79      7007828.33      2885225.00      7007975.00
      2885149.68      7008087.61      2885112.64      7008277.89
      2885022.00      7008456.15

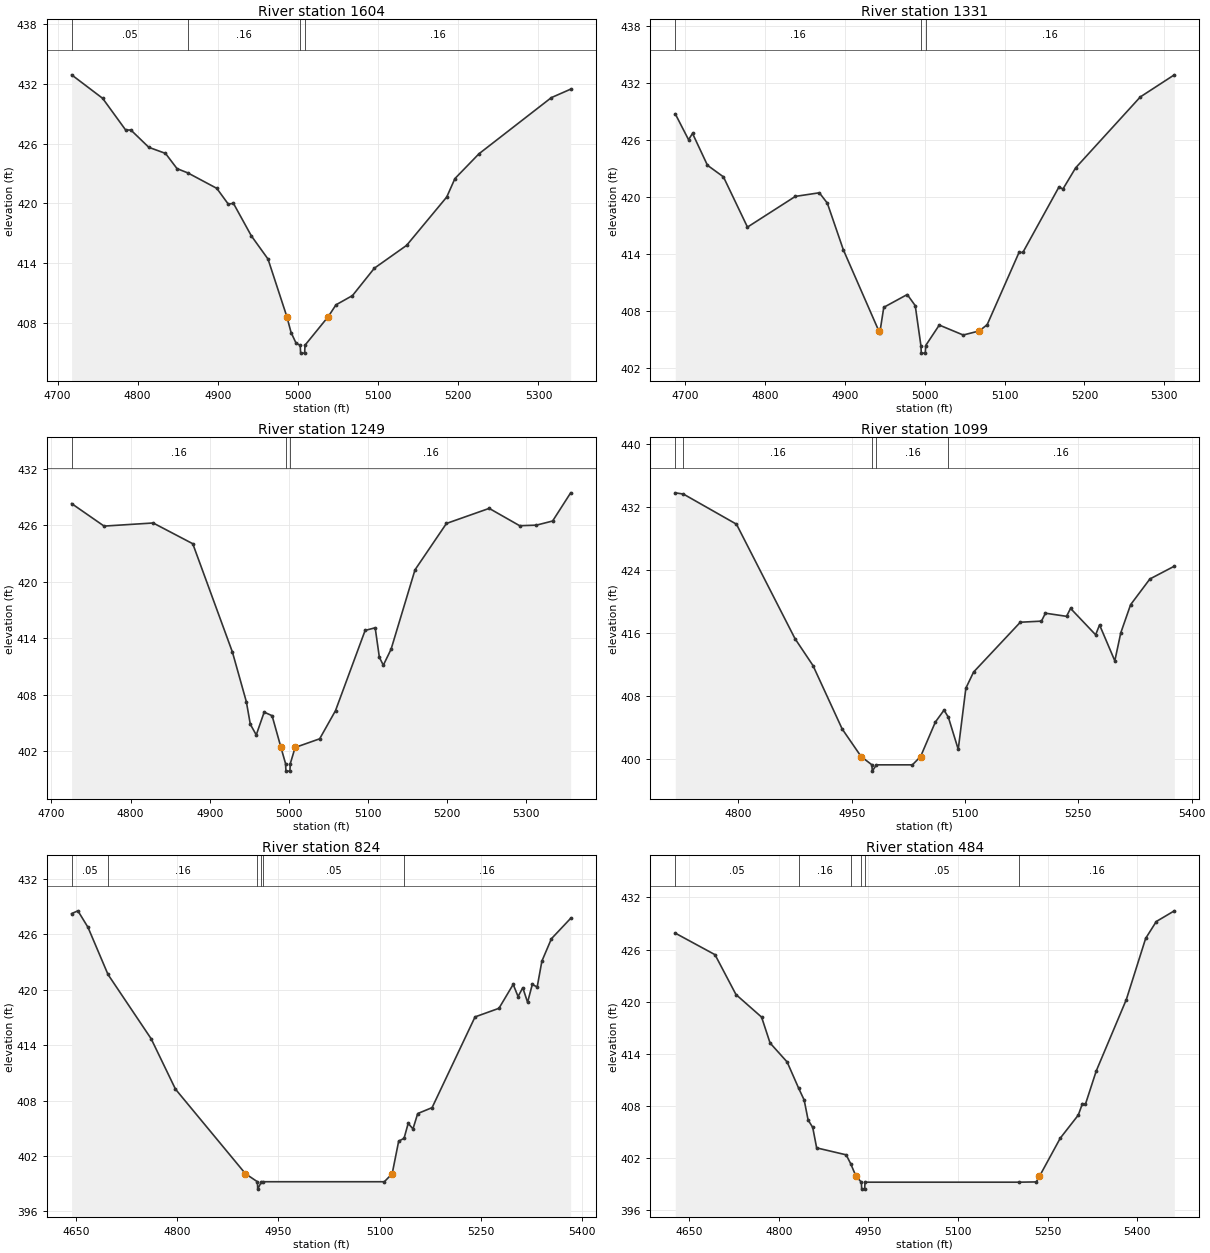
Type RM Length L Ch R = 1,1604,273,273,273
BEGIN DESCRIPTION:
UNT 111 in Running Cr Watershed 4.0
END DESCRIPTION:
XS GIS Cut Line= 3
      2886421.54      7007526.80      2886150.70      7007745.56
      2886127.26      7008019.00
#Sta/Elev= 30
  4717.6  432.90  4756.3  430.54  4785.1  427.35  4791.5  427.36  4813.9  425.62
  4834.7  425.01  4849.1  423.48  4862.6  423.05  4898.7  421.50  4913.0  419.92
  4919.5  419.99  4941.8  416.73  4962.6  414.40  4986.1  408.62  4991.4  407.02
  4997.8  405.92  5002.8  405.75  5003.3  404.95  5008.3  404.95  5008.8  405.75
  5037.8  408.62  5047.4  409.80  5068.0  410.73  5095.3  413.48  5135.5  415.77
  5185.6  420.63  5195.8  422.48  5225.8  424.97  5316.1  430.61  5340.2  431.46
#Mann=4,-1,0
  4717.6    0.05       0  4862.6    0.16       0  5002.8    0.07       0
  5008.8    0.16       0
Bank Sta=4986.1,5037.8
Exp/Cntr=0.3,0.1

Type RM Length L Ch R = 1,1331,82,82,82
BEGIN DESCRIPTION:
Mapping XS 84bbb068
END DESCRIPTION:
XS GIS Cut Line= 3
      2885960.75      7007374.72      2885942.52      7007809.62
      2885971.17      7007997.16
#Sta/Elev= 30
  4687.6  428.76  4704.2  426.04  4709.2  426.70  4727.9  423.34  4747.9  422.12
  4778.0  416.82  4838.0  420.06  4868.0  420.44  4878.0  419.35  4898.1  414.42
  4942.5  405.87  4943.7  405.66  4948.7  408.36  4978.1  409.71  4988.1  408.54
  4995.2  404.33  4995.7  403.53  5000.7  403.53  5001.2  404.33  5018.2  406.49
  5048.2  405.44  5068.3  405.87  5078.2  406.53  5118.1  414.15  5122.9  414.15
  5168.1  421.05  5173.1  420.84  5189.0  423.07  5270.0  430.55  5312.6  432.88
#Mann=3,-1,0
  4687.6    0.16       0  4995.2    0.07       0  5001.2    0.16       0
Bank Sta=4942.5,5068.3
Exp/Cntr=0.3,0.1

Type RM Length L Ch R = 1,1249,150,150,150
BEGIN DESCRIPTION:
Mapping XS 7a078202
END DESCRIPTION:
XS GIS Cut Line= 4
      2885882.47      7007412.20      2885861.63      7007784.62
      2885853.82      7007860.14      2885892.89      7008037.25
#Sta/Elev= 30
  4725.6  428.30  4766.6  425.91  4828.6  426.24  4878.6  424.04  4928.7  412.54
  4946.3  407.27  4951.3  404.88  4958.8  403.75  4968.8  406.17  4978.8  405.79
  4990.0  402.42  4995.8  400.71  4996.3  399.91  5001.3  399.91  5001.8  400.71
  5007.9  402.42  5038.9  403.34  5058.9  406.33  5096.3  414.84  5109.0  415.12
  5114.3  411.98  5119.3  411.15  5129.1  412.85  5159.3  421.27  5199.0  426.19
  5253.0  427.79  5291.5  425.95  5312.6  426.01  5333.1  426.45  5355.9  429.44
#Mann=3,-1,0
  4725.6    0.16       0  4995.8    0.07       0  5001.8    0.16       0
Bank Sta=4990,5007.9
Exp/Cntr=0.3,0.1

Type RM Length L Ch R = 1,1099,275,275,275
BEGIN DESCRIPTION:
UNT 111 in Running Cr Watershed 3.0
END DESCRIPTION:
XS GIS Cut Line= 3
      2885675.00      7007424.97      2885740.04      7007836.21
      2885809.38      7008070.52
#Sta/Elev= 30
  4716.4  433.81  4727.2  433.65  4797.4  429.82  4874.9  415.26  4898.7  411.84
  4937.3  403.78  4962.4  400.27  4976.7  399.21  4977.2  398.41  4982.7  399.21
  5030.3  399.21  5041.2  400.27  5060.7  404.65  5072.2  406.17  5077.9  405.27
  5091.0  401.18  5101.1  408.96  5111.3  411.01  5173.2  417.35  5201.2  417.49
  5206.4  418.50  5234.4  418.10  5239.7  419.11  5272.9  415.75  5278.1  417.01
  5298.3  412.44  5306.2  416.00  5319.2  419.58  5344.7  422.85  5377.1  424.48
#Mann=5,-1,0
  4716.4    0.05       0  4727.2    0.16       0  4976.7   0.033       0
  4982.7    0.16       0  5077.9    0.16       0
Bank Sta=4962.4,5041.2
Exp/Cntr=0.3,0.1

Type RM Length L Ch R = 1,824,340,340,340
BEGIN DESCRIPTION:
Mapping XS df80e110
END DESCRIPTION:
XS GIS Cut Line= 3
      2885351.22      7007516.39      2885507.47      7007888.79
      2885747.04      7008123.16
#Sta/Elev= 30
  4643.7  428.23  4653.0  428.53  4667.9  426.75  4697.6  421.64  4761.5  414.68
  4797.5  409.23  4901.1  400.08  4918.8  399.21  4919.3  398.41  4924.8  399.21
  4927.5  399.21  5106.8  399.21  5118.4  400.08  5128.0  403.60  5136.0  403.91
  5142.1  405.53  5149.2  404.93  5156.2  406.59  5177.5  407.23  5241.1  417.05
  5276.5  417.98  5297.6  420.57  5304.8  419.25  5311.8  420.21  5318.9  418.63
  5325.9  420.57  5333.1  420.28  5340.1  423.09  5354.2  425.51  5382.7  427.72
#Mann=6,-1,0
  4643.7    0.05       0  4697.6    0.16       0  4918.8   0.033       0
  4924.8    0.16       0  4927.5    0.05       0  5136.0    0.16       0
Bank Sta=4901.1,5118.4
Exp/Cntr=0.3,0.1

Type RM Length L Ch R = 1,484,318,318,318
BEGIN DESCRIPTION:
UNT 111 in Running Cr Watershed 2.0
END DESCRIPTION:
XS GIS Cut Line= 3
      2884957.11      7007729.05      2885265.28      7008089.31
      2885625.03      7008125.00
#Sta/Elev= 30
  4626.7  427.89  4693.2  425.41  4728.3  420.82  4771.2  418.22  4785.4  415.24
  4814.0  413.05  4833.2  410.04  4842.5  408.67  4849.1  406.37  4856.8  405.52
  4863.4  403.16  4912.8  402.36  4920.3  401.35  4929.3  399.89  4938.3  399.21
  4938.8  398.41  4943.8  398.41  4944.3  399.21  5202.1  399.21  5231.1  399.24
  5236.5  399.89  5271.3  404.28  5301.5  406.94  5308.4  408.26  5313.5  408.20
  5331.6  412.03  5381.9  420.24  5414.3  427.29  5432.1  429.23  5462.3  430.46
#Mann=6,-1,0
  4626.7    0.05       0  4833.2    0.16       0  4920.3    0.05       0
  4938.3   0.033       0  4944.3    0.05       0  5202.1    0.16       0
Bank Sta=4929.3,5236.5
Exp/Cntr=0.3,0.1

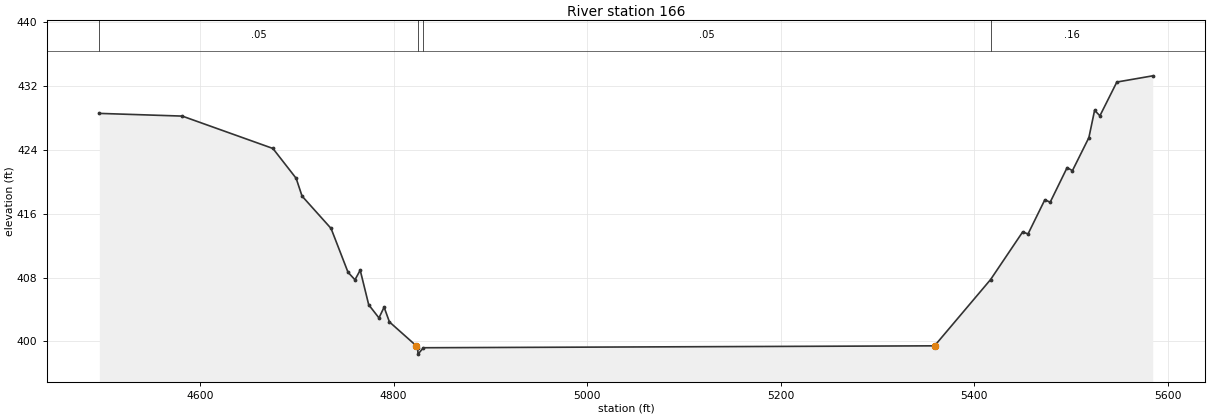
Type RM Length L Ch R = 1,166,0,0,0
BEGIN DESCRIPTION:
UNT 111 in Running Cr Watershed 1.0
END DESCRIPTION:
XS GIS Cut Line= 4
      2884874.98      7007874.96      2885026.56      7008271.60
      2885208.86      7008367.09      2885624.96      7008175.02
#Sta/Elev= 30
  4495.8  428.60  4581.5  428.26  4675.2  424.20  4699.2  420.46  4705.3  418.23
  4735.3  414.17  4752.8  408.68  4760.0  407.73  4765.4  408.94  4774.2  404.60
  4784.8  402.95  4790.1  404.30  4795.6  402.45  4823.4  399.45  4824.7  399.21
  4825.2  398.41  4830.7  399.21  5359.0  399.45  5416.9  407.76  5450.1  413.74
  5455.6  413.48  5473.0  417.77  5478.5  417.46  5496.0  421.80  5501.5  421.42
  5518.5  425.56  5524.4  428.98  5529.9  428.30  5547.4  432.53  5584.5  433.31
#Mann=4,-1,0
  4495.8    0.05       0  4824.7   0.033       0  4830.7    0.05       0
  5416.9    0.16       0
Bank Sta=4823.4,5359
Exp/Cntr=0.3,0.1

Chan Stop Cuts=-1