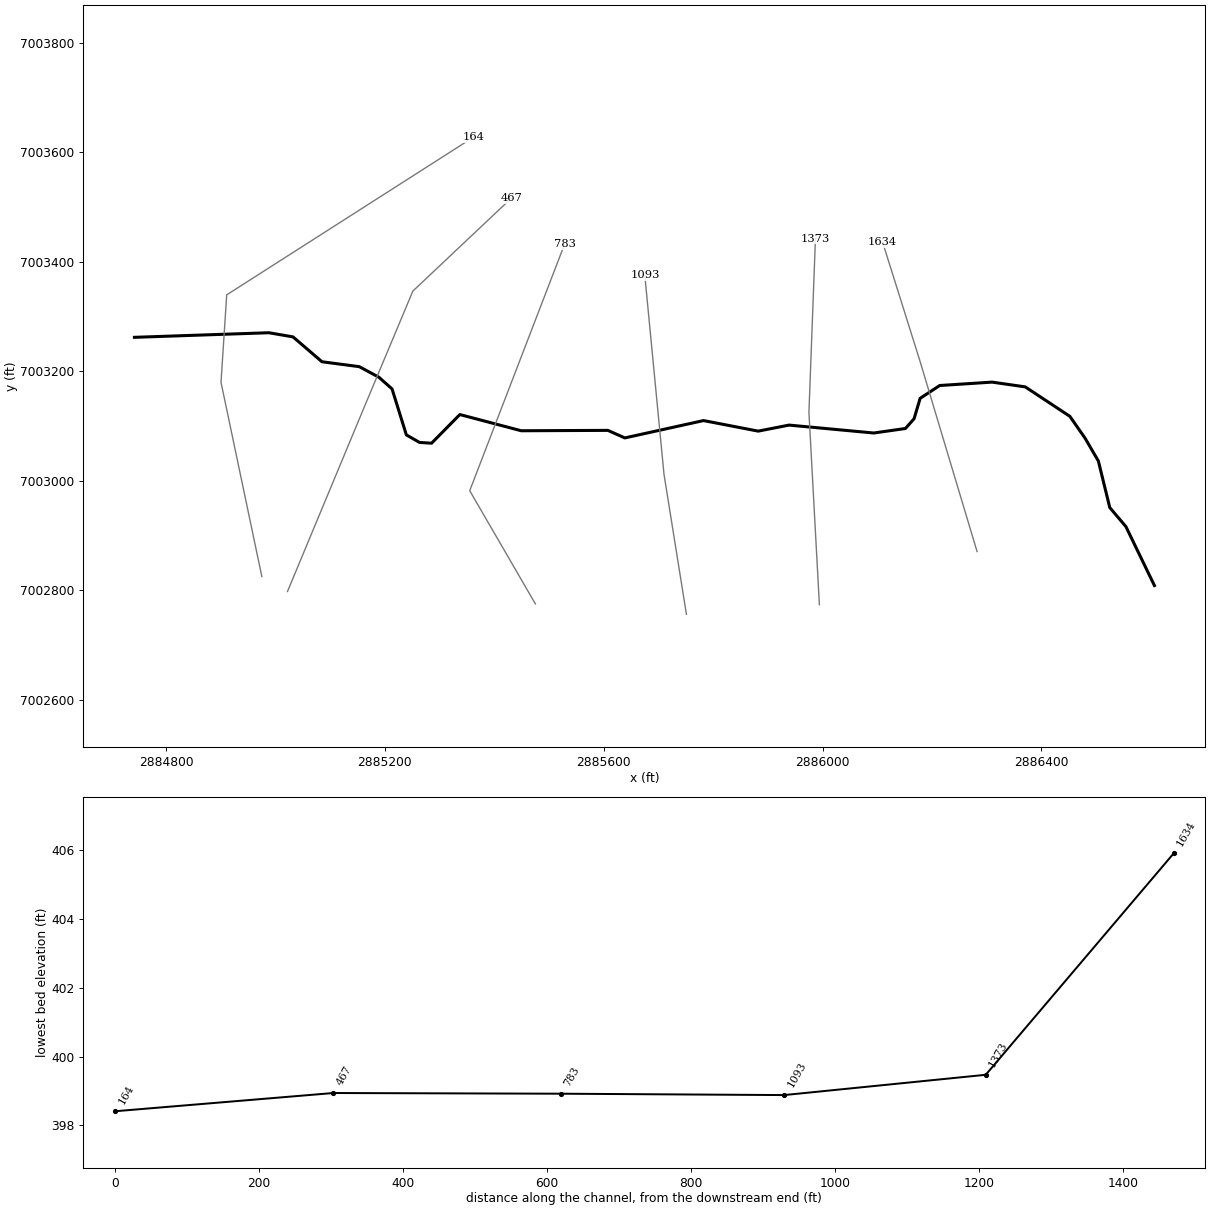
--- UNT 112 in Running Cr Watershed.prj (project) ---

Proj Title=UNT 112 in Running Cr Watershed Base Level Engineering
Current Plan=p01
Default Exp/Contr=0.3,0.1
English Units
Geom File=g01
Flow File=f01
Plan File=p01
BEGIN DESCRIPTION:
UNT 112 in Running Cr Watershed
END DESCRIPTION:

--- UNT 112 in Running Cr Watershed.p01 (plan) ---

Plan Title=Multiple Run
Short Identifier=Multiple
Geom File=g01
Flow File=f01
Subcritical Flow
K Sum by GR= 0
Std Step Tol= 0.01
Critical Tol= 0.01
Num of Std Step Trials= 20
Max Error Tol= 0.3
Flow Tol Ratio= 0.001
Split Flow NTrial= 30
Split Flow Tol= 0.02
Split Flow Ratio= 0.02
Log Output Level= 0
Friction Slope Method= 1
Unsteady Friction Slope Method= 2
Unsteady Bridges Friction Slope Method= 1
Parabolic Critical Depth
Global Vel Dist=  1 , 1 , 1
Global Log Level= 0
CheckData=True
Encroach Param= -1, 0, 0, 0
BEGIN DESCRIPTION:
Multiple Run
END DESCRIPTION:

--- UNT 112 in Running Cr Watershed.f01 (steady flow) ---

Flow Title=Multiple
Number of Profiles=7
Profile Names=10-year,25-year,50-year,1pct_min,100-year,1pct_plu,500-year
River Rch & RM= UNT 112 in Runni,Reach-1,1634
     248     317     370     216     432     861     586
Boundary for River Rch & Prof#=UNT 112 in Runni,Reach-1,1
Up Type=0
Dn Type=3
Dn Slope=0.005
Boundary for River Rch & Prof#=UNT 112 in Runni,Reach-1,2
Up Type=0
Dn Type=3
Dn Slope=0.005
Boundary for River Rch & Prof#=UNT 112 in Runni,Reach-1,3
Up Type=0
Dn Type=3
Dn Slope=0.005
Boundary for River Rch & Prof#=UNT 112 in Runni,Reach-1,4
Up Type=0
Dn Type=3
Dn Slope=0.005
Boundary for River Rch & Prof#=UNT 112 in Runni,Reach-1,5
Up Type=0
Dn Type=3
Dn Slope=0.005
Boundary for River Rch & Prof#=UNT 112 in Runni,Reach-1,6
Up Type=0
Dn Type=3
Dn Slope=0.005
Boundary for River Rch & Prof#=UNT 112 in Runni,Reach-1,7
Up Type=0
Dn Type=3
Dn Slope=0.005

--- UNT 112 in Running Cr Watershed.g01 (geometry) ---

Geom Title=Existing Conditions

River Reach=UNT 112 in Runni,Reach-1
Reach XY= 30
      2886606.49      7002808.49      2886554.41      7002916.13
      2886524.90      7002950.86      2886504.06      7003035.92
      2886479.76      7003077.59      2886451.98      7003117.52
      2886370.38      7003171.34      2886309.76      7003180.03
      2886214.06      7003173.83      2886178.26      7003150.42
      2886167.25      7003113.25      2886151.41      7003095.35
      2886093.58      7003087.08      2885938.67      7003101.54
      2885882.21      7003090.53      2885782.38      7003109.80
      2885638.49      7003078.13      2885607.51      7003091.90
      2885449.15      7003091.21      2885336.93      7003120.82
      2885285.29      7003068.49      2885263.26      7003069.87
      2885239.17      7003083.64      2885213.00      7003167.64
      2885188.91      7003188.98      2885153.11      7003208.26
      2885084.95      7003217.21      2885031.93      7003262.65
      2884987.87      7003270.22      2884742.10      7003261.84

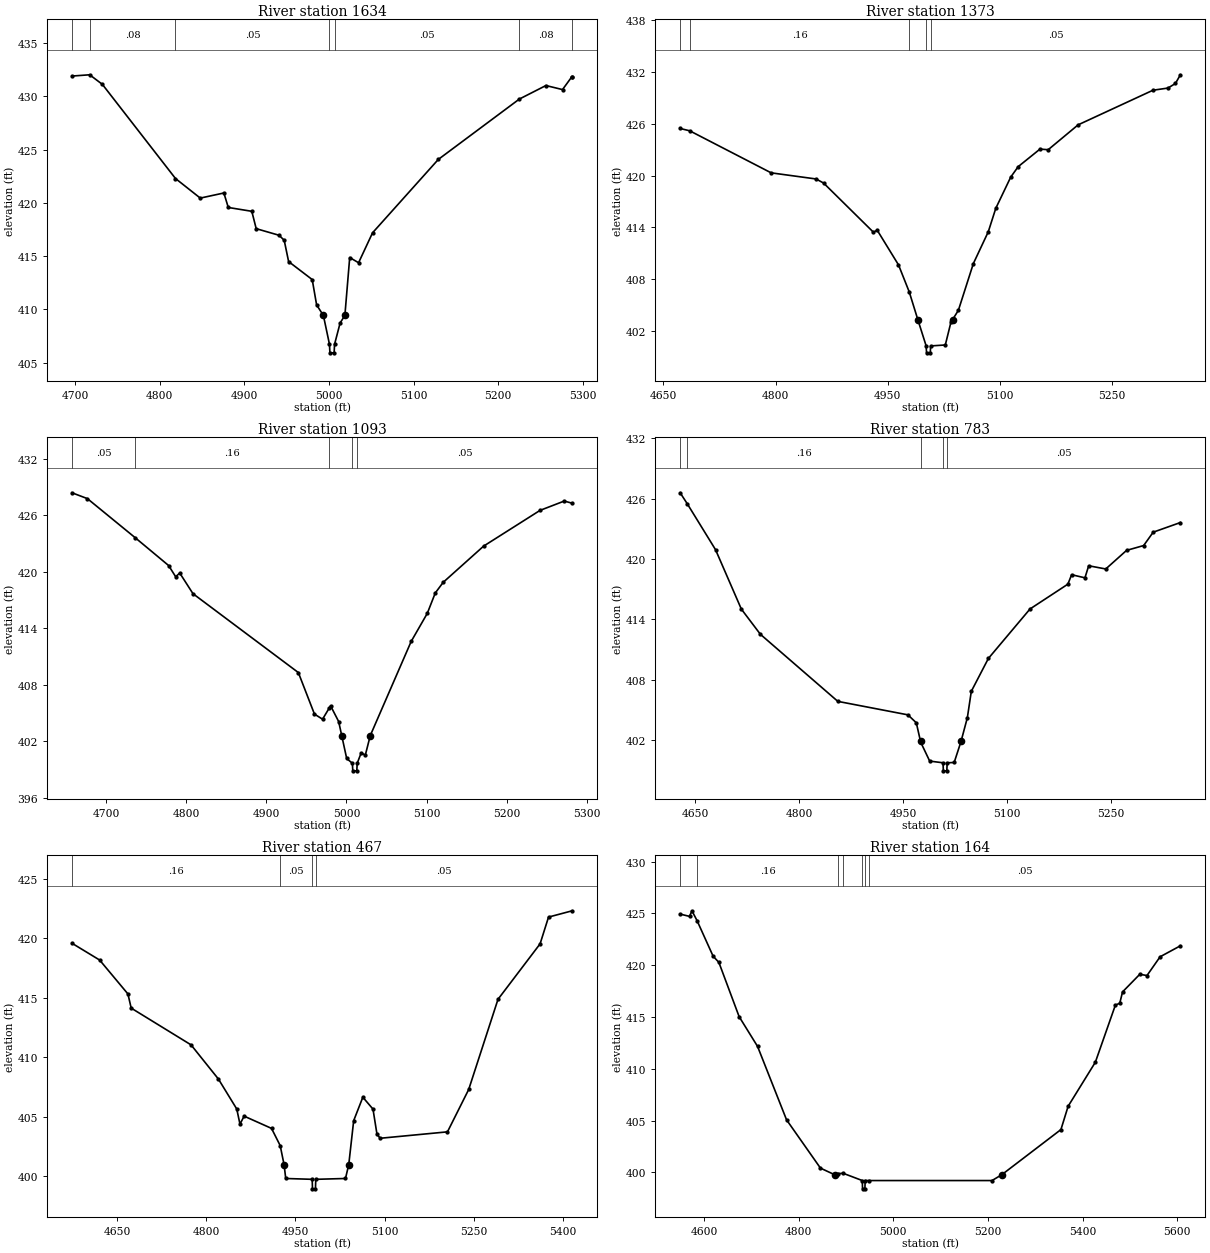
Type RM Length L Ch R = 1,1634,261,261,261
BEGIN DESCRIPTION:
UNT 112 in Running Cr Watershed 5.0
END DESCRIPTION:
XS GIS Cut Line= 3
      2886282.32      7002870.62      2886178.15      7003217.85
      2886109.54      7003436.00
#Sta/Elev= 30
  4696.4  431.90  4717.3  432.02  4732.3  431.12  4818.7  422.28  4848.0  420.44
  4875.9  420.92  4881.1  419.56  4908.9  419.20  4914.1  417.57  4941.1  416.95
  4947.2  416.48  4952.4  414.48  4980.3  412.79  4985.5  410.41  4993.5  409.42
  5000.7  406.71  5001.2  405.91  5006.2  405.91  5006.7  406.71  5013.3  408.72
  5018.9  409.42  5024.6  414.86  5035.1  414.37  5051.6  417.18  5129.3  424.07
  5225.1  429.74  5256.5  431.01  5276.1  430.63  5287.1  431.83  5287.6  431.83
#Mann=7,-1,0
  4696.4     0.1       0  4717.3    0.08       0  4818.7    0.05       0
  5000.7    0.03       0  5006.7    0.05       0  5225.1    0.08       0
  5287.1    0.05       0
Bank Sta=4993.5,5018.9
Exp/Cntr=0.3,0.1

Type RM Length L Ch R = 1,1373,280,280,280
BEGIN DESCRIPTION:
UNT 112 in Running Cr Watershed 4.0
END DESCRIPTION:
XS GIS Cut Line= 3
      2885994.12      7002773.44      2885975.00      7003125.00
      2885986.90      7003441.70
#Sta/Elev= 30
  4672.4  425.46  4685.2  425.19  4794.1  420.32  4854.2  419.61  4864.2  419.14
  4930.9  413.44  4935.9  413.68  4964.4  409.66  4978.8  406.52  4990.2  403.33
  5001.4  400.27  5001.9  399.47  5006.9  399.47  5007.4  400.27  5027.0  400.38
  5034.5  403.01  5036.8  403.33  5044.5  404.40  5064.5  409.81  5084.5  413.50
  5094.5  416.21  5114.5  419.83  5124.5  421.04  5153.6  423.07  5164.6  423.00
  5204.6  425.88  5304.7  429.89  5324.7  430.14  5334.7  430.67  5341.4  431.68
#Mann=5,-1,0
  4672.4    0.05       0  4685.2    0.16       0  4978.8    0.05       0
  5001.4   0.035       0  5007.4    0.05       0
Bank Sta=4990.2,5036.8
Exp/Cntr=0.3,0.1

Type RM Length L Ch R = 1,1093,310,310,310
BEGIN DESCRIPTION:
UNT 112 in Running Cr Watershed 3.0
END DESCRIPTION:
XS GIS Cut Line= 3
      2885751.07      7002756.04      2885710.07      7003011.76
      2885675.00      7003374.98
#Sta/Elev= 30
  4657.7  428.39  4676.9  427.77  4736.7  423.61  4778.2  420.67  4787.0  419.48
  4792.1  419.87  4808.6  417.68  4940.0  409.31  4960.1  404.90  4970.2  404.36
  4978.2  405.50  4980.2  405.78  4990.3  404.11  4994.1  402.62  5000.3  400.19
  5007.4  399.68  5007.9  398.88  5012.9  398.88  5013.4  399.68  5018.4  400.79
  5023.5  400.54  5029.7  402.62  5080.7  412.61  5100.8  415.59  5110.8  417.76
  5120.7  418.89  5171.1  422.73  5241.4  426.52  5271.6  427.51  5281.6  427.28
#Mann=5,-1,0
  4657.7    0.05       0  4736.7    0.16       0  4978.2    0.05       0
  5007.4   0.035       0  5013.4    0.05       0
Bank Sta=4994.1,5029.7
Exp/Cntr=0.3,0.1

Type RM Length L Ch R = 1,783,316,316,316
BEGIN DESCRIPTION:
UNT 112 in Running Cr Watershed 2.0
END DESCRIPTION:
XS GIS Cut Line= 3
      2885475.02      7002774.97      2885354.99      7002981.71
      2885528.23      7003431.54
#Sta/Elev= 30
  4628.7  426.58  4639.1  425.47  4679.7  420.92  4716.9  415.01  4744.4  412.50
  4856.0  405.83  4957.0  404.49  4969.1  403.70  4975.2  401.85  4975.5  401.76
  4988.4  399.89  5007.6  399.72  5008.1  398.92  5013.1  398.92  5013.6  399.72
  5023.7  399.75  5033.6  401.85  5042.7  404.21  5048.4  406.83  5073.0  410.10
  5133.0  415.02  5187.6  417.49  5193.0  418.43  5212.2  418.12  5217.6  419.32
  5242.2  419.00  5272.2  420.85  5296.8  421.33  5310.6  422.66  5349.8  423.62
#Mann=5,-1,0
  4628.7    0.05       0  4639.1    0.16       0  4975.5    0.05       0
  5007.6   0.035       0  5013.6    0.05       0
Bank Sta=4975.2,5033.6
Exp/Cntr=0.3,0.1

Type RM Length L Ch R = 1,467,303,303,303
BEGIN DESCRIPTION:
Mapping XS eb442b07
END DESCRIPTION:
XS GIS Cut Line= 4
      2885021.88      7002797.67      2885160.79      7003131.05
      2885251.07      7003346.32      2885430.83      7003515.72
#Sta/Elev= 30
  4574.2  419.58  4620.7  418.17  4668.3  415.32  4673.8  414.13  4774.5  411.04
  4820.5  408.17  4851.4  405.65  4856.8  404.38  4863.8  405.05  4909.9  404.02
  4924.5  402.57  4931.0  400.97  4933.8  399.81  4978.3  399.74  4978.8  398.94
  4983.8  398.94  4984.3  399.74  5034.3  399.81  5039.8  400.97  5048.1  404.67
  5063.5  406.64  5080.6  405.64  5087.3  403.53  5092.7  403.19  5205.9  403.73
  5241.6  407.29  5290.9  414.87  5361.7  419.53  5375.9  421.78  5415.8  422.31
#Mann=4,-1,0
  4574.2    0.16       0  4924.5    0.05       0  4978.3   0.035       0
  4984.3    0.05       0
Bank Sta=4931,5039.8
Exp/Cntr=0.3,0.1

Type RM Length L Ch R = 1,164,0,0,0
BEGIN DESCRIPTION:
UNT 112 in Running Cr Watershed 1.0
END DESCRIPTION:
XS GIS Cut Line= 4
      2884975.00      7002824.99      2884900.37      7003179.66
      2884910.79      7003339.38      2885361.13      7003626.90
#Sta/Elev= 30
  4549.6  424.93  4569.4  424.71  4574.5  425.25  4585.4  424.29  4619.2  420.87
  4631.4  420.27  4674.2  415.03  4713.1  412.16  4774.4  405.07  4846.0  400.41
  4876.1  399.77  4883.9  399.88  4894.0  399.91  4934.4  399.21  4934.9  398.41
  4939.9  398.41  4940.4  399.21  4949.4  399.21  5208.4  399.21  5229.0  399.77
  5354.0  404.13  5369.2  406.38  5426.7  410.63  5469.0  416.14  5478.3  416.33
  5484.2  417.42  5520.6  419.12  5535.8  419.00  5563.5  420.81  5606.4  421.87
#Mann=7,-1,0
  4549.6     0.1       0  4585.4    0.16       0  4883.9    0.05       0
  4894.0    0.07       0  4934.4   0.033       0  4940.4    0.07       0
  4949.4    0.05       0
Bank Sta=4876.1,5229
Exp/Cntr=0.3,0.1

Chan Stop Cuts=-1