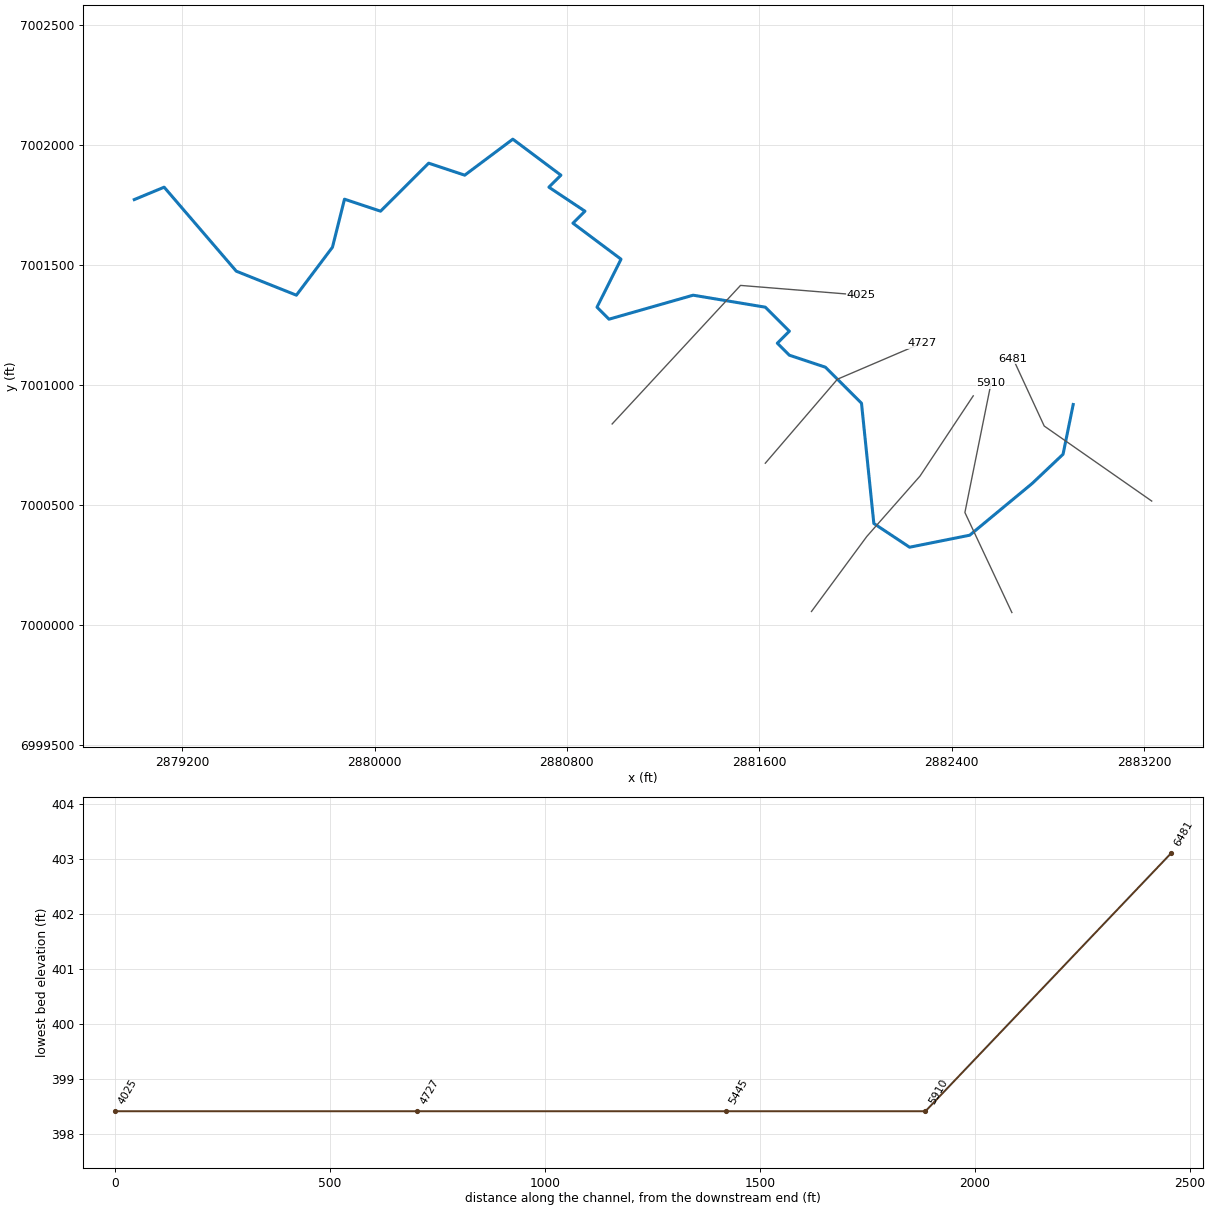
--- UNT 113 in Running Cr Watershed.prj (project) ---

Proj Title=UNT 113 in Running Cr Watershed Base Level Engineering
Current Plan=p01
Default Exp/Contr=0.3,0.1
English Units
Geom File=g01
Flow File=f01
Plan File=p01
BEGIN DESCRIPTION:
UNT 113 in Running Cr Watershed
END DESCRIPTION:

--- UNT 113 in Running Cr Watershed.p01 (plan) ---

Plan Title=Multiple Run
Short Identifier=Multiple
Geom File=g01
Flow File=f01
Subcritical Flow
K Sum by GR= 0
Std Step Tol= 0.01
Critical Tol= 0.01
Num of Std Step Trials= 20
Max Error Tol= 0.3
Flow Tol Ratio= 0.001
Split Flow NTrial= 30
Split Flow Tol= 0.02
Split Flow Ratio= 0.02
Log Output Level= 0
Friction Slope Method= 1
Unsteady Friction Slope Method= 2
Unsteady Bridges Friction Slope Method= 1
Parabolic Critical Depth
Global Vel Dist=  1 , 1 , 1
Global Log Level= 0
CheckData=True
Encroach Param= -1, 0, 0, 0
BEGIN DESCRIPTION:
Multiple Run
END DESCRIPTION:

--- UNT 113 in Running Cr Watershed.f01 (steady flow) ---

Flow Title=Multiple
Number of Profiles=7
Profile Names=10-year,25-year,50-year,1pct_min,100-year,1pct_plu,500-year
River Rch & RM= UNT 113 in Runni,Reach-1,6481
     235     292     334     191     381     760     493
Boundary for River Rch & Prof#=UNT 113 in Runni,Reach-1,1
Up Type=0
Dn Type=3
Dn Slope=0.005
Boundary for River Rch & Prof#=UNT 113 in Runni,Reach-1,2
Up Type=0
Dn Type=3
Dn Slope=0.005
Boundary for River Rch & Prof#=UNT 113 in Runni,Reach-1,3
Up Type=0
Dn Type=3
Dn Slope=0.005
Boundary for River Rch & Prof#=UNT 113 in Runni,Reach-1,4
Up Type=0
Dn Type=3
Dn Slope=0.005
Boundary for River Rch & Prof#=UNT 113 in Runni,Reach-1,5
Up Type=0
Dn Type=3
Dn Slope=0.005
Boundary for River Rch & Prof#=UNT 113 in Runni,Reach-1,6
Up Type=0
Dn Type=3
Dn Slope=0.005
Boundary for River Rch & Prof#=UNT 113 in Runni,Reach-1,7
Up Type=0
Dn Type=3
Dn Slope=0.005

--- UNT 113 in Running Cr Watershed.g01 (geometry) ---

Geom Title=Existing Conditions

River Reach=UNT 113 in Runni,Reach-1
Reach XY= 30
      2882905.41      7000919.56      2882863.22      7000712.27
      2882734.58      7000590.40      2882475.00      7000375.00
      2882225.00      7000325.00      2882076.33      7000423.86
      2882025.00      7000925.00      2881875.00      7001075.00
      2881725.00      7001125.00      2881675.00      7001175.00
      2881725.00      7001225.00      2881625.00      7001325.00
      2881325.00      7001375.00      2880975.00      7001275.00
      2880925.00      7001325.00      2881025.00      7001525.00
      2880825.00      7001675.00      2880875.00      7001725.00
      2880725.00      7001825.00      2880775.00      7001875.00
      2880575.00      7002025.00      2880375.00      7001875.00
      2880225.00      7001925.00      2880025.00      7001725.00
      2879875.00      7001775.00      2879825.00      7001575.00
      2879675.00      7001375.00      2879425.00      7001475.00
      2879125.00      7001825.00      2879000.80      7001773.33

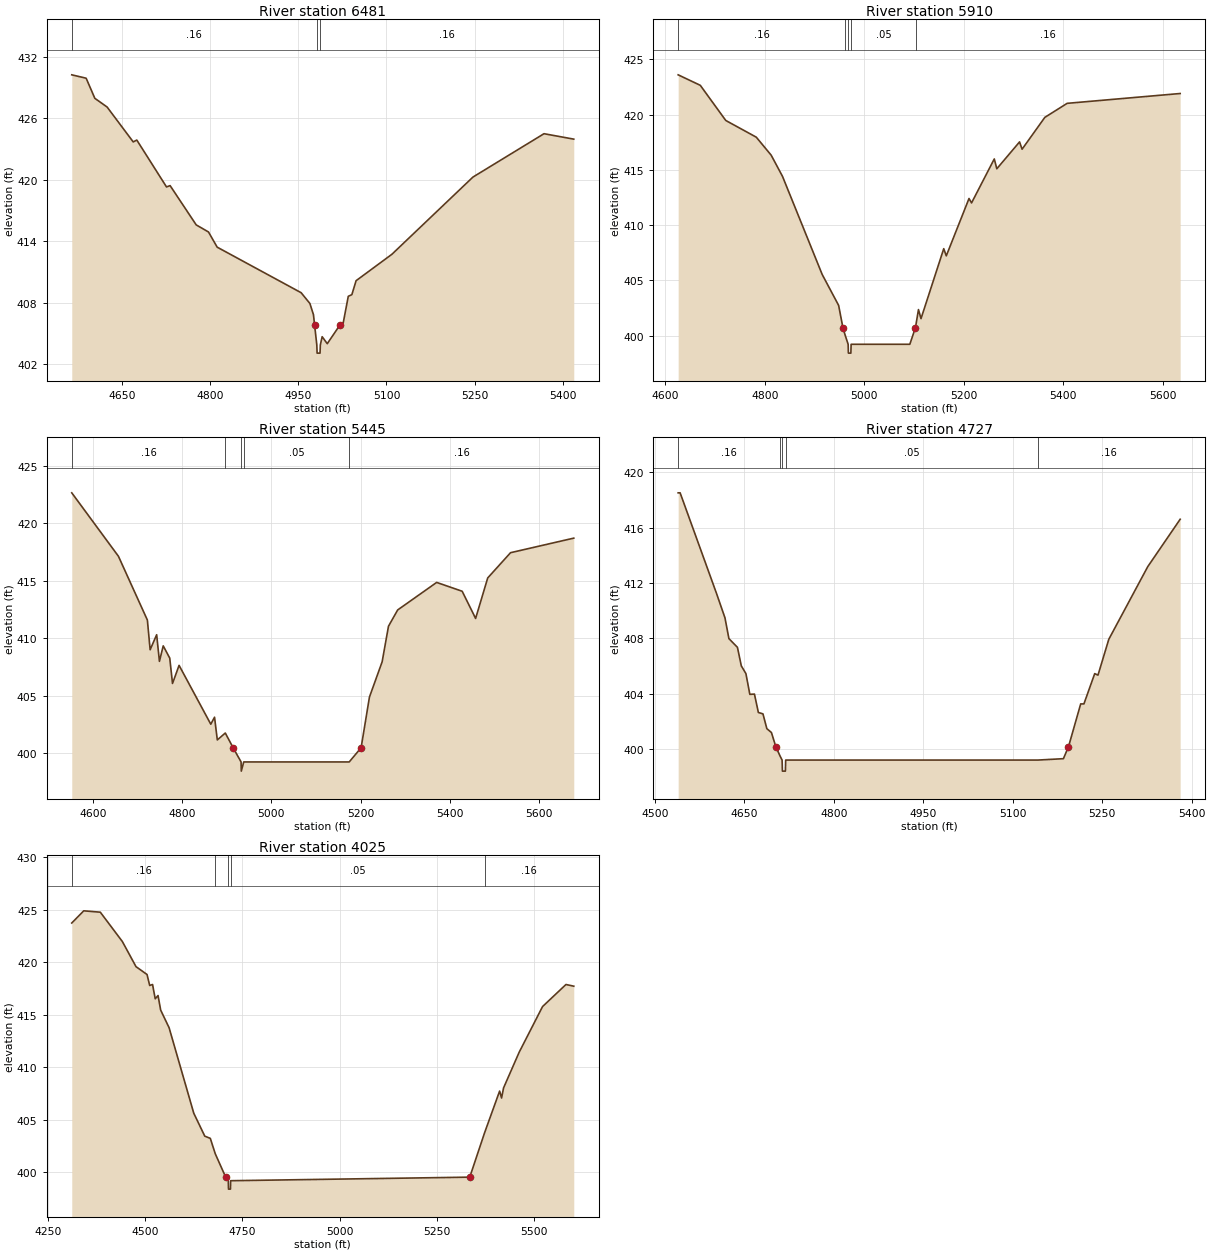
Type RM Length L Ch R = 1,6481,571,571,571
BEGIN DESCRIPTION:
UNT 113 in Running Cr Watershed 3.0
END DESCRIPTION:
XS GIS Cut Line= 3
      2883231.96      7000517.33      2882784.92      7000829.83
      2882655.15      7001110.99
#Sta/Elev= 30
  4564.0  430.23  4588.5  429.90  4603.3  427.94  4624.2  427.09  4668.7  423.69
  4674.8  423.87  4725.4  419.30  4731.5  419.43  4776.0  415.60  4796.9  414.91
  4811.7  413.43  4954.7  408.99  4969.6  407.94  4975.7  406.85  4977.7  405.80
  4981.4  403.90  4981.9  403.10  4986.9  403.10  4987.4  403.90  4990.5  404.70
  4999.2  404.02  5020.3  405.80  5026.2  405.99  5035.0  408.64  5041.1  408.80
  5048.3  410.16  5109.4  412.74  5247.3  420.26  5368.4  424.49  5419.1  423.96
#Mann=3,-1,0
  4564.0    0.16       0  4981.4    0.07       0  4987.4    0.16       0
Bank Sta=4977.7,5020.3
Exp/Cntr=0.3,0.1

Type RM Length L Ch R = 1,5910,465,465,465
BEGIN DESCRIPTION:
Mapping XS 6371652c
END DESCRIPTION:
XS GIS Cut Line= 3
      2882650.39      7000052.88      2882455.06      7000469.59
      2882563.56      7001007.74
#Sta/Elev= 30
  4625.9  423.59  4670.4  422.64  4721.6  419.46  4782.9  417.95  4812.9  416.32
  4835.7  414.40  4915.4  405.53  4948.5  402.73  4957.1  400.71  4961.1  400.11
  4967.6  399.21  4968.1  398.41  4973.1  398.41  4973.6  399.21  5091.6  399.21
  5102.9  400.71  5103.5  400.87  5109.0  402.35  5114.1  401.53  5159.8  407.86
  5164.9  407.21  5210.6  412.40  5215.7  412.00  5261.4  415.98  5266.5  415.09
  5312.2  417.52  5317.3  416.86  5363.0  419.74  5407.9  421.01  5635.1  421.90
#Mann=5,-1,0
  4625.9    0.16       0  4961.1    0.05       0  4967.6   0.033       0
  4973.6    0.05       0  5103.5    0.16       0
Bank Sta=4957.1,5102.9
Exp/Cntr=0.3,0.1

Type RM Length L Ch R = 1,5445,718,718,718
BEGIN DESCRIPTION:
Mapping XS 3a6455a1
END DESCRIPTION:
XS GIS Cut Line= 4
      2881817.02      7000057.24      2882047.07      7000369.76
      2882268.43      7000621.50      2882489.76      7000955.67
#Sta/Elev= 30
  4553.1  422.67  4657.6  417.14  4722.4  411.58  4728.6  408.99  4743.2  410.30
  4749.4  407.98  4757.9  409.33  4772.5  408.26  4778.7  406.05  4793.4  407.63
  4864.4  402.50  4872.8  403.11  4879.0  401.13  4896.9  401.73  4914.4  400.45
  4932.2  399.21  4932.7  398.41  4938.2  399.21  5174.4  399.21  5201.0  400.45
  5219.7  404.87  5248.1  407.94  5262.3  411.04  5282.9  412.46  5370.2  414.86
  5427.3  414.09  5457.4  411.72  5484.5  415.25  5535.6  417.45  5677.2  418.72
#Mann=5,-1,0
  4553.1    0.16       0  4896.9    0.05       0  4932.2   0.033       0
  4938.2    0.05       0  5174.4    0.16       0
Bank Sta=4914.4,5201
Exp/Cntr=0.3,0.1

Type RM Length L Ch R = 1,4727,702,702,702
BEGIN DESCRIPTION:
UNT 113 in Running Cr Watershed 2.0
END DESCRIPTION:
XS GIS Cut Line= 3
      2881624.99      7000674.98      2881925.00      7001025.00
      2882275.01      7001175.00
#Sta/Elev= 30
  4539.0  418.53  4542.3  418.53  4603.2  411.27  4617.5  409.49  4624.1  407.99
  4638.4  407.36  4644.9  406.02  4652.6  405.46  4659.2  403.96  4666.9  403.98
  4673.5  402.65  4681.2  402.55  4687.7  401.48  4695.4  401.20  4702.8  400.17
  4710.0  399.49  4713.3  399.21  4713.8  398.41  4718.8  398.41  4719.3  399.21
  5142.3  399.21  5185.0  399.31  5193.5  400.17  5214.0  403.27  5219.4  403.27
  5237.5  405.46  5243.0  405.35  5261.1  407.94  5326.4  413.19  5380.8  416.62
#Mann=5,-1,0
  4539.0    0.16       0  4710.0    0.05       0  4713.3   0.033       0
  4719.3    0.05       0  5142.3    0.16       0
Bank Sta=4702.8,5193.5
Exp/Cntr=0.3,0.1

Type RM Length L Ch R = 1,4025,0,0,0
BEGIN DESCRIPTION:
UNT 113 in Running Cr Watershed 1.0
END DESCRIPTION:
XS GIS Cut Line= 3
      2880988.01      7000838.48      2881521.90      7001415.77
      2882025.03      7001375.00
#Sta/Elev= 30
  4311.1  423.73  4341.9  424.89  4384.5  424.76  4441.2  421.97  4476.3  419.58
  4504.7  418.83  4511.5  417.79  4518.9  417.88  4525.7  416.52  4533.0  416.83
  4539.8  415.44  4561.4  413.77  4624.9  405.63  4653.2  403.45  4667.4  403.24
  4680.2  401.77  4707.0  399.55  4713.7  399.21  4714.2  398.41  4719.2  398.41
  4719.7  399.21  5334.7  399.55  5372.7  403.76  5411.5  407.74  5416.5  407.08
  5421.6  408.04  5461.7  411.43  5521.9  415.78  5582.1  417.88  5602.2  417.72
#Mann=5,-1,0
  4311.1    0.16       0  4680.2    0.05       0  4713.7   0.033       0
  4719.7    0.05       0  5372.7    0.16       0
Bank Sta=4707,5334.7
Exp/Cntr=0.3,0.1

Chan Stop Cuts=-1