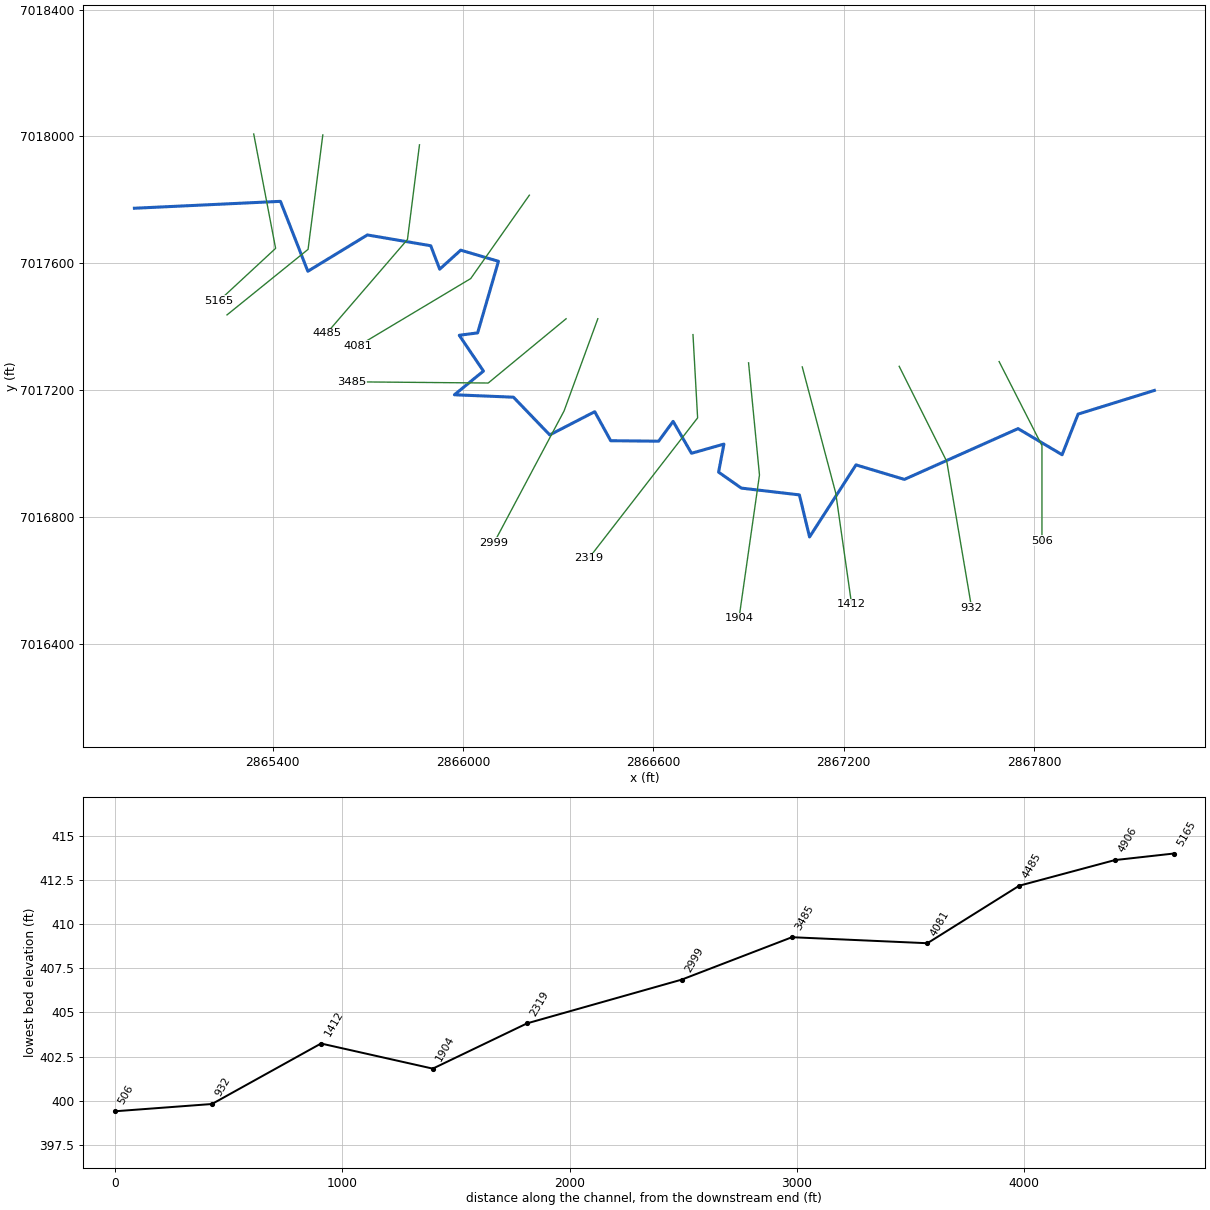
--- UNT 114 in Running Cr Watershed.prj (project) ---

Proj Title=UNT 114 in Running Cr Watershed Base Level Engineering
Current Plan=p01
Default Exp/Contr=0.3,0.1
English Units
Geom File=g01
Flow File=f01
Plan File=p01
BEGIN DESCRIPTION:
UNT 114 in Running Cr Watershed
END DESCRIPTION:

--- UNT 114 in Running Cr Watershed.p01 (plan) ---

Plan Title=Multiple Run
Short Identifier=Multiple
Geom File=g01
Flow File=f01
Subcritical Flow
K Sum by GR= 0
Std Step Tol= 0.01
Critical Tol= 0.01
Num of Std Step Trials= 20
Max Error Tol= 0.3
Flow Tol Ratio= 0.001
Split Flow NTrial= 30
Split Flow Tol= 0.02
Split Flow Ratio= 0.02
Log Output Level= 0
Friction Slope Method= 1
Unsteady Friction Slope Method= 2
Unsteady Bridges Friction Slope Method= 1
Parabolic Critical Depth
Global Vel Dist=  1 , 1 , 1
Global Log Level= 0
CheckData=True
Encroach Param= -1, 0, 0, 0
BEGIN DESCRIPTION:
Multiple Run
END DESCRIPTION:

--- UNT 114 in Running Cr Watershed.f01 (steady flow) ---

Flow Title=Multiple
Number of Profiles=7
Profile Names=10-year,25-year,50-year,1pct_min,100-year,1pct_plu,500-year
River Rch & RM= UNT 114 in Runni,Reach-1,5165
     509     675     809     482     962    1919    1362
Boundary for River Rch & Prof#=UNT 114 in Runni,Reach-1,1
Up Type=0
Dn Type=3
Dn Slope=0.005
Boundary for River Rch & Prof#=UNT 114 in Runni,Reach-1,2
Up Type=0
Dn Type=3
Dn Slope=0.005
Boundary for River Rch & Prof#=UNT 114 in Runni,Reach-1,3
Up Type=0
Dn Type=3
Dn Slope=0.005
Boundary for River Rch & Prof#=UNT 114 in Runni,Reach-1,4
Up Type=0
Dn Type=3
Dn Slope=0.005
Boundary for River Rch & Prof#=UNT 114 in Runni,Reach-1,5
Up Type=0
Dn Type=3
Dn Slope=0.005
Boundary for River Rch & Prof#=UNT 114 in Runni,Reach-1,6
Up Type=0
Dn Type=3
Dn Slope=0.005
Boundary for River Rch & Prof#=UNT 114 in Runni,Reach-1,7
Up Type=0
Dn Type=3
Dn Slope=0.005

--- UNT 114 in Running Cr Watershed.g01 (geometry) ---

Geom Title=Existing Conditions

River Reach=UNT 114 in Runni,Reach-1
Reach XY= 30
      2864964.27      7017773.51      2865424.59      7017795.26
      2865510.92      7017574.74      2865698.59      7017689.29
      2865898.26      7017655.27      2865926.57      7017581.27
      2865992.81      7017641.29      2866111.77      7017606.21
      2866046.19      7017380.49      2865988.24      7017372.86
      2866064.49      7017260.01      2865972.99      7017185.27
      2866159.05      7017177.65      2866273.44      7017058.69
      2866415.27      7017131.90      2866465.60      7017040.39
      2866616.59      7017038.86      2866662.34      7017101.39
      2866720.30      7017000.74      2866822.48      7017029.71
      2866805.70      7016941.26      2866877.38      7016890.93
      2867060.40      7016869.57      2867092.43      7016736.89
      2867238.84      7016964.13      2867391.35      7016918.38
      2867749.75      7017078.52      2867888.54      7016996.16
      2867938.87      7017124.27      2868179.50      7017198.96

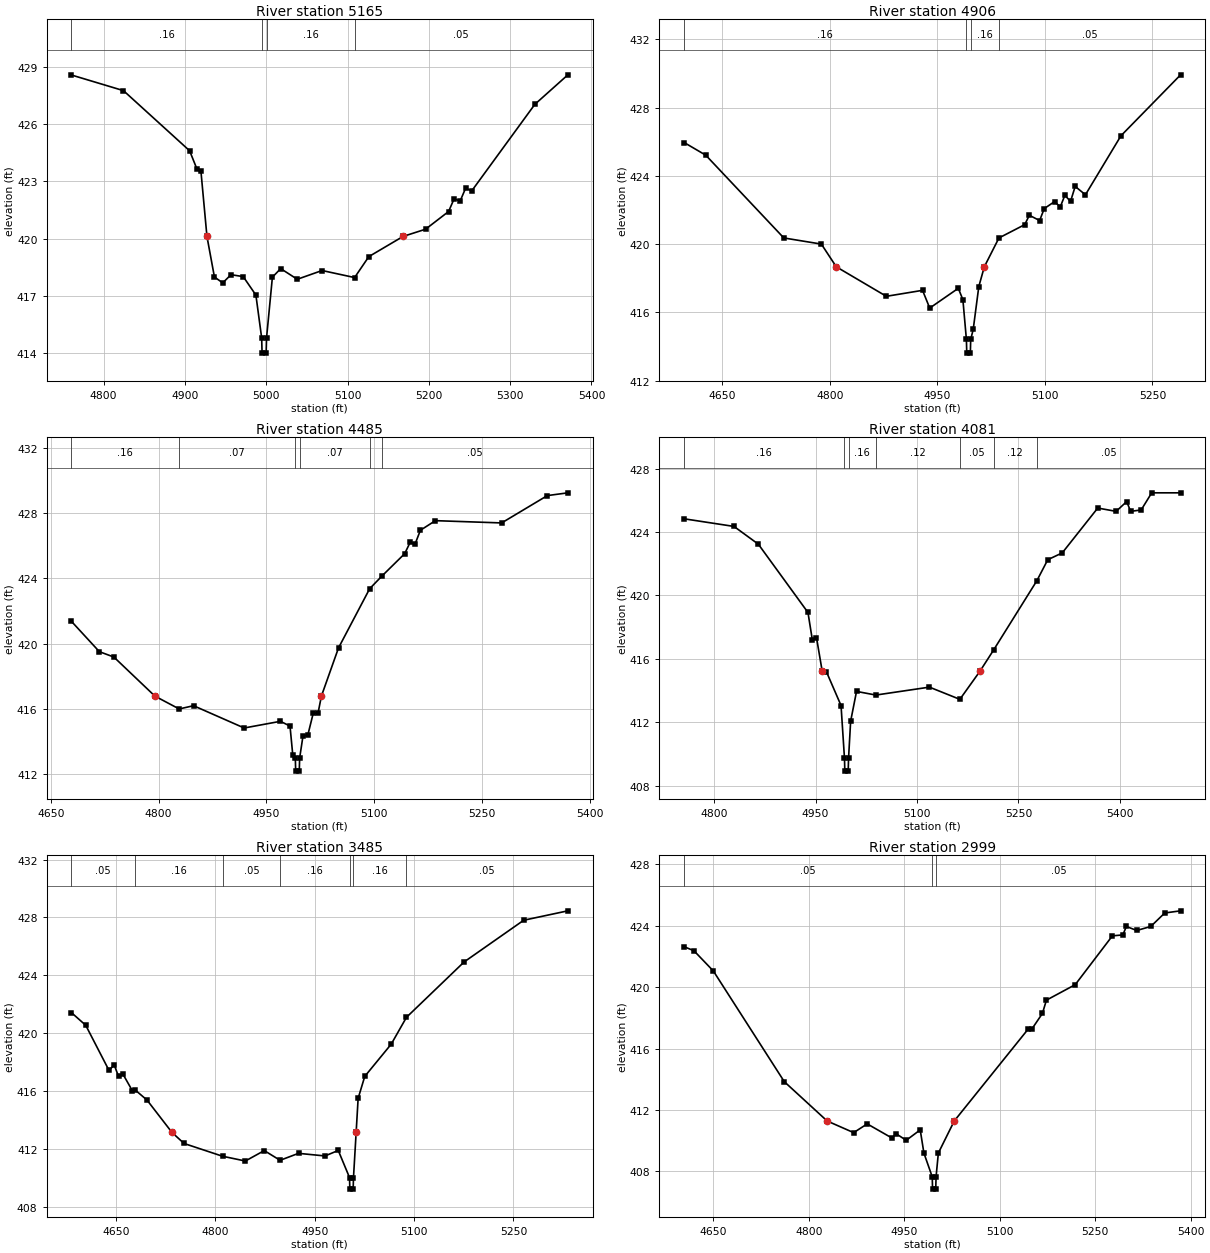
Type RM Length L Ch R = 1,5165,259,259,259
BEGIN DESCRIPTION:
UNT 114 in Running Cr Watershed 11.0
END DESCRIPTION:
XS GIS Cut Line= 3
      2865340.35      7018007.71      2865409.37      7017647.00
      2865230.99      7017481.63
#Sta/Elev= 30
  4760.5  428.59  4824.4  427.77  4905.8  424.61  4914.6  423.67  4919.7  423.54
  4927.1  420.11  4936.3  417.98  4946.5  417.67  4956.7  418.10  4971.7  418.00
  4987.3  417.03  4994.4  414.78  4994.9  413.98  4999.9  413.98  5000.4  414.78
  5007.6  417.97  5017.8  418.42  5038.2  417.86  5068.7  418.32  5108.7  417.95
  5126.2  419.05  5168.3  420.11  5196.0  420.49  5224.3  421.42  5231.1  422.09
  5238.5  421.97  5245.3  422.65  5252.7  422.50  5330.4  427.05  5371.0  428.60
#Mann=4,-1,0
  4760.5    0.16       0  4994.4    0.07       0  5000.4    0.16       0
  5108.7    0.05       0
Bank Sta=4927.1,5168.3
Exp/Cntr=0.3,0.1

Type RM Length L Ch R = 1,4906,421,421,421
BEGIN DESCRIPTION:
UNT 114 in Running Cr Watershed 10.0
END DESCRIPTION:
XS GIS Cut Line= 3
      2865558.16      7018004.83      2865511.64      7017643.84
      2865256.07      7017437.10
#Sta/Elev= 30
  4596.6  425.95  4626.7  425.21  4735.6  420.36  4788.0  420.00  4808.8  418.67
  4878.7  416.94  4929.2  417.29  4939.2  416.25  4979.1  417.41  4985.5  416.74
  4990.4  414.41  4990.9  413.61  4995.9  413.61  4996.4  414.41  4999.9  415.00
  5007.7  417.51  5015.4  418.67  5035.8  420.36  5071.8  421.14  5078.2  421.69
  5092.6  421.38  5099.0  422.08  5113.4  422.49  5121.4  422.18  5127.8  422.86
  5135.7  422.50  5142.2  423.38  5156.5  422.89  5206.1  426.35  5289.3  429.92
#Mann=4,-1,0
  4596.6    0.16       0  4990.4    0.07       0  4996.4    0.16       0
  5035.8    0.05       0
Bank Sta=4808.8,5015.4
Exp/Cntr=0.3,0.1

Type RM Length L Ch R = 1,4485,404,404,404
BEGIN DESCRIPTION:
UNT 114 in Running Cr Watershed 9.0
END DESCRIPTION:
XS GIS Cut Line= 3
      2865862.84      7017973.52      2865825.00      7017675.00
      2865570.46      7017379.40
#Sta/Elev= 30
  4678.7  421.36  4717.5  419.50  4737.7  419.17  4794.8  416.77  4828.6  415.98
  4848.6  416.18  4919.1  414.81  4969.5  415.22  4982.9  414.93  4986.7  413.17
  4990.3  412.96  4990.8  412.16  4995.8  412.16  4996.3  412.96  5001.0  414.33
  5007.6  414.36  5015.3  415.73  5021.9  415.72  5026.6  416.77  5050.4  419.73
  5093.8  423.37  5110.7  424.14  5142.5  425.52  5150.2  426.22  5156.8  426.09
  5164.4  426.96  5185.3  427.55  5277.5  427.41  5341.1  429.09  5369.7  429.26
#Mann=6,-1,0
  4678.7    0.16       0  4828.6    0.07       0  4990.3    0.07       0
  4996.3    0.07       0  5093.8    0.16       0  5110.7    0.05       0
Bank Sta=4794.8,5026.6
Exp/Cntr=0.3,0.1

Type RM Length L Ch R = 1,4081,596,596,596
BEGIN DESCRIPTION:
UNT 114 in Running Cr Watershed 8.0
END DESCRIPTION:
XS GIS Cut Line= 3
      2866209.18      7017814.69      2866024.30      7017551.68
      2865670.35      7017339.83
#Sta/Elev= 30
  4755.7  424.83  4829.3  424.35  4865.3  423.23  4938.7  418.92  4945.2  417.18
  4951.3  417.34  4959.8  415.20  4966.1  415.17  4987.6  413.05  4992.7  409.71
  4993.2  408.91  4998.2  408.91  4998.7  409.71  5001.8  412.06  5010.5  413.94
  5039.1  413.71  5118.3  414.21  5163.3  413.44  5192.8  415.20  5213.3  416.56
  5277.1  420.92  5293.3  422.25  5314.7  422.68  5367.2  425.51  5394.4  425.30
  5410.0  425.92  5415.8  425.30  5431.4  425.39  5447.0  426.47  5489.7  426.47
#Mann=7,-1,0
  4755.7    0.16       0  4992.7    0.07       0  4998.7    0.16       0
  5039.1    0.12       0  5163.3    0.05       0  5213.3    0.12       0
  5277.1    0.05       0
Bank Sta=4959.8,5192.8
Exp/Cntr=0.3,0.1

Type RM Length L Ch R = 1,3485,486,486,486
BEGIN DESCRIPTION:
UNT 114 in Running Cr Watershed 7.0
END DESCRIPTION:
XS GIS Cut Line= 3
      2866324.97      7017424.97      2866079.52      7017222.33
      2865648.33      7017226.15
#Sta/Elev= 30
  4582.7  421.43  4604.2  420.56  4639.3  417.45  4647.2  417.82  4653.7  417.04
  4660.5  417.18  4674.5  416.05  4678.7  416.10  4696.7  415.40  4734.5  413.16
  4752.7  412.40  4810.8  411.52  4845.2  411.19  4873.8  411.91  4897.7  411.24
  4925.5  411.72  4965.5  411.54  4985.5  411.92  5002.5  410.05  5003.0  409.25
  5008.0  409.25  5008.5  410.05  5012.5  413.16  5015.5  415.51  5025.5  417.03
  5065.5  419.26  5088.5  421.11  5175.5  424.93  5265.5  427.81  5332.2  428.46
#Mann=7,-1,0
  4582.7    0.05       0  4678.7    0.16       0  4810.8    0.05       0
  4897.7    0.16       0  5002.5    0.07       0  5008.5    0.16       0
  5088.5    0.05       0
Bank Sta=4734.5,5012.5
Exp/Cntr=0.3,0.1

Type RM Length L Ch R = 1,2999,680,680,680
BEGIN DESCRIPTION:
UNT 114 in Running Cr Watershed 6.0
END DESCRIPTION:
XS GIS Cut Line= 3
      2866425.01      7017425.04      2866318.57      7017134.15
      2866097.91      7016718.78
#Sta/Elev= 30
  4604.2  422.64  4619.5  422.38  4650.0  421.06  4761.5  413.85  4828.8  411.29
  4870.5  410.53  4891.8  411.10  4931.1  410.17  4936.8  410.47  4953.1  410.03
  4975.1  410.71  4980.9  409.20  4994.0  407.65  4994.5  406.85  4999.5  406.85
  5000.0  407.65  5003.6  409.20  5028.6  411.29  5145.2  417.30  5150.9  417.30
  5167.2  418.30  5173.4  419.16  5218.7  420.17  5277.1  423.35  5293.5  423.41
  5299.1  423.96  5315.4  423.70  5337.4  423.96  5359.4  424.84  5384.3  424.98
#Mann=3,-1,0
  4604.2    0.05       0  4994.0    0.03       0  5000.0    0.05       0
Bank Sta=4828.8,5028.6
Exp/Cntr=0.3,0.1

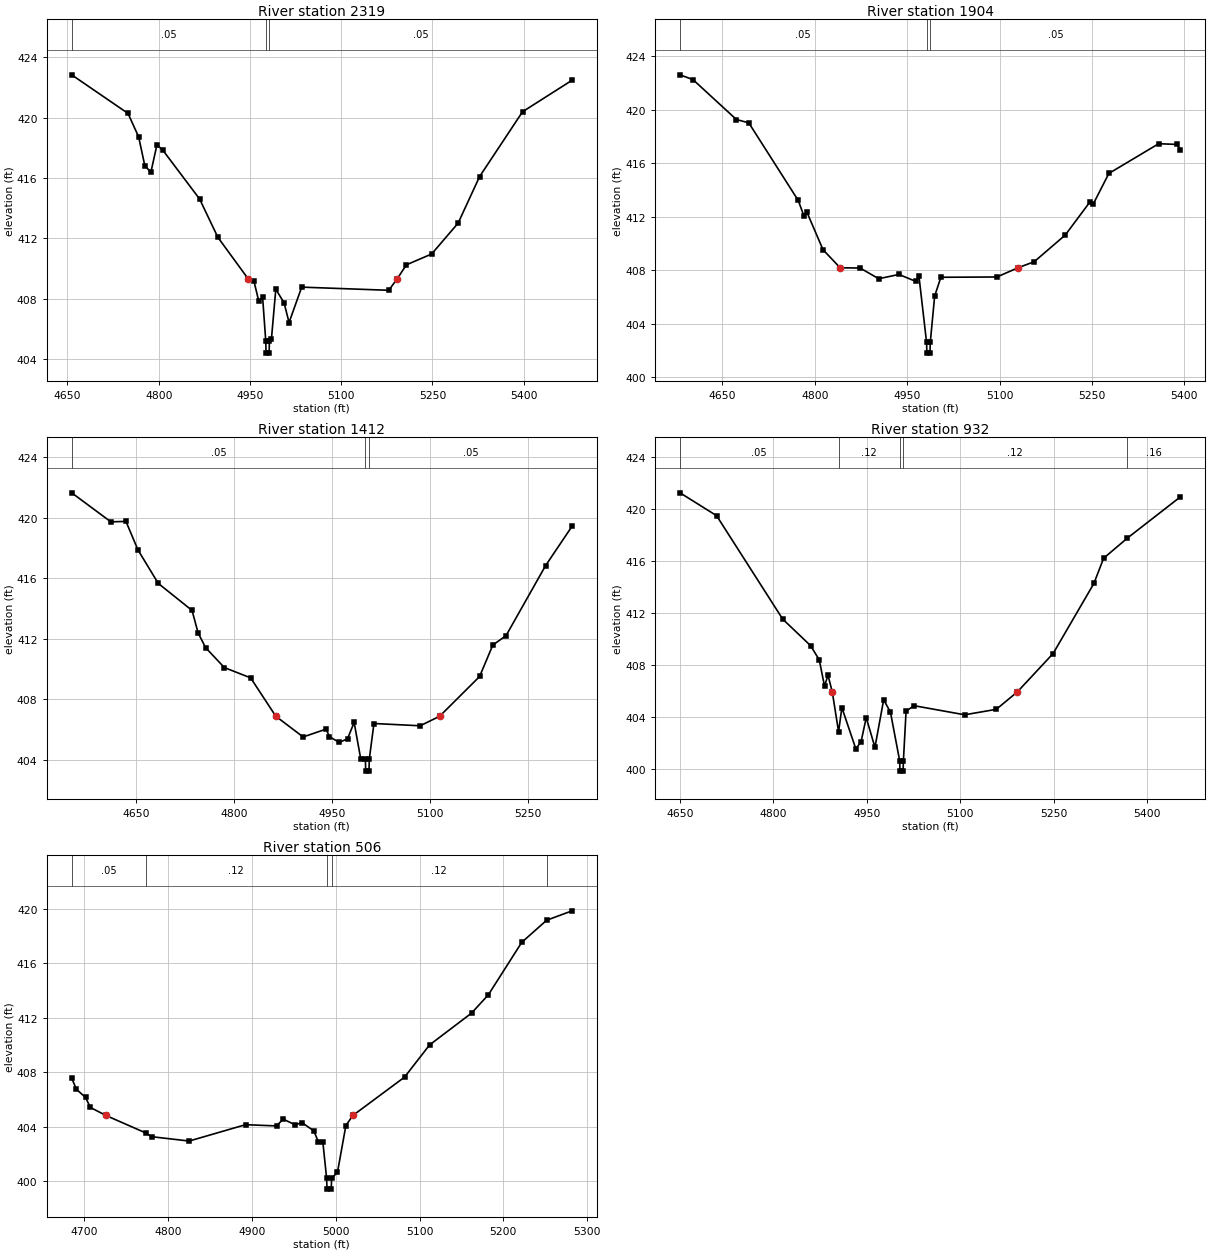
Type RM Length L Ch R = 1,2319,415,415,415
BEGIN DESCRIPTION:
UNT 114 in Running Cr Watershed 5.0
END DESCRIPTION:
XS GIS Cut Line= 3
      2866725.00      7017374.98      2866739.58      7017112.45
      2866396.82      7016669.90
#Sta/Elev= 30
  4656.9  422.85  4749.5  420.29  4767.0  418.73  4777.1  416.83  4787.1  416.38
  4797.1  418.21  4807.1  417.83  4867.2  414.61  4897.2  412.07  4946.7  409.33
  4956.3  409.20  4964.5  407.83  4970.8  408.10  4976.0  405.18  4976.5  404.38
  4981.5  404.38  4982.0  405.18  4985.3  405.31  4992.5  408.62  5006.1  407.72
  5014.3  406.41  5035.1  408.76  5178.2  408.55  5192.4  409.33  5207.2  410.24
  5248.8  410.96  5292.3  413.01  5327.6  416.10  5398.2  420.40  5479.6  422.49
#Mann=3,-1,0
  4656.9    0.05       0  4976.0   0.035       0  4982.0    0.05       0
Bank Sta=4946.7,5192.4
Exp/Cntr=0.3,0.1

Type RM Length L Ch R = 1,1904,492,492,492
BEGIN DESCRIPTION:
UNT 114 in Running Cr Watershed 4.0
END DESCRIPTION:
XS GIS Cut Line= 3
      2866900.17      7017286.03      2866934.56      7016932.38
      2866869.98      7016480.09
#Sta/Elev= 30
  4581.4  422.62  4602.5  422.26  4672.9  419.28  4693.0  419.03  4773.3  413.23
  4782.3  412.10  4787.3  412.36  4813.5  409.55  4841.3  408.20  4873.8  408.18
  4903.9  407.38  4936.7  407.70  4964.2  407.18  4969.2  407.58  4981.6  402.62
  4982.1  401.82  4987.1  401.82  4987.6  402.62  4994.7  406.08  5004.8  407.49
  5095.7  407.51  5130.0  408.20  5156.3  408.65  5206.8  410.65  5247.1  413.14
  5252.1  412.96  5277.5  415.25  5358.3  417.47  5388.5  417.42  5393.6  417.00
#Mann=3,-1,0
  4581.4    0.05       0  4981.6   0.035       0  4987.6    0.05       0
Bank Sta=4841.3,5130
Exp/Cntr=0.3,0.1

Type RM Length L Ch R = 1,1412,480,480,480
BEGIN DESCRIPTION:
UNT 114 in Running Cr Watershed 3.0
END DESCRIPTION:
XS GIS Cut Line= 3
      2867069.45      7017273.00      2867175.00      7016875.00
      2867225.00      7016525.01
#Sta/Elev= 30
  4551.6  421.65  4611.6  419.73  4634.6  419.76  4653.0  417.87  4684.0  415.66
  4735.7  413.87  4744.9  412.39  4756.4  411.41  4785.1  410.09  4825.3  409.41
  4863.8  406.87  4905.6  405.50  4940.7  406.02  4945.8  405.52  4960.8  405.14
  4973.5  405.38  4983.6  406.46  4993.7  404.05  5000.8  404.04  5001.3  403.24
  5006.3  403.24  5006.8  404.04  5013.9  406.39  5084.6  406.24  5114.4  406.87
  5175.5  409.50  5195.7  411.58  5215.9  412.20  5276.5  416.84  5316.9  419.44
#Mann=3,-1,0
  4551.6    0.05       0  5000.8   0.035       0  5006.8    0.05       0
Bank Sta=4863.8,5114.4
Exp/Cntr=0.3,0.1

Type RM Length L Ch R = 1,932,426,426,426
BEGIN DESCRIPTION:
UNT 114 in Running Cr Watershed 2.0
END DESCRIPTION:
XS GIS Cut Line= 3
      2867375.01      7017274.98      2867525.00      7016975.00
      2867603.30      7016513.48
#Sta/Elev= 30
  4650.1  421.26  4708.8  419.50  4815.0  411.53  4859.7  409.49  4873.7  408.39
  4882.1  406.37  4887.7  407.21  4894.6  405.92  4904.7  402.85  4910.0  404.71
  4932.4  401.54  4940.8  402.08  4949.1  403.94  4963.1  401.65  4977.1  405.32
  4988.0  404.36  5002.8  400.62  5003.3  399.82  5008.3  399.82  5008.8  400.62
  5013.1  404.45  5026.1  404.86  5107.2  404.16  5157.9  404.58  5191.7  405.92
  5249.2  408.88  5314.7  414.28  5330.3  416.22  5368.4  417.77  5453.6  420.95
#Mann=5,-1,0
  4650.1    0.05       0  4904.7    0.12       0  5002.8    0.07       0
  5008.8    0.12       0  5368.4    0.16       0
Bank Sta=4894.6,5191.7
Exp/Cntr=0.3,0.1

Type RM Length L Ch R = 1,506,0,0,0
BEGIN DESCRIPTION:
UNT 114 in Running Cr Watershed 1.0
END DESCRIPTION:
XS GIS Cut Line= 3
      2867689.96      7017289.89      2867825.00      7017025.00
      2867825.00      7016725.02
#Sta/Elev= 30
  4684.8  407.56  4690.4  406.74  4701.4  406.14  4707.0  405.41  4725.6  404.82
  4773.0  403.54  4780.1  403.26  4825.0  402.94  4892.3  404.14  4929.3  404.05
  4937.2  404.55  4951.6  404.13  4959.7  404.29  4973.8  403.69  4979.3  402.88
  4984.6  402.88  4989.1  400.21  4989.6  399.41  4994.6  399.41  4995.1  400.21
  5002.1  400.65  5012.1  404.08  5020.5  404.82  5082.1  407.63  5112.1  410.00
  5162.1  412.33  5182.1  413.67  5222.1  417.53  5251.8  419.15  5282.1  419.84
#Mann=5,-1,0
  4684.8    0.05       0  4773.0    0.12       0  4989.1    0.07       0
  4995.1    0.12       0  5251.8    0.16       0
Bank Sta=4725.6,5020.5
Exp/Cntr=0.3,0.1

Chan Stop Cuts=-1