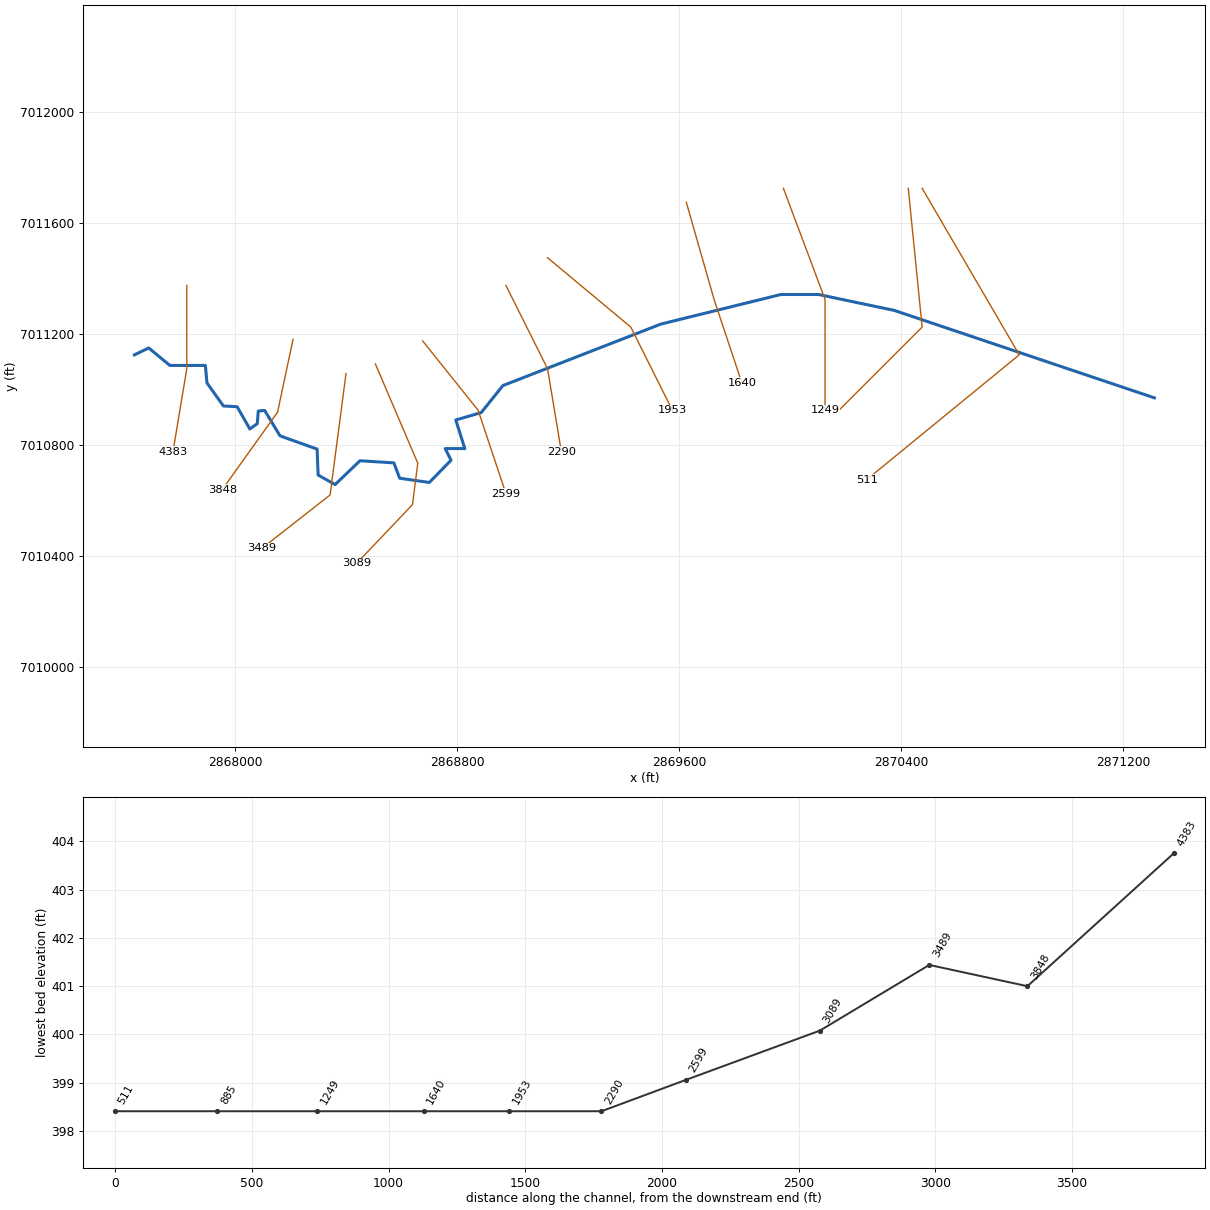
--- UNT 115 in Running Cr Watershed.prj (project) ---

Proj Title=UNT 115 in Running Cr Watershed Base Level Engineering
Current Plan=p01
Default Exp/Contr=0.3,0.1
English Units
Geom File=g01
Flow File=f01
Plan File=p01
BEGIN DESCRIPTION:
UNT 115 in Running Cr Watershed
END DESCRIPTION:

--- UNT 115 in Running Cr Watershed.p01 (plan) ---

Plan Title=Multiple Run
Short Identifier=Multiple
Geom File=g01
Flow File=f01
Subcritical Flow
K Sum by GR= 0
Std Step Tol= 0.01
Critical Tol= 0.01
Num of Std Step Trials= 20
Max Error Tol= 0.3
Flow Tol Ratio= 0.001
Split Flow NTrial= 30
Split Flow Tol= 0.02
Split Flow Ratio= 0.02
Log Output Level= 0
Friction Slope Method= 1
Unsteady Friction Slope Method= 2
Unsteady Bridges Friction Slope Method= 1
Parabolic Critical Depth
Global Vel Dist=  1 , 1 , 1
Global Log Level= 0
CheckData=True
Encroach Param= -1, 0, 0, 0
BEGIN DESCRIPTION:
Multiple Run
END DESCRIPTION:

--- UNT 115 in Running Cr Watershed.f01 (steady flow) ---

Flow Title=Multiple
Number of Profiles=7
Profile Names=10-year,25-year,50-year,1pct_min,100-year,1pct_plu,500-year
River Rch & RM= UNT 115 in Runni,Reach-1,4383
     375     484     569     333     664    1325     905
Boundary for River Rch & Prof#=UNT 115 in Runni,Reach-1,1
Up Type=0
Dn Type=3
Dn Slope=0.005
Boundary for River Rch & Prof#=UNT 115 in Runni,Reach-1,2
Up Type=0
Dn Type=3
Dn Slope=0.005
Boundary for River Rch & Prof#=UNT 115 in Runni,Reach-1,3
Up Type=0
Dn Type=3
Dn Slope=0.005
Boundary for River Rch & Prof#=UNT 115 in Runni,Reach-1,4
Up Type=0
Dn Type=3
Dn Slope=0.005
Boundary for River Rch & Prof#=UNT 115 in Runni,Reach-1,5
Up Type=0
Dn Type=3
Dn Slope=0.005
Boundary for River Rch & Prof#=UNT 115 in Runni,Reach-1,6
Up Type=0
Dn Type=3
Dn Slope=0.005
Boundary for River Rch & Prof#=UNT 115 in Runni,Reach-1,7
Up Type=0
Dn Type=3
Dn Slope=0.005

--- UNT 115 in Running Cr Watershed.g01 (geometry) ---

Geom Title=Existing Conditions

River Reach=UNT 115 in Runni,Reach-1
Reach XY= 30
      2867636.24      7011124.87      2867687.76      7011149.67
      2867764.08      7011086.71      2867891.91      7011086.71
      2867897.64      7011023.74      2867956.89      7010940.69
      2868006.40      7010937.88      2868052.19      7010857.74
      2868078.90      7010876.82      2868082.72      7010922.61
      2868105.61      7010924.52      2868160.95      7010832.94
      2868294.51      7010785.24      2868298.32      7010691.74
      2868359.38      7010657.40      2868449.06      7010743.26
      2868571.17      7010735.63      2868592.16      7010680.30
      2868699.01      7010665.03      2868777.24      7010745.17
      2868756.25      7010787.15      2868826.85      7010787.15
      2868794.41      7010890.18      2868886.00      7010916.89
      2868964.22      7011014.20      2869532.82      7011235.53
      2869965.94      7011342.38      2870101.41      7011342.38
      2870374.26      7011285.14      2871312.02      7010969.87

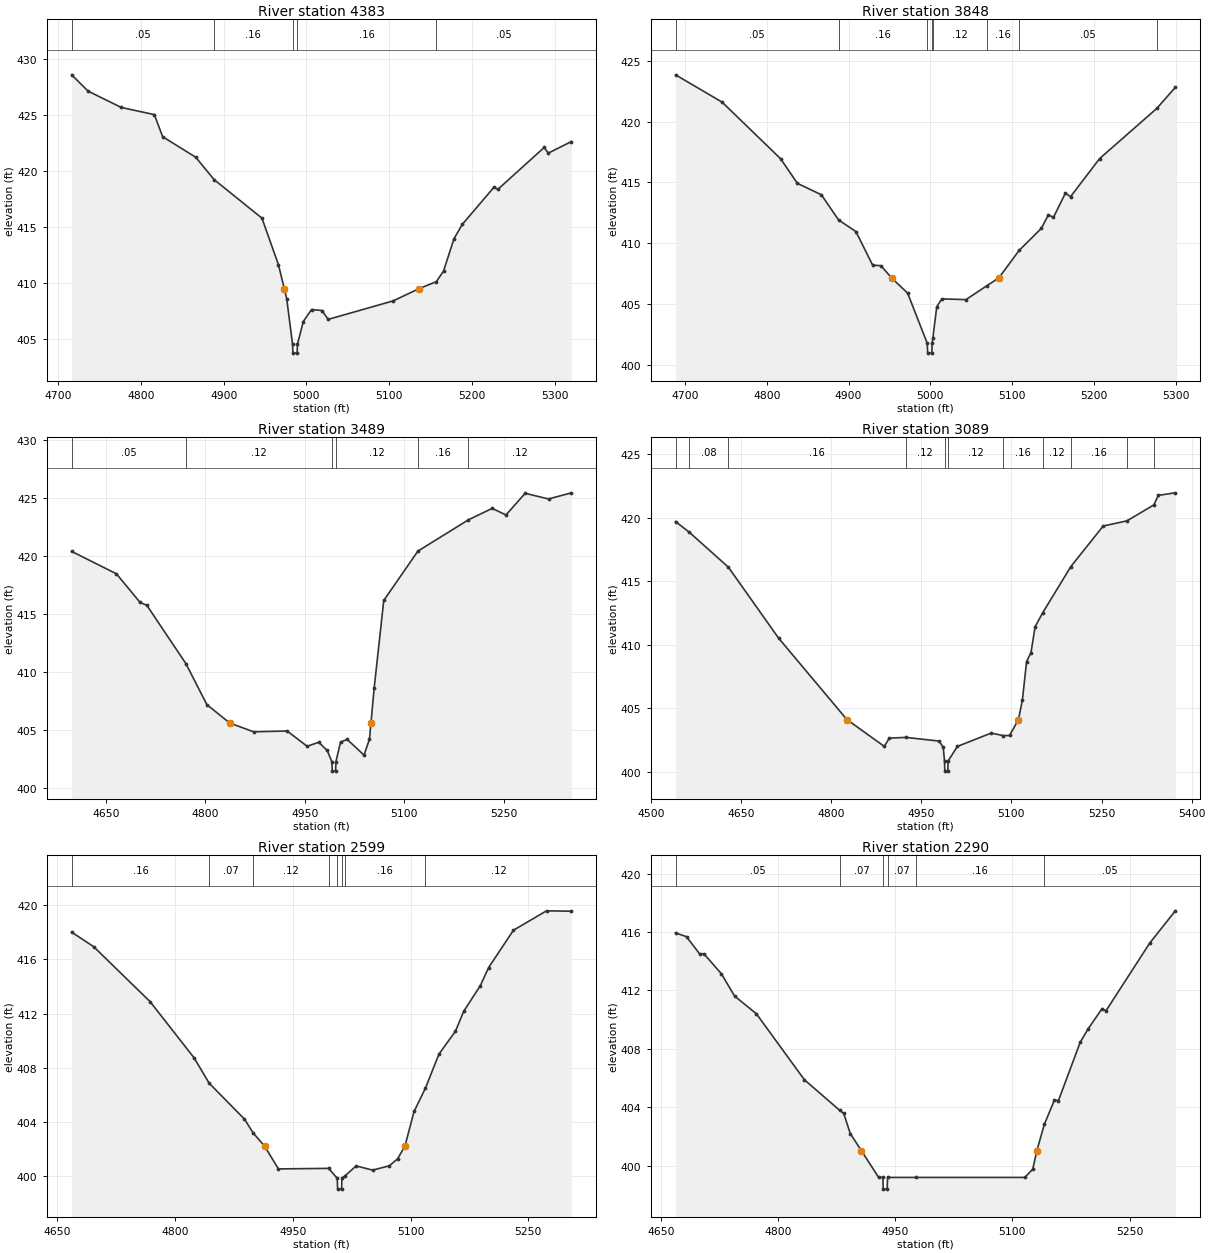
Type RM Length L Ch R = 1,4383,535,535,535
BEGIN DESCRIPTION:
UNT 115 in Running Cr Watershed 11.0
END DESCRIPTION:
XS GIS Cut Line= 3
      2867825.00      7011374.97      2867825.00      7011075.00
      2867775.00      7010775.01
#Sta/Elev= 30
  4716.2  428.57  4736.2  427.11  4776.2  425.66  4816.2  425.02  4826.2  423.05
  4866.2  421.22  4888.3  419.23  4946.2  415.79  4966.2  411.63  4973.2  409.51
  4976.2  408.59  4983.2  404.55  4983.7  403.75  4988.7  403.75  4989.2  404.55
  4996.2  406.57  5006.2  407.64  5018.7  407.55  5026.3  406.76  5104.9  408.41
  5136.4  409.51  5157.0  410.12  5165.7  411.06  5178.4  413.96  5188.5  415.24
  5226.5  418.53  5231.6  418.37  5287.4  422.09  5292.4  421.59  5320.3  422.62
#Mann=5,-1,0
  4716.2    0.05       0  4888.3    0.16       0  4983.2    0.07       0
  4989.2    0.16       0  5157.0    0.05       0
Bank Sta=4973.2,5136.4
Exp/Cntr=0.3,0.1

Type RM Length L Ch R = 1,3848,359,359,359
BEGIN DESCRIPTION:
UNT 115 in Running Cr Watershed 10.0
END DESCRIPTION:
XS GIS Cut Line= 3
      2868207.76      7011180.66      2868152.19      7010918.47
      2867952.89      7010639.45
#Sta/Elev= 30
  4688.5  423.83  4745.4  421.59  4817.0  416.94  4837.4  414.93  4866.8  413.99
  4887.7  411.93  4909.0  410.97  4929.4  408.22  4939.6  408.17  4952.6  407.17
  4972.2  405.92  4996.2  401.80  4996.7  401.00  5001.7  401.00  5002.2  401.80
  5003.1  402.28  5007.8  404.81  5014.0  405.45  5043.5  405.39  5068.6  406.51
  5083.7  407.17  5108.4  409.42  5135.7  411.24  5144.3  412.35  5150.4  412.13
  5165.1  414.13  5171.3  413.83  5206.9  416.96  5276.7  421.07  5299.4  422.80
#Mann=8,-1,0
  4688.5    0.05       0  4887.7    0.16       0  4996.2    0.07       0
  5002.2    0.16       0  5003.1    0.12       0  5068.6    0.16       0
  5108.4    0.05       0  5276.7    0.12       0
Bank Sta=4952.6,5083.7
Exp/Cntr=0.3,0.1

Type RM Length L Ch R = 1,3489,400,400,400
BEGIN DESCRIPTION:
UNT 115 in Running Cr Watershed 9.0
END DESCRIPTION:
XS GIS Cut Line= 3
      2868398.73      7011057.40      2868341.43      7010619.86
      2868094.89      7010427.14
#Sta/Elev= 30
  4598.2  420.38  4665.8  418.45  4701.5  415.98  4711.6  415.74  4770.6  410.71
  4802.3  407.17  4837.0  405.58  4872.9  404.83  4923.4  404.90  4953.6  403.58
  4971.1  403.93  4983.9  403.22  4991.0  402.24  4991.5  401.44  4996.5  401.44
  4997.0  402.24  5004.0  403.95  5014.1  404.17  5039.4  402.82  5047.6  404.18
  5049.9  405.58  5054.7  408.57  5069.2  416.15  5120.8  420.41  5196.9  423.10
  5232.9  424.09  5253.7  423.52  5282.6  425.39  5317.9  424.90  5352.4  425.43
#Mann=6,-1,0
  4598.2    0.05       0  4770.6    0.12       0  4991.0    0.07       0
  4997.0    0.12       0  5120.8    0.16       0  5196.9    0.12       0
Bank Sta=4837,5049.9
Exp/Cntr=0.3,0.1

Type RM Length L Ch R = 1,3089,490,490,490
BEGIN DESCRIPTION:
UNT 115 in Running Cr Watershed 8.0
END DESCRIPTION:
XS GIS Cut Line= 4
      2868504.62      7011092.10      2868657.40      7010734.45
      2868638.30      7010585.14      2868436.92      7010373.34
#Sta/Elev= 30
  4541.1  419.68  4563.6  418.86  4629.0  416.10  4712.5  410.53  4826.3  404.13
  4888.5  402.02  4896.8  402.67  4924.5  402.73  4979.9  402.44  4986.6  401.94
  4988.7  400.88  4989.2  400.08  4994.2  400.08  4994.7  400.88  5010.1  402.02
  5066.4  403.07  5086.2  402.87  5097.0  402.88  5111.8  404.13  5118.4  405.69
  5125.3  408.69  5132.6  409.39  5139.5  411.42  5152.0  412.51  5199.0  416.15
  5252.7  419.33  5292.3  419.74  5337.1  420.99  5344.6  421.74  5372.8  421.94
#Mann=11,-1,0
  4541.1    0.16       0  4563.6    0.08       0  4629.0    0.16       0
  4924.5    0.12       0  4988.7    0.07       0  4994.7    0.12       0
  5086.2    0.16       0  5152.0    0.12       0  5199.0    0.16       0
  5292.3    0.12       0  5337.1    0.16       0
Bank Sta=4826.3,5111.8
Exp/Cntr=0.3,0.1

Type RM Length L Ch R = 1,2599,309,309,309
BEGIN DESCRIPTION:
UNT 115 in Running Cr Watershed 7.0
END DESCRIPTION:
XS GIS Cut Line= 3
      2868675.01      7011174.99      2868875.00      7010925.00
      2868975.01      7010624.97
#Sta/Elev= 30
  4668.4  418.00  4696.4  416.93  4768.4  412.87  4824.5  408.72  4843.6  406.86
  4888.5  404.22  4899.4  403.21  4914.1  402.23  4931.7  400.55  4995.6  400.59
  5006.6  399.86  5007.1  399.06  5012.1  399.06  5012.6  399.86  5016.7  400.05
  5030.7  400.77  5051.8  400.46  5072.9  400.78  5083.4  401.29  5092.8  402.23
  5104.5  404.79  5119.0  406.51  5136.1  409.01  5157.2  410.70  5167.7  412.17
  5188.8  414.05  5199.4  415.39  5231.0  418.14  5273.1  419.57  5304.8  419.54
#Mann=8,-1,0
  4668.4    0.16       0  4843.6    0.07       0  4899.4    0.12       0
  4995.6    0.07       0  5006.6    0.07       0  5012.6    0.07       0
  5016.7    0.16       0  5119.0    0.12       0
Bank Sta=4914.1,5092.8
Exp/Cntr=0.3,0.1

Type RM Length L Ch R = 1,2290,337,337,337
BEGIN DESCRIPTION:
UNT 115 in Running Cr Watershed 6.0
END DESCRIPTION:
XS GIS Cut Line= 3
      2868975.00      7011374.99      2869125.00      7011075.00
      2869174.99      7010775.04
#Sta/Elev= 30
  4669.0  415.94  4683.0  415.68  4699.7  414.51  4705.3  414.51  4727.7  413.14
  4744.5  411.62  4772.4  410.41  4833.9  405.89  4879.3  403.79  4884.2  403.59
  4892.6  402.21  4906.8  401.04  4928.9  399.21  4934.3  399.21  4934.8  398.41
  4939.8  398.41  4940.3  399.21  4977.2  399.21  5115.9  399.21  5126.1  399.78
  5131.3  401.04  5140.9  402.84  5153.9  404.51  5159.0  404.47  5186.9  408.47
  5197.0  409.38  5214.8  410.76  5219.8  410.61  5275.6  415.23  5308.5  417.45
#Mann=6,-1,0
  4669.0    0.05       0  4879.3    0.07       0  4934.3    0.07       0
  4940.3    0.07       0  4977.2    0.16       0  5140.9    0.05       0
Bank Sta=4906.8,5131.3
Exp/Cntr=0.3,0.1

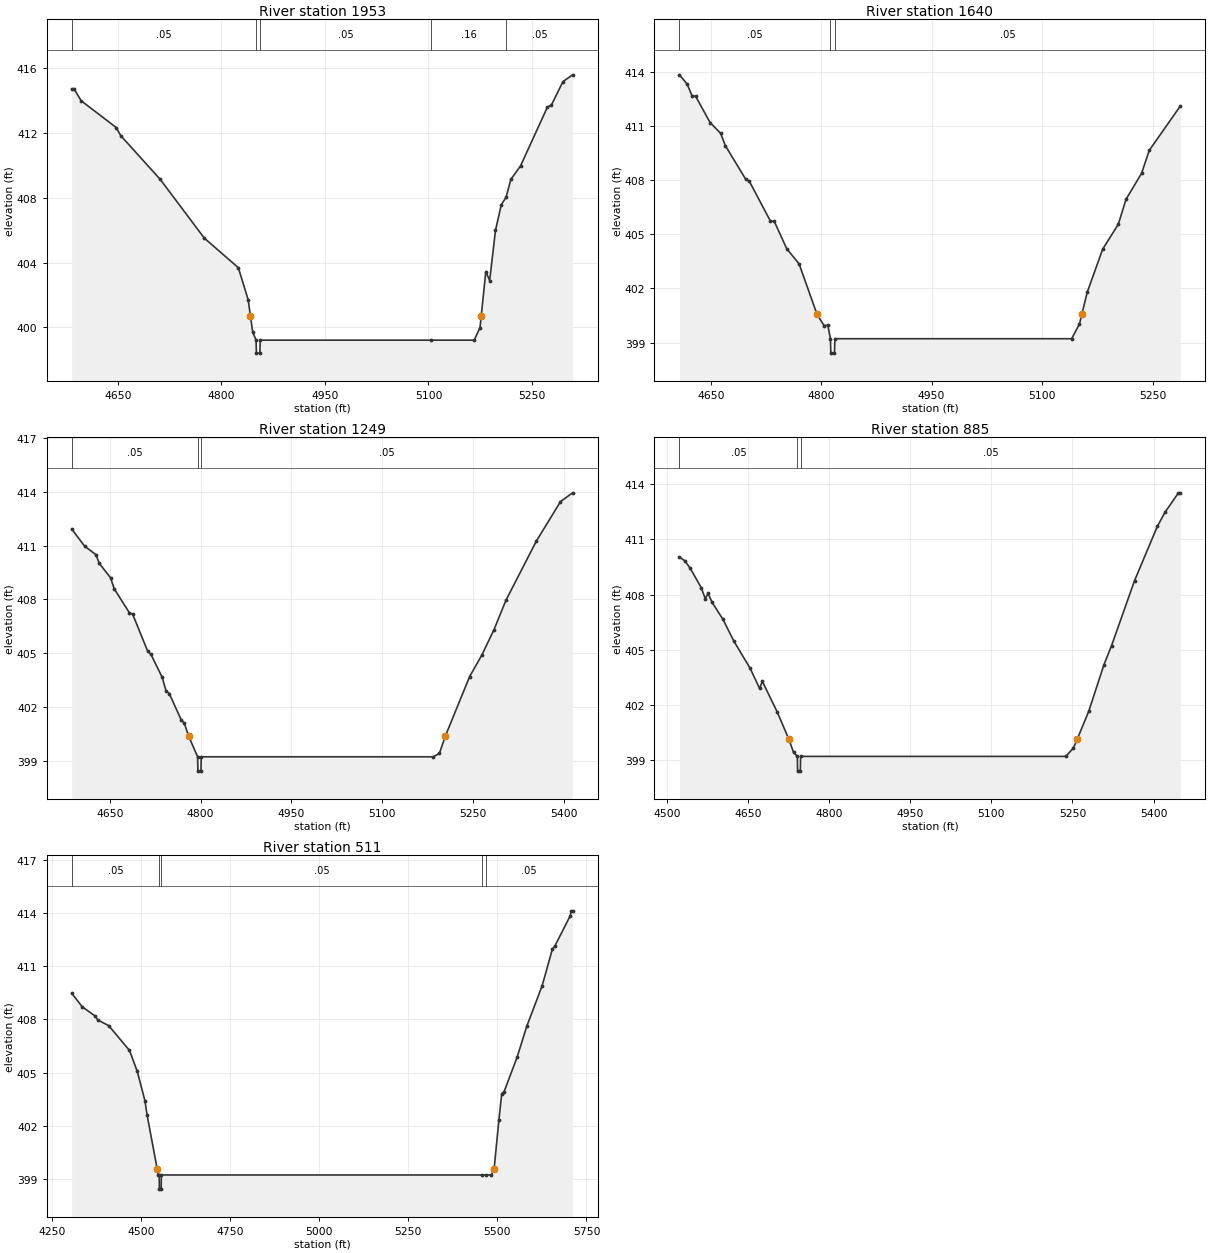
Type RM Length L Ch R = 1,1953,313,313,313
BEGIN DESCRIPTION:
UNT 115 in Running Cr Watershed 5.0
END DESCRIPTION:
XS GIS Cut Line= 3
      2869124.96      7011475.03      2869425.00      7011225.00
      2869575.01      7010924.98
#Sta/Elev= 30
  4582.9  414.72  4586.2  414.72  4596.6  413.98  4647.4  412.33  4653.9  411.83
  4711.2  409.13  4775.0  405.51  4824.4  403.68  4838.7  401.70  4841.9  400.72
  4845.2  399.72  4850.1  399.21  4850.6  398.41  4855.6  398.41  4856.1  399.21
  5104.2  399.21  5166.3  399.21  5174.7  399.99  5176.5  400.72  5183.1  403.44
  5188.7  402.89  5197.1  405.98  5205.5  407.56  5212.4  408.02  5219.4  409.13
  5233.4  409.96  5272.5  413.60  5278.1  413.71  5294.9  415.16  5308.9  415.58
#Mann=5,-1,0
  4582.9    0.05       0  4850.1   0.033       0  4856.1    0.05       0
  5104.2    0.16       0  5212.4    0.05       0
Bank Sta=4841.9,5176.5
Exp/Cntr=0.3,0.1

Type RM Length L Ch R = 1,1640,391,391,391
BEGIN DESCRIPTION:
UNT 115 in Running Cr Watershed 4.0
END DESCRIPTION:
XS GIS Cut Line= 3
      2869625.01      7011674.95      2869725.00      7011325.00
      2869825.00      7011024.99
#Sta/Elev= 30
  4607.6  413.86  4618.0  413.35  4624.5  412.71  4629.7  412.66  4649.2  411.21
  4663.5  410.61  4670.0  409.92  4697.3  408.08  4702.5  407.95  4731.1  405.74
  4736.3  405.73  4753.2  404.21  4770.1  403.36  4794.3  400.57  4803.9  399.94
  4809.1  399.96  4812.6  399.21  4813.1  398.41  4818.1  398.41  4818.6  399.21
  5140.2  399.21  5150.8  400.03  5154.0  400.57  5161.3  401.79  5182.4  404.19
  5203.5  405.56  5214.0  406.95  5235.1  408.39  5245.6  409.67  5287.8  412.13
#Mann=3,-1,0
  4607.6    0.05       0  4812.6   0.033       0  4818.6    0.05       0
Bank Sta=4794.3,5154
Exp/Cntr=0.3,0.1

Type RM Length L Ch R = 1,1249,364,364,364
BEGIN DESCRIPTION:
UNT 115 in Running Cr Watershed 3.0
END DESCRIPTION:
XS GIS Cut Line= 3
      2869975.00      7011725.01      2870125.00      7011325.00
      2870125.00      7010925.01
#Sta/Elev= 30
  4587.2  411.92  4608.6  410.96  4627.3  410.49  4632.6  410.01  4651.3  409.20
  4657.5  408.58  4682.4  407.25  4687.8  407.17  4712.7  405.10  4718.0  404.93
  4736.7  403.64  4743.0  402.88  4748.3  402.74  4767.9  401.28  4773.2  401.08
  4780.1  400.38  4795.1  399.21  4795.6  398.41  4800.6  398.41  4801.1  399.21
  5184.4  399.21  5194.4  399.40  5204.4  400.38  5244.4  403.69  5264.4  404.88
  5284.4  406.29  5304.4  407.95  5354.4  411.24  5394.4  413.45  5414.4  413.94
#Mann=3,-1,0
  4587.2    0.05       0  4795.1   0.033       0  4801.1    0.05       0
Bank Sta=4780.1,5204.4
Exp/Cntr=0.3,0.1

Type RM Length L Ch R = 1,885,374,374,374
BEGIN DESCRIPTION:
UNT 115 in Running Cr Watershed 2.0
END DESCRIPTION:
XS GIS Cut Line= 3
      2870425.00      7011725.05      2870475.00      7011225.00
      2870175.00      7010925.00
#Sta/Elev= 30
  4522.9  410.04  4533.0  409.83  4543.0  409.42  4563.1  408.38  4570.7  407.77
  4575.7  408.07  4583.2  407.58  4603.3  406.66  4623.4  405.48  4653.6  404.00
  4671.2  402.90  4676.2  403.29  4703.8  401.62  4725.2  400.15  4734.0  399.43
  4741.0  399.21  4741.5  398.41  4746.5  398.41  4747.0  399.21  5237.6  399.21
  5251.7  399.66  5258.9  400.15  5280.0  401.65  5308.3  404.19  5322.4  405.23
  5364.9  408.76  5407.3  411.72  5421.4  412.48  5446.2  413.53  5449.7  413.53
#Mann=3,-1,0
  4522.9    0.05       0  4741.0   0.033       0  4747.0    0.05       0
Bank Sta=4725.2,5258.9
Exp/Cntr=0.3,0.1

Type RM Length L Ch R = 1,511,0,0,0
BEGIN DESCRIPTION:
UNT 115 in Running Cr Watershed 1.0
END DESCRIPTION:
XS GIS Cut Line= 3
      2870474.98      7011725.03      2870825.00      7011125.00
      2870274.99      7010674.99
#Sta/Elev= 30
  4305.8  409.48  4335.2  408.72  4372.4  408.18  4378.2  407.98  4409.6  407.65
  4467.9  406.25  4489.8  405.06  4511.3  403.40  4517.1  402.62  4545.4  399.57
  4548.5  399.22  4551.3  399.21  4551.8  398.41  4556.8  398.41  4557.3  399.21
  5457.5  399.21  5467.0  399.21  5483.5  399.21  5491.0  399.57  5504.4  402.34
  5512.3  403.81  5518.7  403.91  5555.3  405.86  5582.6  407.62  5625.7  409.91
  5654.4  411.98  5660.8  412.13  5703.9  413.84  5707.9  414.14  5711.1  414.14
#Mann=5,-1,0
  4305.8    0.05       0  4551.3   0.033       0  4557.3    0.05       0
  5457.5    0.16       0  5467.0    0.05       0
Bank Sta=4545.4,5491
Exp/Cntr=0.3,0.1

Chan Stop Cuts=-1