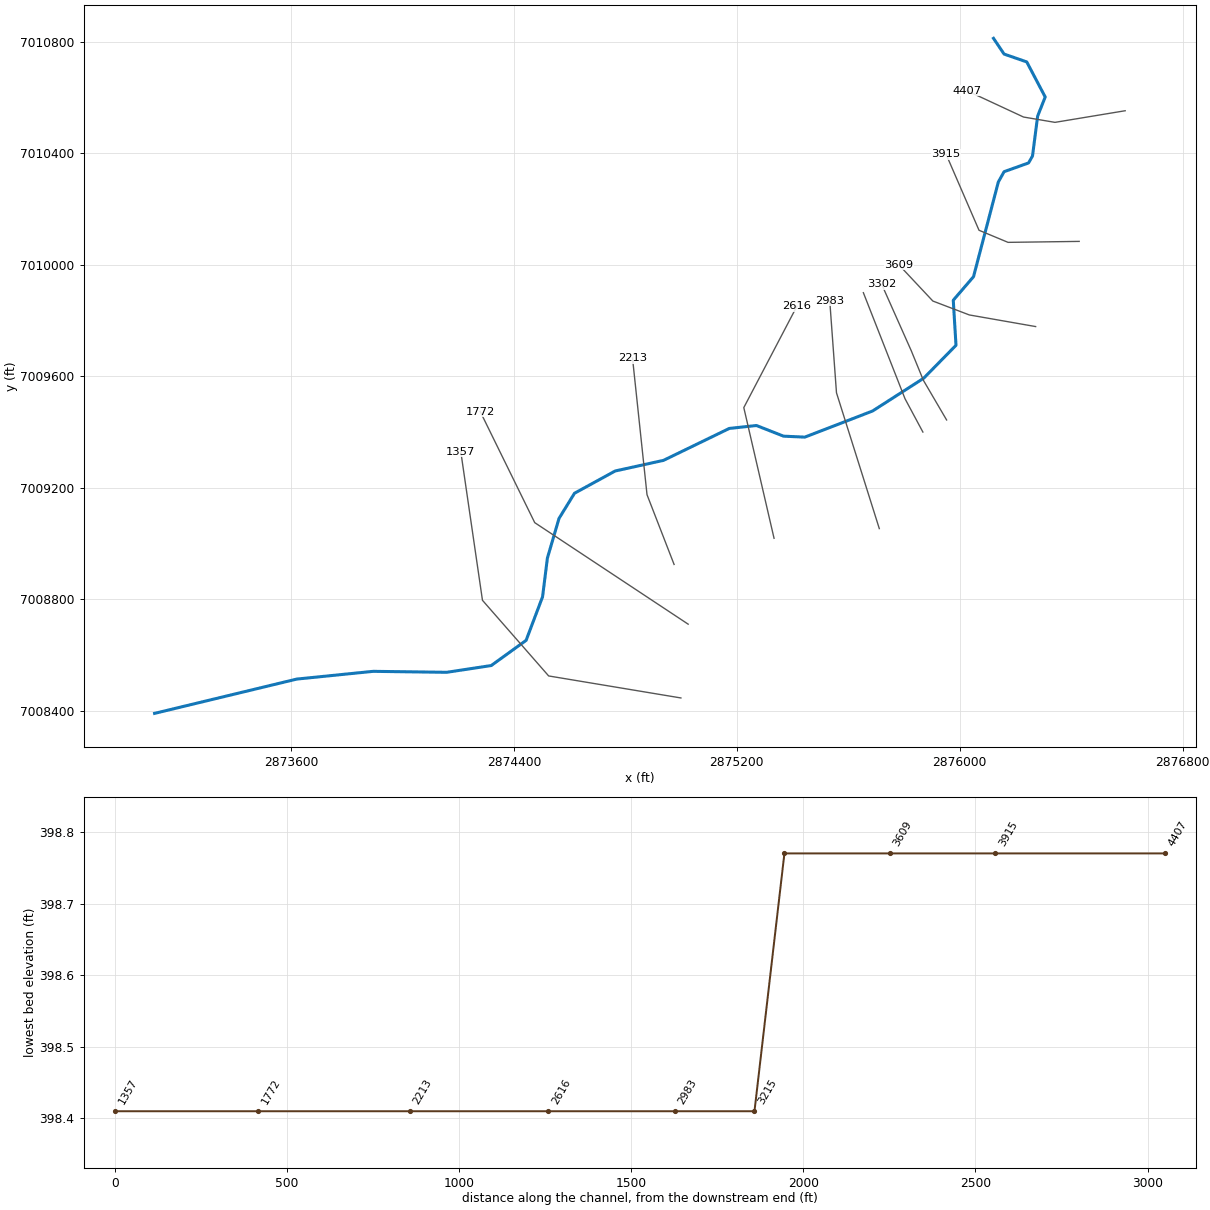
--- UNT 116 in Running Cr Watershed.prj (project) ---

Proj Title=UNT 116 in Running Cr Watershed Base Level Engineering
Current Plan=p01
Default Exp/Contr=0.3,0.1
English Units
Geom File=g01
Flow File=f01
Plan File=p01
BEGIN DESCRIPTION:
UNT 116 in Running Cr Watershed
END DESCRIPTION:

--- UNT 116 in Running Cr Watershed.p01 (plan) ---

Plan Title=Multiple Run
Short Identifier=Multiple
Geom File=g01
Flow File=f01
Subcritical Flow
K Sum by GR= 0
Std Step Tol= 0.01
Critical Tol= 0.01
Num of Std Step Trials= 20
Max Error Tol= 0.3
Flow Tol Ratio= 0.001
Split Flow NTrial= 30
Split Flow Tol= 0.02
Split Flow Ratio= 0.02
Log Output Level= 0
Friction Slope Method= 1
Unsteady Friction Slope Method= 2
Unsteady Bridges Friction Slope Method= 1
Parabolic Critical Depth
Global Vel Dist=  1 , 1 , 1
Global Log Level= 0
CheckData=True
Encroach Param= -1, 0, 0, 0
BEGIN DESCRIPTION:
Multiple Run
END DESCRIPTION:

--- UNT 116 in Running Cr Watershed.f01 (steady flow) ---

Flow Title=Multiple
Number of Profiles=7
Profile Names=10-year,25-year,50-year,1pct_min,100-year,1pct_plu,500-year
River Rch & RM= UNT 116 in Runni,Reach-1,4407
     266     334     384     220     439     876     573
Boundary for River Rch & Prof#=UNT 116 in Runni,Reach-1,1
Up Type=0
Dn Type=3
Dn Slope=0.005
Boundary for River Rch & Prof#=UNT 116 in Runni,Reach-1,2
Up Type=0
Dn Type=3
Dn Slope=0.005
Boundary for River Rch & Prof#=UNT 116 in Runni,Reach-1,3
Up Type=0
Dn Type=3
Dn Slope=0.005
Boundary for River Rch & Prof#=UNT 116 in Runni,Reach-1,4
Up Type=0
Dn Type=3
Dn Slope=0.005
Boundary for River Rch & Prof#=UNT 116 in Runni,Reach-1,5
Up Type=0
Dn Type=3
Dn Slope=0.005
Boundary for River Rch & Prof#=UNT 116 in Runni,Reach-1,6
Up Type=0
Dn Type=3
Dn Slope=0.005
Boundary for River Rch & Prof#=UNT 116 in Runni,Reach-1,7
Up Type=0
Dn Type=3
Dn Slope=0.005

--- UNT 116 in Running Cr Watershed.g01 (geometry) ---

Geom Title=Existing Conditions

River Reach=UNT 116 in Runni,Reach-1
Reach XY= 30
      2876120.94      7010812.58      2876158.92      7010756.16
      2876240.30      7010727.95      2876306.49      7010602.08
      2876279.36      7010533.72      2876260.91      7010390.49
      2876246.81      7010365.54      2876158.92      7010334.07
      2876138.30      7010297.18      2876049.33      7009957.55
      2875976.63      7009872.91      2875986.39      7009711.24
      2875870.29      7009592.97      2875687.13      7009475.56
      2875444.07      7009381.81      2875367.69      7009385.28
      2875270.46      7009423.48      2875173.24      7009413.06
      2874937.13      7009298.48      2874763.52      7009260.28
      2874617.69      7009180.42      2874562.13      7009090.14
      2874520.46      7008947.78      2874503.10      7008808.89
      2874444.07      7008652.64      2874319.07      7008562.37
      2874159.35      7008538.06      2873895.46      7008541.53
      2873621.16      7008513.76      2873111.21      7008390.72

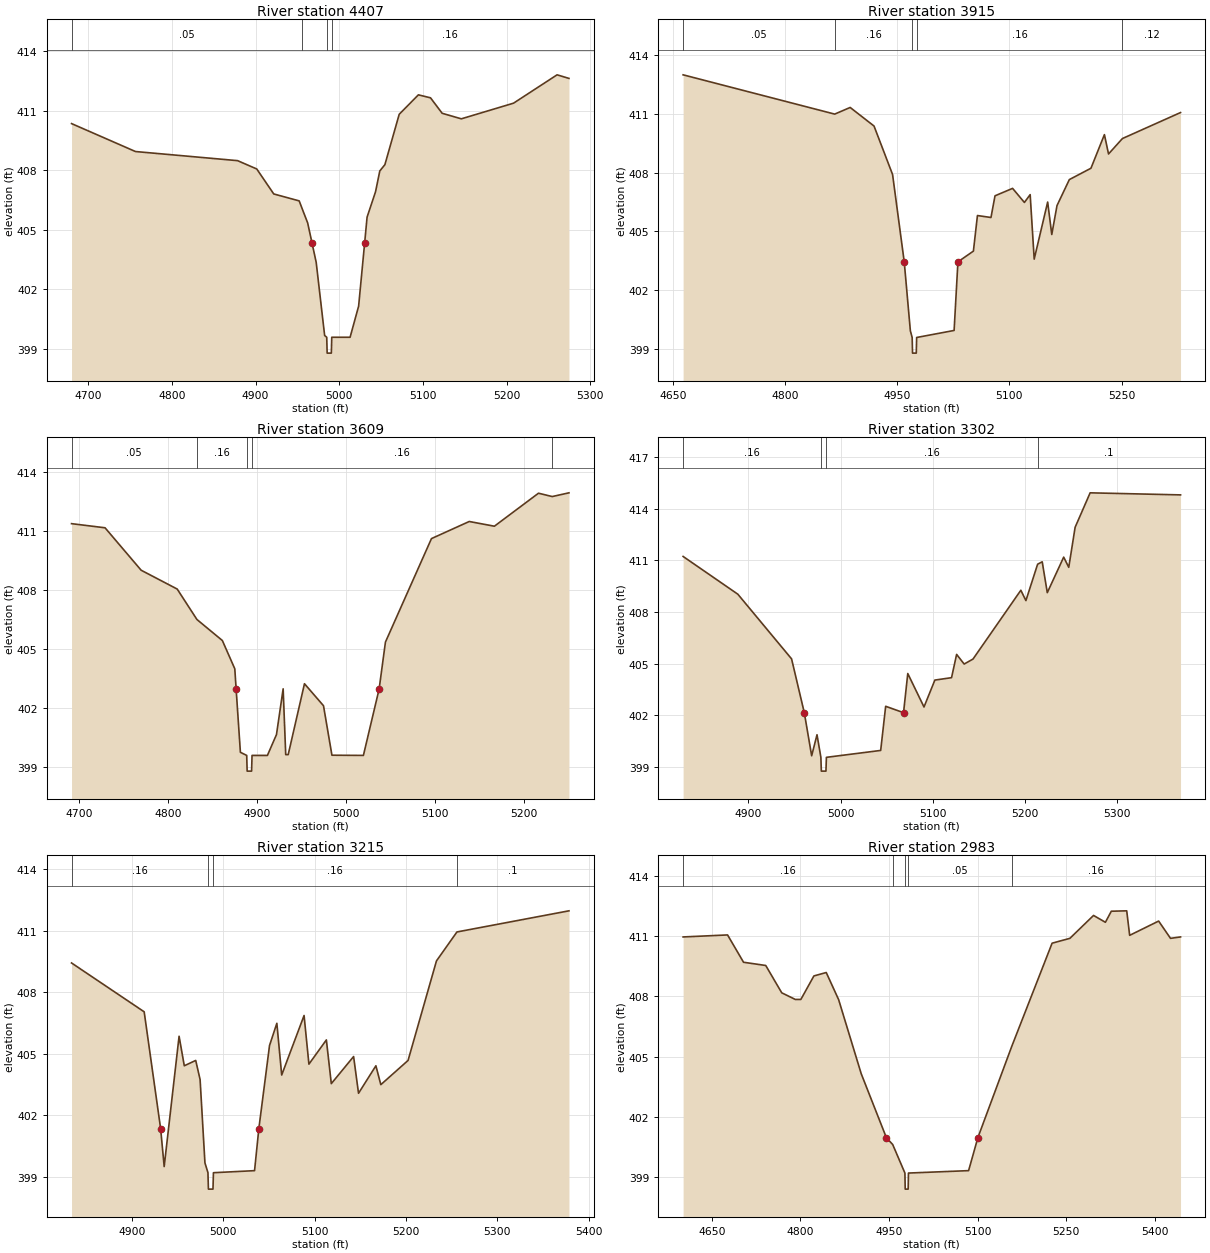
Type RM Length L Ch R = 1,4407,492,492,492
BEGIN DESCRIPTION:
UNT 116 in Running Cr Watershed 10.0
END DESCRIPTION:
XS GIS Cut Line= 4
      2876593.31      7010552.81      2876341.57      7010511.14
      2876228.73      7010530.24      2876025.00      7010625.00
#Sta/Elev= 30
  4680.2  410.35  4756.6  408.94  4878.6  408.48  4901.5  408.06  4921.8  406.80
  4952.2  406.45  4955.9  406.04  4962.3  405.34  4967.5  404.33  4972.5  403.35
  4982.6  399.66  4985.1  399.57  4985.6  398.77  4990.6  398.77  4991.1  399.57
  5013.0  399.57  5023.2  401.14  5030.4  404.33  5033.3  405.63  5043.4  406.91
  5048.5  407.96  5054.6  408.28  5071.7  410.82  5094.6  411.80  5109.1  411.65
  5123.0  410.87  5145.9  410.59  5208.3  411.38  5260.3  412.81  5274.5  412.63
#Mann=4,-1,0
  4680.2    0.05       0  4955.9    0.16       0  4985.1    0.07       0
  4991.1    0.16       0
Bank Sta=4967.5,5030.4
Exp/Cntr=0.3,0.1

Type RM Length L Ch R = 1,3915,306,306,306
BEGIN DESCRIPTION:
Mapping XS 13f776f2
END DESCRIPTION:
XS GIS Cut Line= 4
      2876428.42      7010084.06      2876173.17      7010080.58
      2876069.01      7010123.99      2875950.93      7010396.59
#Sta/Elev= 30
  4663.7  413.01  4866.4  411.00  4887.1  411.34  4919.0  410.39  4943.8  407.91
  4959.4  403.44  4967.6  399.91  4970.0  399.57  4970.5  398.77  4975.5  398.77
  4976.0  399.57  5026.1  399.93  5031.2  403.44  5051.9  403.99  5057.3  405.81
  5075.4  405.71  5080.8  406.82  5104.3  407.20  5120.1  406.48  5127.8  406.88
  5133.2  403.58  5151.2  406.50  5156.7  404.84  5163.7  406.32  5180.2  407.65
  5209.1  408.23  5227.1  409.95  5232.6  408.96  5251.2  409.75  5328.9  411.08
#Mann=5,-1,0
  4663.7    0.05       0  4866.4    0.16       0  4970.0    0.07       0
  4976.0    0.16       0  5251.2    0.12       0
Bank Sta=4959.4,5031.2
Exp/Cntr=0.3,0.1

Type RM Length L Ch R = 1,3609,307,307,307
BEGIN DESCRIPTION:
UNT 116 in Running Cr Watershed 9.0
END DESCRIPTION:
XS GIS Cut Line= 4
      2876272.13      7009778.50      2876034.28      7009820.17
      2875903.40      7009870.05      2875781.50      7009999.99
#Sta/Elev= 30
  4691.3  411.37  4729.0  411.16  4769.6  409.00  4810.2  408.04  4832.4  406.49
  4861.0  405.42  4875.0  403.98  4876.5  402.95  4881.3  399.73  4888.4  399.57
  4888.9  398.77  4893.9  398.77  4894.4  399.57  4911.7  399.57  4921.9  400.63
  4929.4  402.96  4932.3  399.61  4935.1  399.61  4953.4  403.22  4974.8  402.10
  4984.3  399.58  5019.7  399.57  5037.4  402.95  5044.5  405.34  5096.3  410.61
  5138.8  411.48  5167.1  411.24  5216.7  412.92  5232.2  412.75  5251.0  412.94
#Mann=5,-1,0
  4691.3    0.05       0  4832.4    0.16       0  4888.4    0.07       0
  4894.4    0.16       0  5232.2     0.1       0
Bank Sta=4876.5,5037.4
Exp/Cntr=0.3,0.1

Type RM Length L Ch R = 1,3302,87,87,87
BEGIN DESCRIPTION:
Mapping XS 9665343c
END DESCRIPTION:
XS GIS Cut Line= 4
      2875952.71      7009443.39      2875869.35      7009585.79
      2875825.95      7009691.69      2875720.05      7009929.53
#Sta/Elev= 30
  4829.2  411.22  4888.6  409.03  4946.9  405.28  4960.7  402.16  4968.7  399.66
  4974.5  400.88  4978.7  399.57  4979.2  398.77  4984.2  398.77  4984.7  399.57
  5043.6  399.97  5049.0  402.53  5068.4  402.16  5073.0  404.43  5090.6  402.49
  5102.4  404.05  5120.5  404.19  5126.0  405.54  5134.2  404.98  5143.8  405.27
  5195.7  409.26  5201.2  408.66  5213.9  410.77  5218.9  410.91  5224.4  409.12
  5242.2  411.18  5247.7  410.59  5254.6  412.91  5270.9  414.91  5369.0  414.79
#Mann=4,-1,0
  4829.2    0.16       0  4978.7    0.07       0  4984.7    0.16       0
  5213.9     0.1       0
Bank Sta=4960.7,5068.4
Exp/Cntr=0.3,0.1

Type RM Length L Ch R = 1,3215,232,232,232
BEGIN DESCRIPTION:
Mapping XS 6a6bf7ea
END DESCRIPTION:
XS GIS Cut Line= 3
      2875867.62      7009400.01      2875803.38      7009519.82
      2875654.08      7009900.01
#Sta/Elev= 30
  4833.9  409.43  4913.4  407.05  4931.4  401.36  4935.3  399.51  4951.6  405.86
  4957.3  404.42  4969.8  404.68  4974.6  403.75  4979.9  399.69  4983.2  399.21
  4983.7  398.41  4988.7  398.41  4989.2  399.21  5034.2  399.31  5038.9  401.36
  5050.6  405.41  5058.6  406.49  5063.9  403.97  5088.4  406.87  5093.7  404.50
  5112.8  405.68  5118.2  403.55  5142.6  404.87  5148.0  403.08  5167.0  404.42
  5172.4  403.50  5202.2  404.68  5233.3  409.53  5255.7  410.94  5378.3  411.97
#Mann=4,-1,0
  4833.9    0.16       0  4983.2    0.07       0  4989.2    0.16       0
  5255.7     0.1       0
Bank Sta=4931.4,5038.9
Exp/Cntr=0.3,0.1

Type RM Length L Ch R = 1,2983,367,367,367
BEGIN DESCRIPTION:
UNT 116 in Running Cr Watershed 7.0
END DESCRIPTION:
XS GIS Cut Line= 3
      2875711.22      7009053.69      2875557.63      7009540.86
      2875533.42      7009871.97
#Sta/Elev= 30
  4601.2  410.96  4676.5  411.06  4703.6  409.70  4741.2  409.54  4768.3  408.18
  4791.3  407.85  4800.7  407.85  4822.8  409.02  4843.7  409.19  4864.7  407.84
  4903.0  404.15  4945.6  400.97  4956.3  400.63  4977.0  399.21  4977.5  398.41
  4982.5  398.41  4983.0  399.21  5084.9  399.33  5100.6  400.97  5158.1  405.52
  5226.4  410.65  5256.5  410.89  5296.6  412.03  5316.7  411.69  5326.7  412.24
  5352.8  412.26  5357.8  411.04  5406.9  411.75  5427.0  410.89  5444.0  410.96
#Mann=5,-1,0
  4601.2    0.16       0  4956.3    0.05       0  4977.0   0.033       0
  4983.0    0.05       0  5158.1    0.16       0
Bank Sta=4945.6,5100.6
Exp/Cntr=0.3,0.1

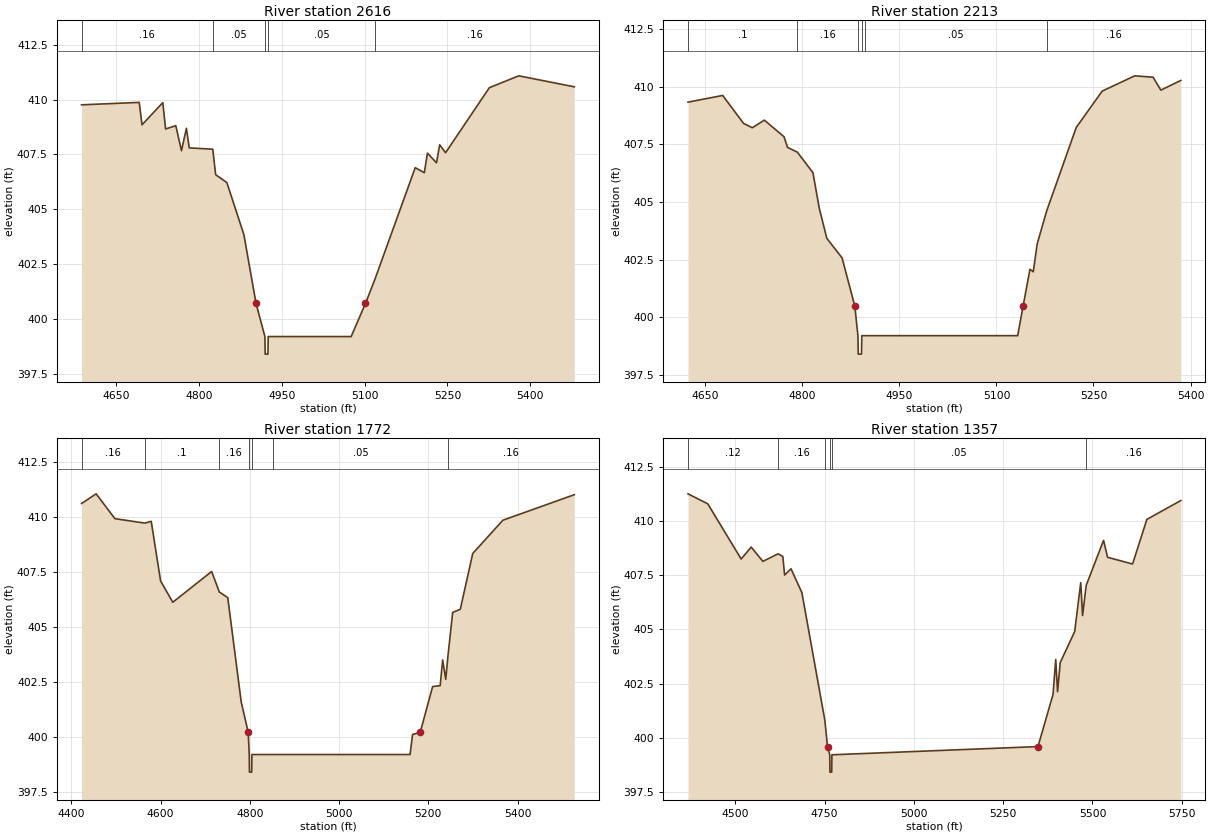
Type RM Length L Ch R = 1,2616,403,403,403
BEGIN DESCRIPTION:
UNT 116 in Running Cr Watershed 6.0
END DESCRIPTION:
XS GIS Cut Line= 3
      2875333.63      7009018.90      2875225.11      7009487.70
      2875415.50      7009851.16
#Sta/Elev= 30
  4588.0  409.76  4692.3  409.87  4697.4  408.85  4735.0  409.86  4740.1  408.66
  4758.5  408.81  4768.8  407.67  4777.7  408.69  4782.8  407.80  4825.4  407.74
  4830.6  406.58  4850.9  406.22  4881.7  403.85  4903.7  400.72  4919.7  399.21
  4920.2  398.41  4925.2  398.41  4925.7  399.21  5075.8  399.21  5101.7  400.72
  5118.8  401.82  5191.7  406.90  5208.1  406.67  5213.8  407.56  5230.2  407.12
  5235.9  407.94  5246.6  407.58  5325.8  410.54  5379.0  411.08  5479.5  410.58
#Mann=5,-1,0
  4588.0    0.16       0  4825.4    0.05       0  4919.7   0.033       0
  4925.7    0.05       0  5118.8    0.16       0
Bank Sta=4903.7,5101.7
Exp/Cntr=0.3,0.1

Type RM Length L Ch R = 1,2213,441,441,441
BEGIN DESCRIPTION:
UNT 116 in Running Cr Watershed 5.0
END DESCRIPTION:
XS GIS Cut Line= 3
      2874974.99      7008925.02      2874877.89      7009175.20
      2874825.80      7009665.68
#Sta/Elev= 30
  4623.3  409.33  4676.9  409.62  4709.1  408.41  4722.6  408.22  4741.3  408.55
  4771.7  407.83  4777.1  407.37  4792.4  407.16  4816.4  406.27  4826.1  404.74
  4837.8  403.43  4861.4  402.58  4881.1  400.49  4885.9  399.21  4886.4  398.41
  4891.4  398.41  4891.9  399.21  4896.1  399.21  5132.8  399.21  5141.2  400.49
  5151.8  402.09  5156.9  401.98  5163.0  403.19  5177.7  404.62  5223.3  408.23
  5263.5  409.81  5313.8  410.47  5342.1  410.41  5354.1  409.85  5384.9  410.27
#Mann=6,-1,0
  4623.3     0.1       0  4792.4    0.16       0  4885.9   0.033       0
  4891.9    0.16       0  4896.1    0.05       0  5177.7    0.16       0
Bank Sta=4881.1,5141.2
Exp/Cntr=0.3,0.1

Type RM Length L Ch R = 1,1772,415,415,415
BEGIN DESCRIPTION:
UNT 116 in Running Cr Watershed 4.0
END DESCRIPTION:
XS GIS Cut Line= 3
      2875025.49      7008710.77      2874475.00      7009075.00
      2874279.48      7009473.55
#Sta/Elev= 30
  4423.0  410.62  4455.7  411.06  4497.8  409.93  4564.7  409.73  4579.1  409.81
  4600.1  407.10  4627.4  406.13  4714.5  407.53  4731.6  406.60  4750.6  406.34
  4780.7  401.60  4796.4  400.22  4798.7  399.21  4799.2  398.41  4804.2  398.41
  4804.7  399.21  4852.3  399.21  5159.0  399.21  5164.6  400.12  5181.8  400.22
  5209.6  402.30  5226.5  402.34  5232.0  403.51  5239.0  402.63  5244.1  403.73
  5254.5  405.67  5271.5  405.81  5299.5  408.35  5367.0  409.86  5527.0  411.02
#Mann=7,-1,0
  4423.0    0.16       0  4564.7     0.1       0  4731.6    0.16       0
  4798.7   0.033       0  4804.7    0.16       0  4852.3    0.05       0
  5244.1    0.16       0
Bank Sta=4796.4,5181.8
Exp/Cntr=0.3,0.1

Type RM Length L Ch R = 1,1357,0,0,0
BEGIN DESCRIPTION:
UNT 116 in Running Cr Watershed 3.0
END DESCRIPTION:
XS GIS Cut Line= 4
      2874999.45      7008446.03      2874525.00      7008525.00
      2874287.51      7008796.42      2874209.85      7009328.95
#Sta/Elev= 30
  4367.5  411.26  4422.7  410.80  4516.3  408.25  4544.4  408.80  4577.1  408.14
  4619.7  408.49  4632.9  408.37  4638.0  407.51  4655.9  407.80  4686.3  406.70
  4750.7  400.80  4758.1  399.59  4764.4  399.21  4764.9  398.41  4769.9  398.41
  4770.4  399.21  5347.5  399.59  5389.6  402.00  5397.2  403.61  5402.3  402.12
  5409.8  403.47  5450.2  404.90  5467.2  407.16  5472.3  405.64  5482.6  407.04
  5531.1  409.11  5542.3  408.33  5612.3  408.02  5652.4  410.08  5747.3  410.95
#Mann=6,-1,0
  4367.5    0.12       0  4619.7    0.16       0  4750.7    0.05       0
  4764.4   0.033       0  4770.4    0.05       0  5482.6    0.16       0
Bank Sta=4758.1,5347.5
Exp/Cntr=0.3,0.1

Chan Stop Cuts=-1