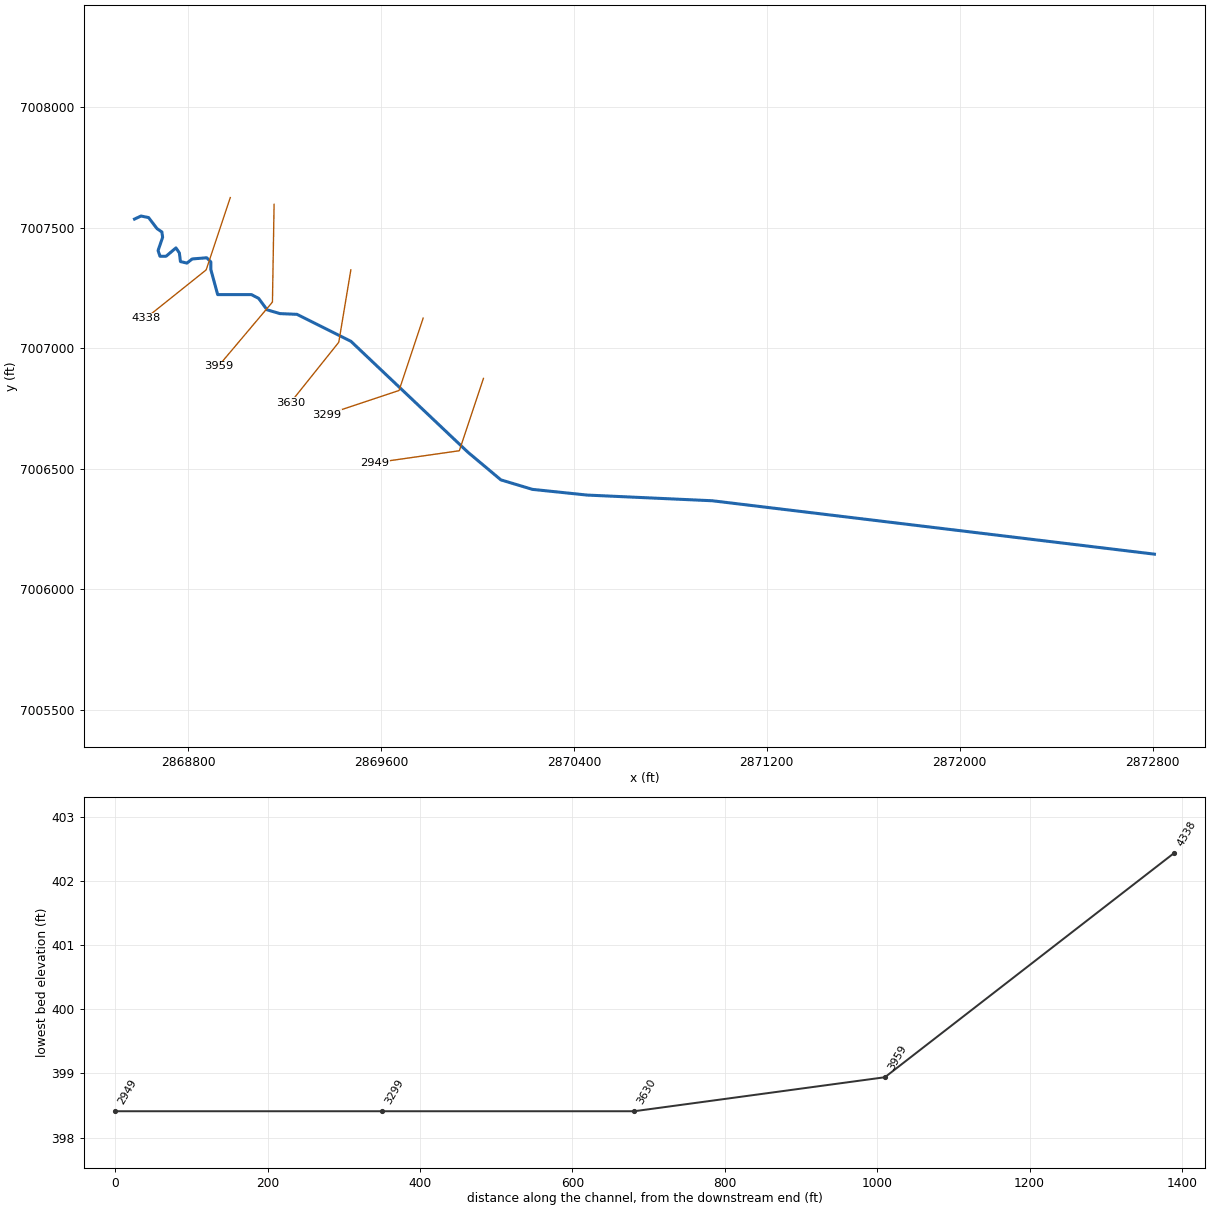
--- UNT 117 in Running Cr Watershed.prj (project) ---

Proj Title=UNT 117 in Running Cr Watershed Base Level Engineering
Current Plan=p01
Default Exp/Contr=0.3,0.1
English Units
Geom File=g01
Flow File=f01
Plan File=p01
BEGIN DESCRIPTION:
UNT 117 in Running Cr Watershed
END DESCRIPTION:

--- UNT 117 in Running Cr Watershed.p01 (plan) ---

Plan Title=Multiple Run
Short Identifier=Multiple
Geom File=g01
Flow File=f01
Subcritical Flow
K Sum by GR= 0
Std Step Tol= 0.01
Critical Tol= 0.01
Num of Std Step Trials= 20
Max Error Tol= 0.3
Flow Tol Ratio= 0.001
Split Flow NTrial= 30
Split Flow Tol= 0.02
Split Flow Ratio= 0.02
Log Output Level= 0
Friction Slope Method= 1
Unsteady Friction Slope Method= 2
Unsteady Bridges Friction Slope Method= 1
Parabolic Critical Depth
Global Vel Dist=  1 , 1 , 1
Global Log Level= 0
CheckData=True
Encroach Param= -1, 0, 0, 0
BEGIN DESCRIPTION:
Multiple Run
END DESCRIPTION:

--- UNT 117 in Running Cr Watershed.f01 (steady flow) ---

Flow Title=Multiple
Number of Profiles=7
Profile Names=10-year,25-year,50-year,1pct_min,100-year,1pct_plu,500-year
River Rch & RM= UNT 117 in Runni,Reach-1,4338
     342     440     517     303     604    1205     823
Boundary for River Rch & Prof#=UNT 117 in Runni,Reach-1,1
Up Type=0
Dn Type=3
Dn Slope=0.005
Boundary for River Rch & Prof#=UNT 117 in Runni,Reach-1,2
Up Type=0
Dn Type=3
Dn Slope=0.005
Boundary for River Rch & Prof#=UNT 117 in Runni,Reach-1,3
Up Type=0
Dn Type=3
Dn Slope=0.005
Boundary for River Rch & Prof#=UNT 117 in Runni,Reach-1,4
Up Type=0
Dn Type=3
Dn Slope=0.005
Boundary for River Rch & Prof#=UNT 117 in Runni,Reach-1,5
Up Type=0
Dn Type=3
Dn Slope=0.005
Boundary for River Rch & Prof#=UNT 117 in Runni,Reach-1,6
Up Type=0
Dn Type=3
Dn Slope=0.005
Boundary for River Rch & Prof#=UNT 117 in Runni,Reach-1,7
Up Type=0
Dn Type=3
Dn Slope=0.005

--- UNT 117 in Running Cr Watershed.g01 (geometry) ---

Geom Title=Existing Conditions

River Reach=UNT 117 in Runni,Reach-1
Reach XY= 30
      2868577.90      7007535.82      2868604.67      7007548.41
      2868636.16      7007542.11      2868670.80      7007496.46
      2868691.27      7007482.28      2868694.41      7007460.24
      2868675.52      7007405.14      2868683.39      7007381.52
      2868708.58      7007381.52      2868749.52      7007416.16
      2868763.69      7007395.69      2868768.41      7007359.48
      2868795.18      7007353.18      2868817.22      7007370.50
      2868877.05      7007375.22      2868894.37      7007357.90
      2868894.37      7007326.41      2868922.71      7007222.50
      2869062.84      7007222.50      2869092.76      7007206.75
      2869127.40      7007159.52      2869180.93      7007143.77
      2869251.78      7007140.62      2869475.36      7007028.83
      2869960.30      7006569.09      2870097.28      7006454.15
      2870227.96      7006414.79      2870454.68      7006391.17
      2870974.26      7006367.55      2872807.71      7006146.12

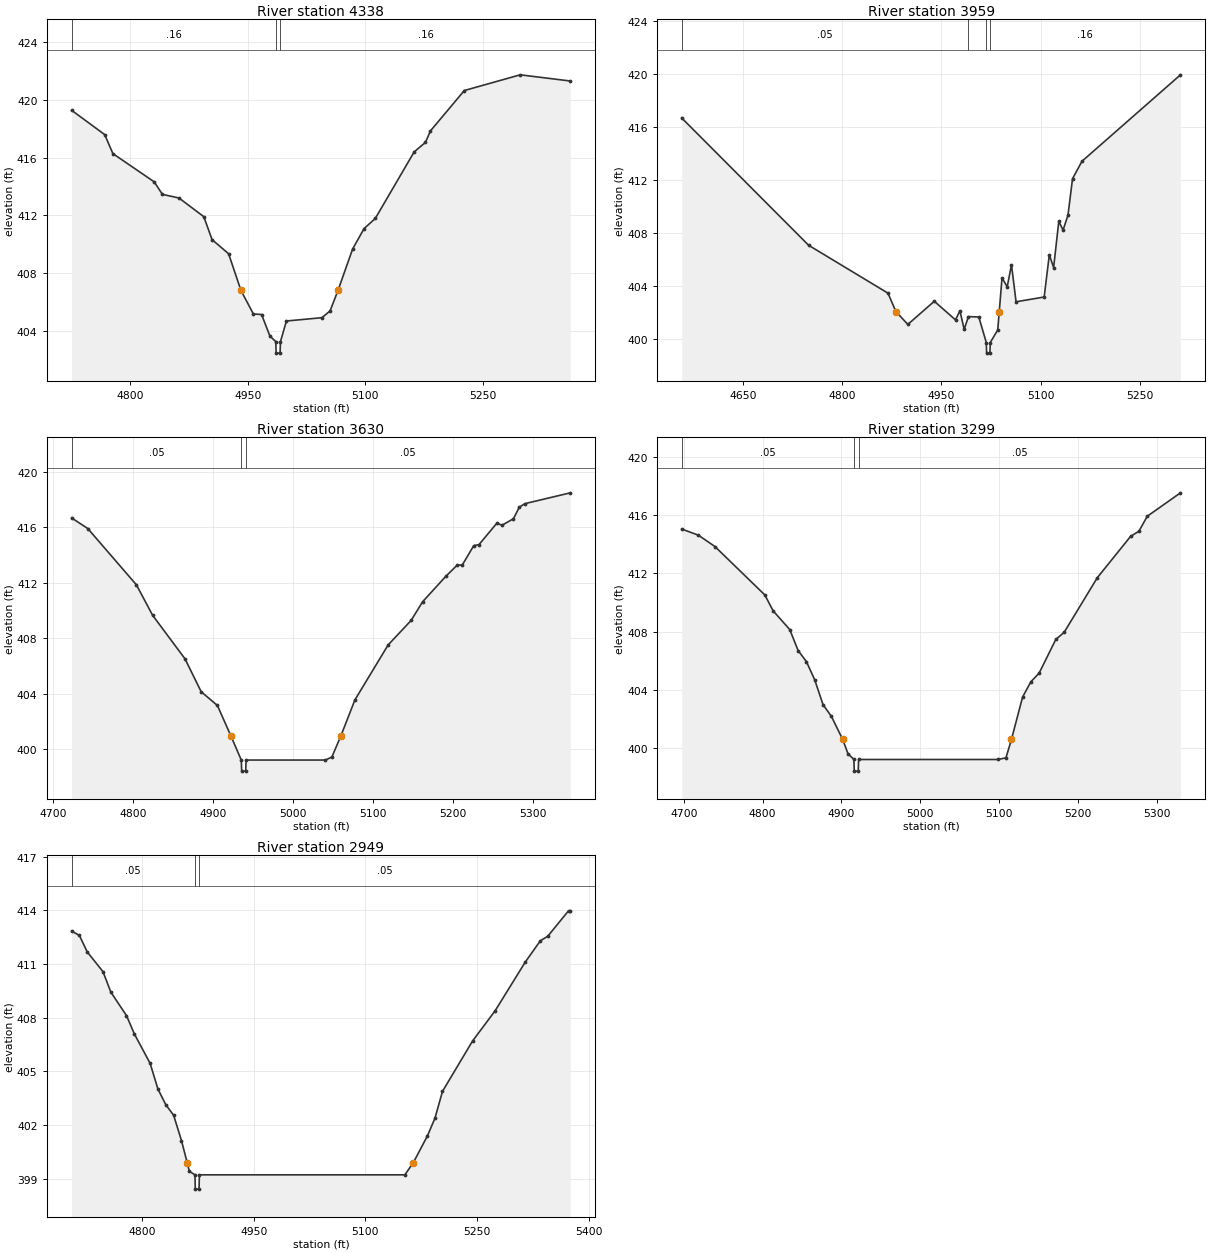
Type RM Length L Ch R = 1,4338,379,379,379
BEGIN DESCRIPTION:
UNT 117 in Running Cr Watershed 12.0
END DESCRIPTION:
XS GIS Cut Line= 3
      2868975.00      7007625.00      2868875.00      7007325.00
      2868624.99      7007124.99
#Sta/Elev= 30
  4725.1  419.29  4767.3  417.60  4777.8  416.28  4830.5  414.32  4841.0  413.45
  4862.1  413.20  4893.8  411.90  4904.3  410.31  4925.4  409.33  4941.2  406.78
  4957.0  405.15  4967.5  405.11  4978.1  403.62  4985.6  403.23  4986.1  402.43
  4991.1  402.43  4991.6  403.23  4999.2  404.66  5044.5  404.89  5054.9  405.36
  5065.0  406.78  5083.7  409.66  5098.2  411.07  5112.6  411.78  5162.2  416.40
  5176.6  417.06  5183.0  417.86  5226.2  420.66  5297.5  421.75  5361.5  421.32
#Mann=3,-1,0
  4725.1    0.16       0  4985.6    0.07       0  4991.6    0.16       0
Bank Sta=4941.2,5065
Exp/Cntr=0.3,0.1

Type RM Length L Ch R = 1,3959,329,329,329
BEGIN DESCRIPTION:
UNT 117 in Running Cr Watershed 11.0
END DESCRIPTION:
XS GIS Cut Line= 3
      2869156.68      7007596.88      2869149.86      7007191.57
      2868925.01      7006925.01
#Sta/Elev= 30
  4557.4  416.71  4749.3  407.09  4869.3  403.47  4881.2  402.08  4899.3  401.11
  4939.3  402.86  4971.4  401.45  4978.0  402.14  4984.5  400.74  4990.9  401.70
  5006.6  401.67  5017.9  399.74  5018.4  398.94  5023.4  398.94  5023.9  399.74
  5035.2  400.69  5037.5  402.08  5041.7  404.63  5049.5  403.95  5056.0  405.61
  5062.9  402.82  5105.4  403.18  5113.2  406.37  5119.7  405.41  5127.5  408.89
  5134.0  408.24  5141.4  409.36  5148.3  412.12  5162.6  413.44  5311.5  419.97
#Mann=4,-1,0
  4557.4    0.05       0  4990.9    0.16       0  5017.9    0.07       0
  5023.9    0.16       0
Bank Sta=4881.2,5037.5
Exp/Cntr=0.3,0.1

Type RM Length L Ch R = 1,3630,331,331,331
BEGIN DESCRIPTION:
UNT 117 in Running Cr Watershed 10.0
END DESCRIPTION:
XS GIS Cut Line= 3
      2869475.00      7007325.01      2869425.00      7007025.00
      2869225.00      7006775.00
#Sta/Elev= 30
  4723.0  416.69  4743.3  415.92  4804.1  411.86  4824.4  409.66  4864.9  406.52
  4885.2  404.14  4905.5  403.15  4922.3  400.96  4935.4  399.21  4935.9  398.41
  4940.9  398.41  4941.4  399.21  5040.8  399.21  5048.8  399.43  5060.1  400.96
  5077.6  403.55  5119.2  407.52  5148.0  409.29  5162.4  410.64  5191.2  412.46
  5205.6  413.28  5212.0  413.29  5226.4  414.69  5232.9  414.76  5255.3  416.31
  5261.7  416.16  5276.1  416.63  5283.3  417.46  5290.5  417.72  5347.3  418.50
#Mann=3,-1,0
  4723.0    0.05       0  4935.4   0.033       0  4941.4    0.05       0
Bank Sta=4922.3,5060.1
Exp/Cntr=0.3,0.1

Type RM Length L Ch R = 1,3299,350,350,350
BEGIN DESCRIPTION:
UNT 117 in Running Cr Watershed 9.0
END DESCRIPTION:
XS GIS Cut Line= 3
      2869774.99      7007124.98      2869675.00      7006825.00
      2869375.04      7006725.01
#Sta/Elev= 30
  4697.5  415.05  4718.6  414.63  4739.6  413.85  4802.9  410.52  4813.4  409.43
  4834.5  408.14  4845.1  406.70  4855.6  405.94  4866.1  404.69  4876.7  402.98
  4887.2  402.18  4901.6  400.59  4908.3  399.61  4915.8  399.21  4916.3  398.41
  4921.3  398.41  4921.8  399.21  5098.0  399.21  5108.6  399.32  5115.6  400.59
  5129.7  403.50  5140.2  404.55  5150.7  405.15  5171.8  407.46  5182.4  407.95
  5224.5  411.71  5266.7  414.55  5277.2  414.90  5287.8  415.93  5329.9  417.54
#Mann=3,-1,0
  4697.5    0.05       0  4915.8   0.033       0  4921.8    0.05       0
Bank Sta=4901.6,5115.6
Exp/Cntr=0.3,0.1

Type RM Length L Ch R = 1,2949,0,0,0
BEGIN DESCRIPTION:
UNT 117 in Running Cr Watershed 8.0
END DESCRIPTION:
XS GIS Cut Line= 3
      2870024.98      7006874.95      2869925.00      7006575.00
      2869575.03      7006525.00
#Sta/Elev= 30
  4705.5  412.85  4716.0  412.60  4726.5  411.68  4747.6  410.58  4758.2  409.43
  4779.2  408.12  4789.8  407.09  4810.9  405.45  4821.4  404.01  4831.9  403.14
  4842.5  402.54  4853.0  401.13  4860.7  399.89  4863.6  399.41  4871.1  399.21
  4871.6  398.41  4876.6  398.41  4877.1  399.21  5153.0  399.21  5164.3  399.89
  5183.3  401.39  5193.4  402.38  5203.5  403.88  5243.9  406.70  5274.2  408.39
  5314.6  411.11  5334.8  412.30  5344.9  412.56  5372.7  413.98  5375.2  413.98
#Mann=3,-1,0
  4705.5    0.05       0  4871.1   0.033       0  4877.1    0.05       0
Bank Sta=4860.7,5164.3
Exp/Cntr=0.3,0.1

Chan Stop Cuts=-1