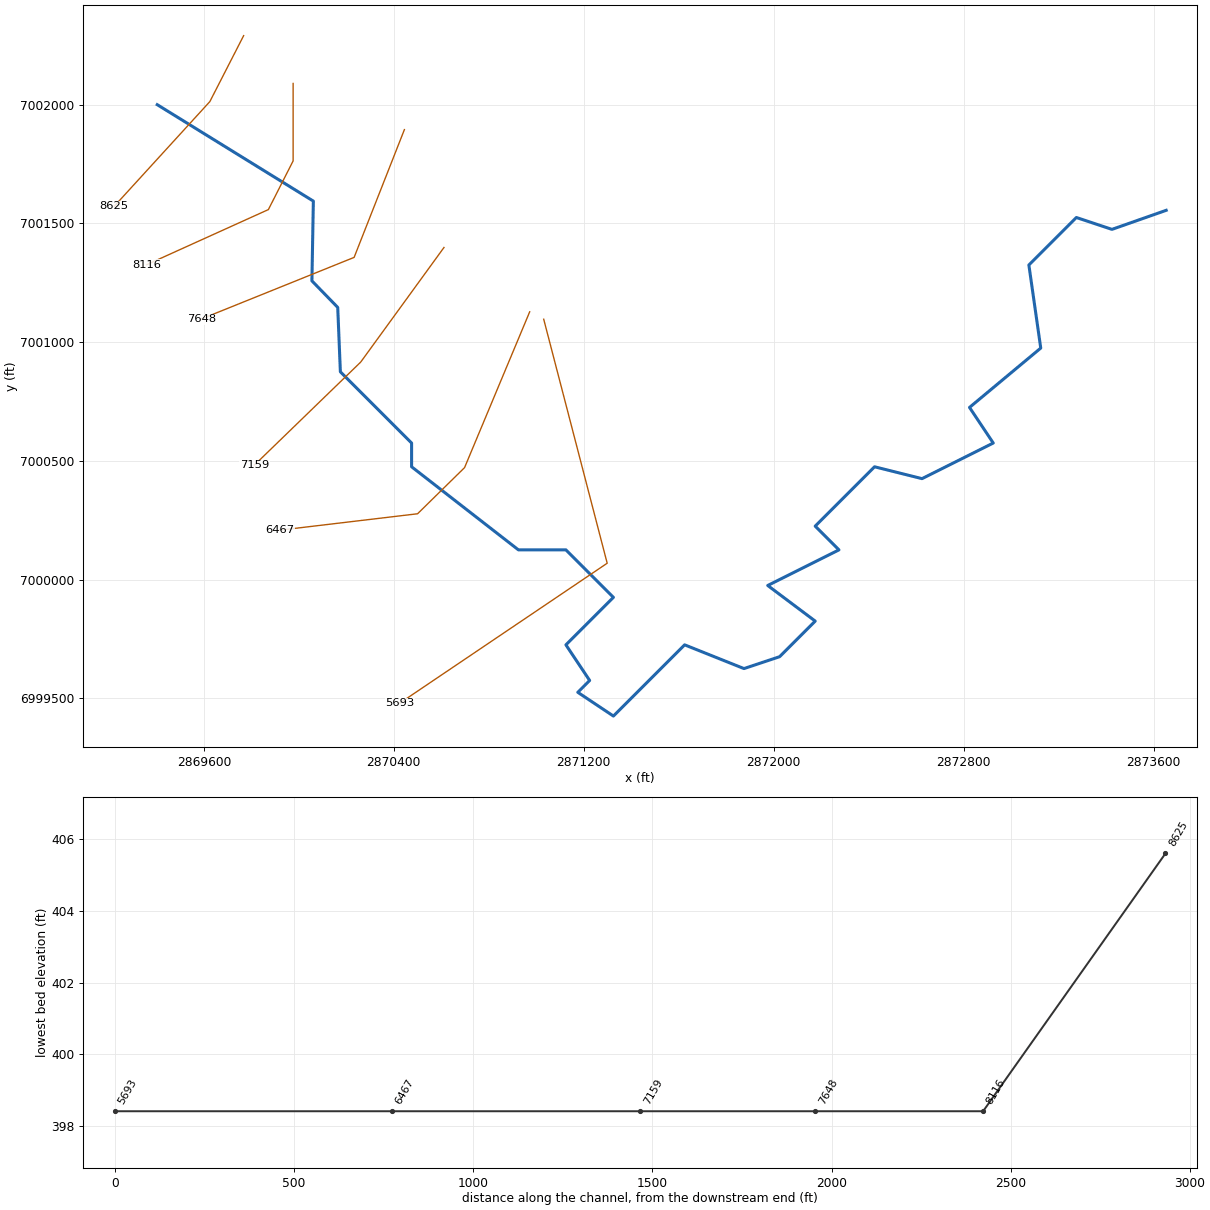
--- UNT 118 in Running Cr Watershed.prj (project) ---

Proj Title=UNT 118 in Running Cr Watershed Base Level Engineering
Current Plan=p01
Default Exp/Contr=0.3,0.1
English Units
Geom File=g01
Flow File=f01
Plan File=p01
BEGIN DESCRIPTION:
UNT 118 in Running Cr Watershed
END DESCRIPTION:

--- UNT 118 in Running Cr Watershed.p01 (plan) ---

Plan Title=Multiple Run
Short Identifier=Multiple
Geom File=g01
Flow File=f01
Subcritical Flow
K Sum by GR= 0
Std Step Tol= 0.01
Critical Tol= 0.01
Num of Std Step Trials= 20
Max Error Tol= 0.3
Flow Tol Ratio= 0.001
Split Flow NTrial= 30
Split Flow Tol= 0.02
Split Flow Ratio= 0.02
Log Output Level= 0
Friction Slope Method= 1
Unsteady Friction Slope Method= 2
Unsteady Bridges Friction Slope Method= 1
Parabolic Critical Depth
Global Vel Dist=  1 , 1 , 1
Global Log Level= 0
CheckData=True
Encroach Param= -1, 0, 0, 0
BEGIN DESCRIPTION:
Multiple Run
END DESCRIPTION:

--- UNT 118 in Running Cr Watershed.f01 (steady flow) ---

Flow Title=Multiple
Number of Profiles=7
Profile Names=10-year,25-year,50-year,1pct_min,100-year,1pct_plu,500-year
River Rch & RM= UNT 118 in Runni,Reach-1,8625
     201     247     281     159     318     634     406
Boundary for River Rch & Prof#=UNT 118 in Runni,Reach-1,1
Up Type=0
Dn Type=3
Dn Slope=0.005
Boundary for River Rch & Prof#=UNT 118 in Runni,Reach-1,2
Up Type=0
Dn Type=3
Dn Slope=0.005
Boundary for River Rch & Prof#=UNT 118 in Runni,Reach-1,3
Up Type=0
Dn Type=3
Dn Slope=0.005
Boundary for River Rch & Prof#=UNT 118 in Runni,Reach-1,4
Up Type=0
Dn Type=3
Dn Slope=0.005
Boundary for River Rch & Prof#=UNT 118 in Runni,Reach-1,5
Up Type=0
Dn Type=3
Dn Slope=0.005
Boundary for River Rch & Prof#=UNT 118 in Runni,Reach-1,6
Up Type=0
Dn Type=3
Dn Slope=0.005
Boundary for River Rch & Prof#=UNT 118 in Runni,Reach-1,7
Up Type=0
Dn Type=3
Dn Slope=0.005

--- UNT 118 in Running Cr Watershed.g01 (geometry) ---

Geom Title=Existing Conditions

River Reach=UNT 118 in Runni,Reach-1
Reach XY= 30
      2869403.54      7002000.24      2870061.17      7001593.99
      2870055.10      7001258.06      2870163.80      7001146.35
      2870175.00      7000875.00      2870475.00      7000575.00
      2870475.00      7000475.00      2870925.00      7000125.00
      2871125.00      7000125.00      2871325.00      6999925.00
      2871125.00      6999725.00      2871225.00      6999575.00
      2871175.00      6999525.00      2871325.00      6999425.00
      2871625.00      6999725.00      2871875.00      6999625.00
      2872025.00      6999675.00      2872175.00      6999825.00
      2871975.00      6999975.00      2872275.00      7000125.00
      2872175.00      7000225.00      2872425.00      7000475.00
      2872625.00      7000425.00      2872925.00      7000575.00
      2872825.00      7000725.00      2873125.00      7000975.00
      2873075.00      7001325.00      2873275.00      7001525.00
      2873425.00      7001475.00      2873653.40      7001555.28

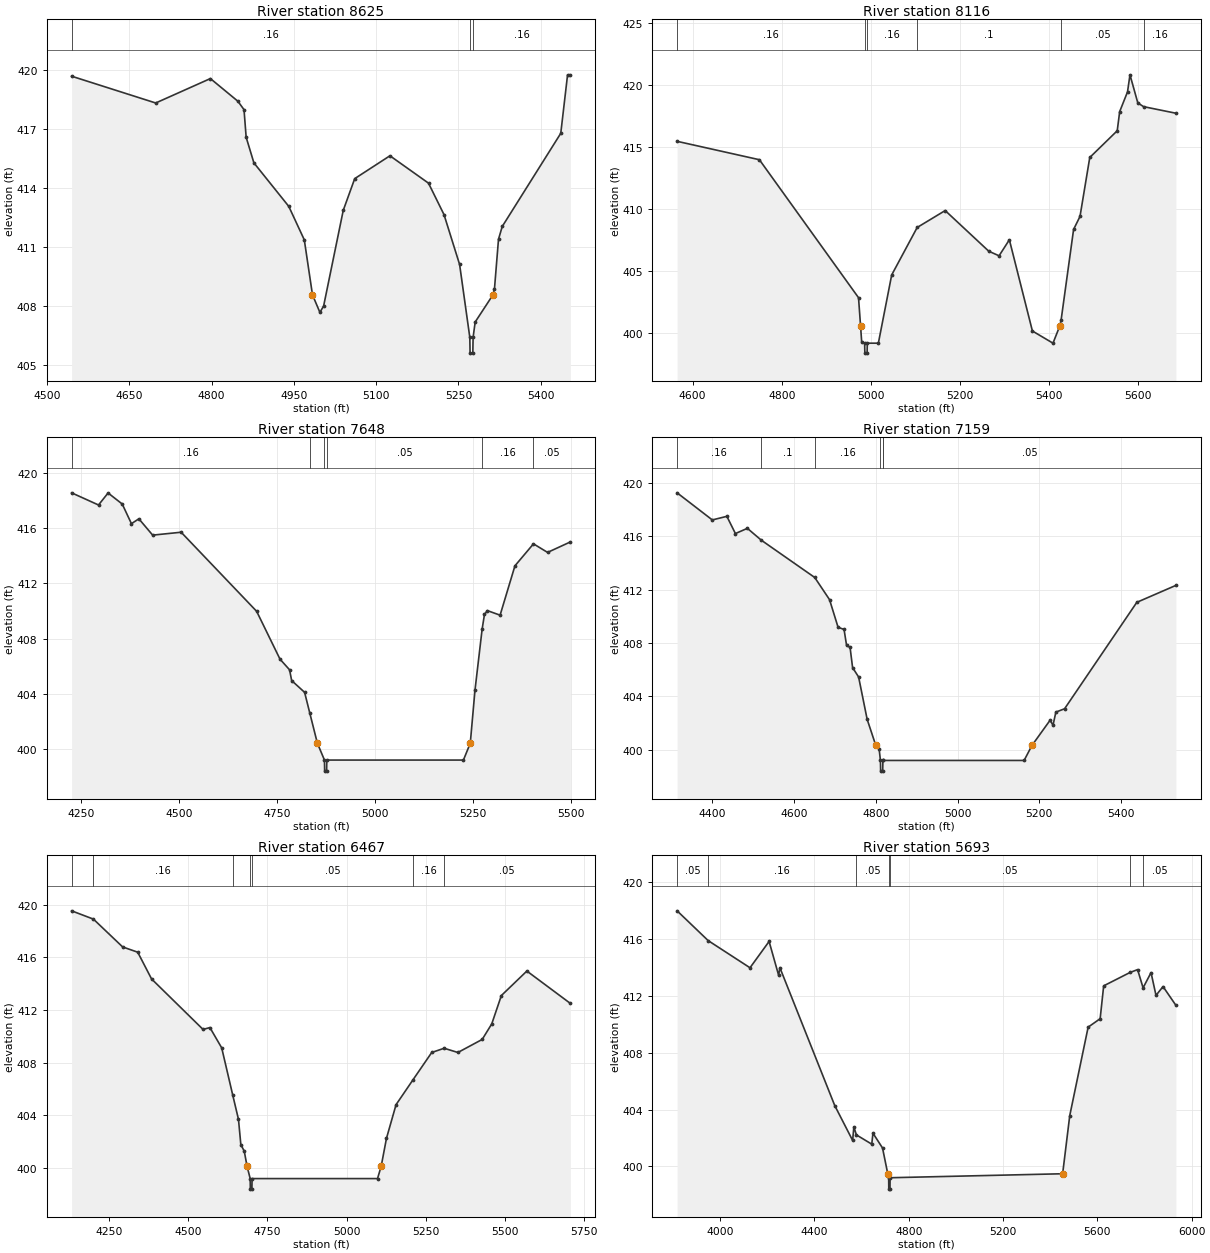
Type RM Length L Ch R = 1,8625,509,509,509
BEGIN DESCRIPTION:
UNT 118 in Running Cr Watershed 4.0
END DESCRIPTION:
XS GIS Cut Line= 3
      2869767.56      7002290.98      2869625.22      7002013.23
      2869222.46      7001572.28
#Sta/Elev= 30
  4544.8  419.66  4698.1  418.30  4797.8  419.54  4847.9  418.39  4859.1  417.96
  4863.0  416.56  4877.1  415.26  4940.7  413.05  4969.0  411.35  4983.9  408.56
  4997.4  407.67  5004.2  407.99  5040.0  412.85  5060.9  414.46  5125.1  415.62
  5195.4  414.23  5223.7  412.63  5252.1  410.10  5270.7  406.40  5271.2  405.60
  5276.2  405.60  5276.7  406.40  5280.5  407.18  5312.9  408.56  5315.6  408.84
  5323.0  411.38  5329.8  412.03  5436.5  416.76  5448.9  419.73  5454.1  419.73
#Mann=3,-1,0
  4544.8    0.16       0  5270.7    0.07       0  5276.7    0.16       0
Bank Sta=4983.9,5312.9
Exp/Cntr=0.3,0.1

Type RM Length L Ch R = 1,8116,468,468,468
BEGIN DESCRIPTION:
Mapping XS 2eac2cab
END DESCRIPTION:
XS GIS Cut Line= 4
      2869975.91      7002089.58      2869975.91      7001763.23
      2869871.75      7001558.37      2869358.92      7001326.21
#Sta/Elev= 30
  4565.2  415.45  4749.8  413.97  4972.2  402.87  4976.7  400.63  4979.3  399.30
  4985.9  399.21  4986.4  398.41  4991.4  398.41  4991.9  399.21  5016.7  399.21
  5046.6  404.70  5103.8  408.52  5166.6  409.88  5264.4  406.61  5287.5  406.24
  5310.6  407.53  5362.3  400.19  5408.5  399.21  5424.1  400.63  5426.7  401.07
  5454.7  408.36  5469.1  409.41  5491.0  414.15  5552.6  416.30  5558.1  417.84
  5575.7  419.43  5581.2  420.80  5598.8  418.54  5611.7  418.24  5684.3  417.71
#Mann=6,-1,0
  4565.2    0.16       0  4985.9    0.07       0  4991.9    0.16       0
  5103.8     0.1       0  5426.7    0.05       0  5611.7    0.16       0
Bank Sta=4976.7,5424.1
Exp/Cntr=0.3,0.1

Type RM Length L Ch R = 1,7648,489,489,489
BEGIN DESCRIPTION:
Mapping XS 3b486694
END DESCRIPTION:
XS GIS Cut Line= 3
      2870444.68      7001895.21      2870232.86      7001356.98
      2869588.49      7001097.15
#Sta/Elev= 30
  4226.2  418.54  4294.9  417.66  4319.3  418.53  4355.4  417.73  4378.9  416.31
  4397.9  416.66  4433.1  415.48  4505.8  415.69  4698.5  409.97  4758.1  406.51
  4782.5  405.74  4787.9  404.96  4820.9  404.11  4833.9  402.64  4853.5  400.43
  4871.6  399.21  4872.1  398.41  4877.1  398.41  4877.6  399.21  5226.3  399.21
  5243.8  400.43  5255.8  404.26  5274.1  408.69  5280.0  409.74  5287.5  410.02
  5319.9  409.69  5357.8  413.26  5405.1  414.85  5441.1  414.23  5499.4  414.99
#Mann=6,-1,0
  4226.2    0.16       0  4833.9    0.05       0  4871.6   0.033       0
  4877.6    0.05       0  5274.1    0.16       0  5405.1    0.05       0
Bank Sta=4853.5,5243.8
Exp/Cntr=0.3,0.1

Type RM Length L Ch R = 1,7159,692,692,692
BEGIN DESCRIPTION:
UNT 118 in Running Cr Watershed 3.0
END DESCRIPTION:
XS GIS Cut Line= 3
      2870611.36      7001398.68      2870260.64      7000916.00
      2869812.75      7000482.01
#Sta/Elev= 30
  4313.8  419.25  4399.9  417.22  4435.5  417.49  4456.4  416.20  4485.7  416.59
  4519.9  415.70  4650.5  412.91  4686.7  411.25  4707.6  409.18  4722.2  409.02
  4728.4  407.82  4736.9  407.68  4743.1  406.16  4757.8  405.46  4778.7  402.29
  4799.9  400.33  4808.0  400.07  4811.2  399.21  4811.7  398.41  4816.7  398.41
  4817.2  399.21  4817.6  399.21  5162.7  399.21  5181.8  400.33  5226.2  402.22
  5233.4  401.85  5240.4  402.83  5261.7  403.08  5438.4  411.05  5534.1  412.32
#Mann=6,-1,0
  4313.8    0.16       0  4519.9     0.1       0  4650.5    0.16       0
  4811.2   0.033       0  4817.2    0.16       0  4817.6    0.05       0
Bank Sta=4799.9,5181.8
Exp/Cntr=0.3,0.1

Type RM Length L Ch R = 1,6467,774,774,774
BEGIN DESCRIPTION:
UNT 118 in Running Cr Watershed 2.0
END DESCRIPTION:
XS GIS Cut Line= 4
      2870972.45      7001127.84      2870698.14      7000471.56
      2870500.22      7000277.12      2869918.48      7000207.86
#Sta/Elev= 30
  4131.9  419.53  4200.8  418.90  4293.0  416.79  4340.6  416.39  4384.3  414.36
  4546.8  410.53  4568.5  410.67  4605.7  409.13  4640.6  405.54  4658.7  403.70
  4666.1  401.79  4676.9  401.29  4685.8  400.14  4695.6  399.21  4696.1  398.41
  4701.1  398.41  4701.6  399.21  5097.6  399.21  5109.1  400.14  5125.9  402.27
  5156.1  404.82  5208.5  406.67  5268.7  408.78  5307.9  409.10  5351.3  408.78
  5428.0  409.77  5458.2  410.95  5488.5  413.10  5569.0  414.96  5706.5  412.50
#Mann=7,-1,0
  4131.9    0.05       0  4200.8    0.16       0  4640.6    0.05       0
  4695.6   0.033       0  4701.6    0.05       0  5208.5    0.16       0
  5307.9    0.05       0
Bank Sta=4685.8,5109.1
Exp/Cntr=0.3,0.1

Type RM Length L Ch R = 1,5693,0,0,0
BEGIN DESCRIPTION:
UNT 118 in Running Cr Watershed 1.0
END DESCRIPTION:
XS GIS Cut Line= 3
      2871031.47      7001096.54      2871298.83      7000068.78
      2870424.95      6999479.26
#Sta/Elev= 30
  3817.3  417.96  3948.9  415.87  4126.5  413.96  4207.5  415.81  4248.0  413.43
  4253.2  413.97  4486.0  404.28  4561.9  401.83  4567.1  402.78  4577.8  402.22
  4643.0  401.57  4648.1  402.34  4688.7  401.30  4710.9  399.49  4714.8  399.21
  4715.3  398.41  4720.3  398.41  4720.8  399.21  5452.8  399.49  5483.0  403.58
  5561.0  409.79  5611.9  410.38  5626.9  412.69  5738.7  413.63  5770.8  413.83
  5794.1  412.55  5827.8  413.62  5848.9  412.02  5878.7  412.64  5933.4  411.32
#Mann=7,-1,0
  3817.3    0.05       0  3948.9    0.16       0  4577.8    0.05       0
  4714.8   0.033       0  4720.8    0.05       0  5738.7    0.16       0
  5794.1    0.05       0
Bank Sta=4710.9,5452.8
Exp/Cntr=0.3,0.1

Chan Stop Cuts=-1