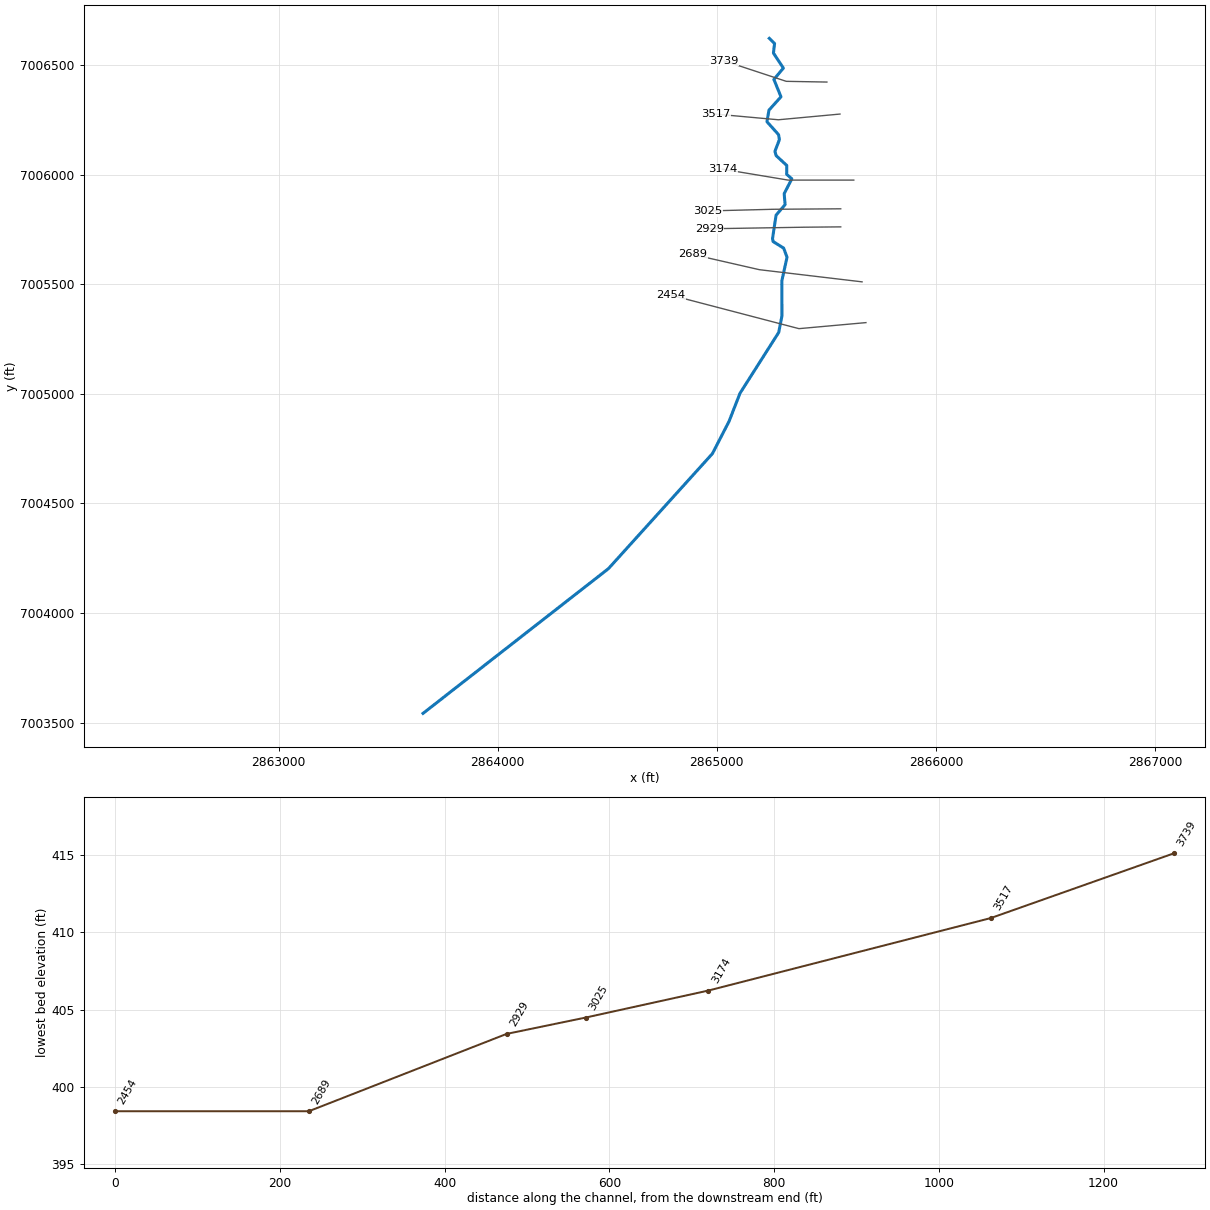
--- UNT 119 in Running Cr Watershed.prj (project) ---

Proj Title=UNT 119 in Running Cr Watershed Base Level Engineering
Current Plan=p01
Default Exp/Contr=0.3,0.1
English Units
Geom File=g01
Flow File=f01
Plan File=p01
BEGIN DESCRIPTION:
UNT 119 in Running Cr Watershed
END DESCRIPTION:

--- UNT 119 in Running Cr Watershed.p01 (plan) ---

Plan Title=Multiple Run
Short Identifier=Multiple
Geom File=g01
Flow File=f01
Subcritical Flow
K Sum by GR= 0
Std Step Tol= 0.01
Critical Tol= 0.01
Num of Std Step Trials= 20
Max Error Tol= 0.3
Flow Tol Ratio= 0.001
Split Flow NTrial= 30
Split Flow Tol= 0.02
Split Flow Ratio= 0.02
Log Output Level= 0
Friction Slope Method= 1
Unsteady Friction Slope Method= 2
Unsteady Bridges Friction Slope Method= 1
Parabolic Critical Depth
Global Vel Dist=  1 , 1 , 1
Global Log Level= 0
CheckData=True
Encroach Param= -1, 0, 0, 0
BEGIN DESCRIPTION:
Multiple Run
END DESCRIPTION:

--- UNT 119 in Running Cr Watershed.f01 (steady flow) ---

Flow Title=Multiple
Number of Profiles=7
Profile Names=10-year,25-year,50-year,1pct_min,100-year,1pct_plu,500-year
River Rch & RM= UNT 119 in Runni,Reach-1,3739
     163     200     228     130     260     519     335
Boundary for River Rch & Prof#=UNT 119 in Runni,Reach-1,1
Up Type=0
Dn Type=3
Dn Slope=0.005
Boundary for River Rch & Prof#=UNT 119 in Runni,Reach-1,2
Up Type=0
Dn Type=3
Dn Slope=0.005
Boundary for River Rch & Prof#=UNT 119 in Runni,Reach-1,3
Up Type=0
Dn Type=3
Dn Slope=0.005
Boundary for River Rch & Prof#=UNT 119 in Runni,Reach-1,4
Up Type=0
Dn Type=3
Dn Slope=0.005
Boundary for River Rch & Prof#=UNT 119 in Runni,Reach-1,5
Up Type=0
Dn Type=3
Dn Slope=0.005
Boundary for River Rch & Prof#=UNT 119 in Runni,Reach-1,6
Up Type=0
Dn Type=3
Dn Slope=0.005
Boundary for River Rch & Prof#=UNT 119 in Runni,Reach-1,7
Up Type=0
Dn Type=3
Dn Slope=0.005

--- UNT 119 in Running Cr Watershed.g01 (geometry) ---

Geom Title=Existing Conditions

River Reach=UNT 119 in Runni,Reach-1
Reach XY= 30
      2865239.45      7006621.83      2865263.41      7006598.39
      2865258.20      7006554.64      2865303.52      7006485.89
      2865260.29      7006434.33      2865292.58      7006355.16
      2865237.89      7006294.23      2865228.52      7006241.62
      2865281.64      7006182.25      2865285.29      7006159.33
      2865264.98      7006106.21      2865270.70      7006086.41
      2865319.14      7006041.62      2865318.62      7006001.52
      2865342.06      7005980.69      2865307.16      7005912.98
      2865311.33      7005862.98      2865270.18      7005815.06
      2865254.04      7005707.77      2865256.75      7005694.51
      2865304.78      7005664.70      2865320.24      7005623.29
      2865296.50      7005515.09      2865297.00      7005355.38
      2865282.18      7005279.79      2865105.80      7005002.63
      2865055.41      7004873.69      2864979.82      7004726.96
      2864505.54      7004202.28      2863659.32      7003541.73

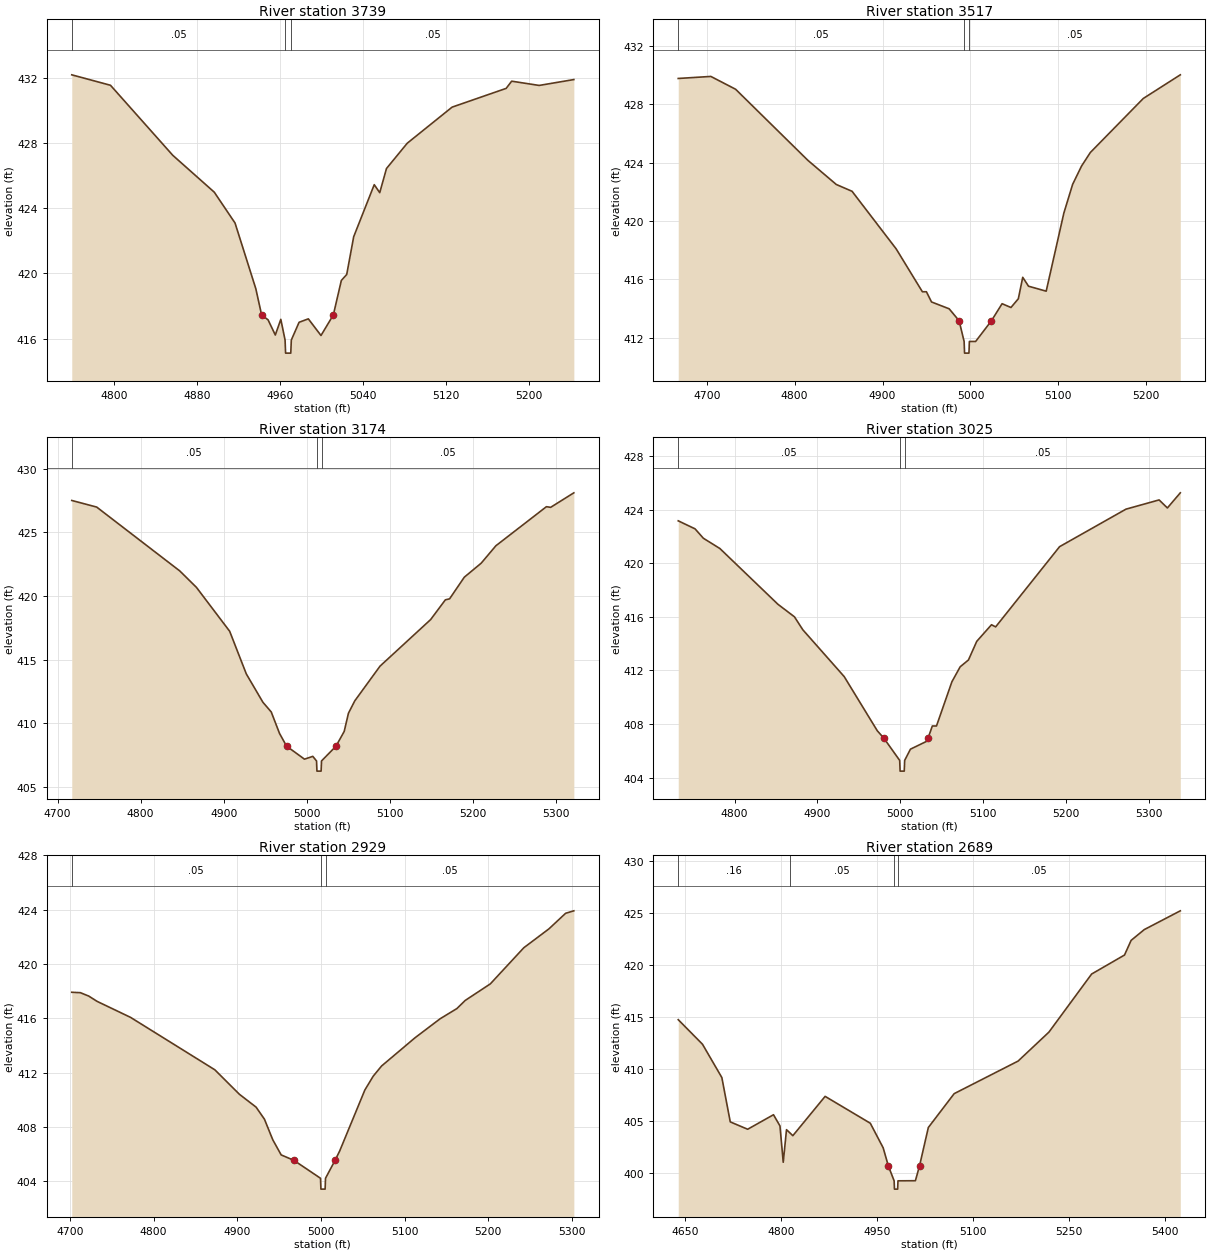
Type RM Length L Ch R = 1,3739,222,222,222
BEGIN DESCRIPTION:
UNT 119 in Running Cr Watershed 8.0
END DESCRIPTION:
XS GIS Cut Line= 3
      2865502.29      7006422.36      2865316.78      7006425.62
      2865033.60      7006518.93
#Sta/Elev= 30
  4759.3  432.17  4796.6  431.53  4856.6  427.24  4896.6  424.98  4916.6  423.09
  4936.6  419.07  4942.2  417.46  4948.4  417.16  4955.4  416.23  4960.7  417.19
  4964.8  415.92  4965.3  415.12  4970.3  415.12  4970.8  415.92  4978.3  417.01
  4987.2  417.22  4999.4  416.20  5011.3  417.46  5019.0  419.57  5024.2  419.94
  5030.9  422.25  5050.7  425.44  5056.0  424.95  5062.5  426.43  5082.5  427.98
  5125.7  430.19  5177.8  431.34  5183.1  431.78  5209.6  431.52  5243.0  431.88
#Mann=3,-1,0
  4759.3    0.05       0  4964.8    0.03       0  4970.8    0.05       0
Bank Sta=4942.2,5011.3
Exp/Cntr=0.3,0.1

Type RM Length L Ch R = 1,3517,343,343,343
BEGIN DESCRIPTION:
Mapping XS bb09c8ce
END DESCRIPTION:
XS GIS Cut Line= 3
      2865561.96      7006276.31      2865280.75      7006250.27
      2864993.03      7006276.31
#Sta/Elev= 30
  4667.5  429.77  4704.6  429.91  4732.8  429.03  4815.1  424.15  4847.3  422.50
  4865.3  422.03  4915.5  418.08  4945.3  415.14  4949.9  415.14  4955.7  414.44
  4975.8  413.97  4987.1  413.15  4992.8  411.73  4993.3  410.93  4998.3  410.93
  4998.8  411.73  5005.9  411.73  5023.9  413.15  5036.0  414.32  5046.1  414.06
  5054.5  414.66  5059.5  416.13  5066.1  415.52  5086.2  415.18  5106.3  420.54
  5116.3  422.51  5126.4  423.76  5136.4  424.69  5196.7  428.40  5238.8  430.02
#Mann=3,-1,0
  4667.5    0.05       0  4992.8    0.03       0  4998.8    0.05       0
Bank Sta=4987.1,5023.9
Exp/Cntr=0.3,0.1

Type RM Length L Ch R = 1,3174,149,149,149
BEGIN DESCRIPTION:
UNT 119 in Running Cr Watershed 7.0
END DESCRIPTION:
XS GIS Cut Line= 3
      2865624.96      7005975.00      2865325.00      7005975.00
      2865025.00      7006025.00
#Sta/Elev= 30
  4717.1  427.50  4747.1  426.98  4847.1  421.96  4867.1  420.67  4907.1  417.22
  4927.1  413.87  4947.1  411.64  4957.1  410.88  4967.1  409.19  4975.6  408.19
  4997.1  407.17  5007.1  407.39  5011.6  407.03  5012.1  406.23  5017.1  406.23
  5017.6  407.03  5035.0  408.19  5044.9  409.35  5050.0  410.78  5057.6  411.75
  5088.0  414.48  5148.9  418.14  5166.6  419.69  5171.7  419.77  5189.4  421.47
  5209.7  422.57  5227.4  423.94  5288.2  427.01  5293.3  426.96  5321.2  428.10
#Mann=3,-1,0
  4717.1    0.05       0  5011.6    0.03       0  5017.6    0.05       0
Bank Sta=4975.6,5035
Exp/Cntr=0.3,0.1

Type RM Length L Ch R = 1,3025,96,96,96
BEGIN DESCRIPTION:
Mapping XS e98980e8
END DESCRIPTION:
XS GIS Cut Line= 3
      2865565.28      7005844.02      2865257.10      7005841.85
      2864959.38      7005834.27
#Sta/Elev= 30
  4732.0  423.17  4752.3  422.57  4762.3  421.87  4782.3  421.10  4852.3  416.94
  4872.3  416.00  4882.3  415.04  4932.3  411.54  4972.3  407.49  4980.2  406.94
  4999.3  405.28  4999.8  404.48  5004.8  404.48  5005.3  405.28  5012.3  406.12
  5032.3  406.72  5033.5  406.94  5038.7  407.85  5043.7  407.85  5062.3  411.15
  5072.3  412.27  5082.3  412.78  5092.3  414.17  5110.1  415.41  5115.1  415.25
  5192.3  421.24  5272.4  424.04  5312.4  424.73  5322.4  424.13  5338.0  425.26
#Mann=3,-1,0
  4732.0    0.05       0  4999.3    0.03       0  5005.3    0.05       0
Bank Sta=4980.2,5033.5
Exp/Cntr=0.3,0.1

Type RM Length L Ch R = 1,2929,240,240,240
BEGIN DESCRIPTION:
UNT 119 in Running Cr Watershed 6.0
END DESCRIPTION:
XS GIS Cut Line= 3
      2865565.27      7005761.56      2865400.76      7005760.04
      2864965.23      7005752.88
#Sta/Elev= 30
  4702.1  417.92  4712.4  417.89  4722.4  417.64  4732.4  417.25  4772.4  416.07
  4873.1  412.21  4902.4  410.41  4922.4  409.46  4932.4  408.57  4942.4  407.05
  4952.4  405.94  4967.6  405.54  4999.4  404.22  4999.9  403.42  5004.9  403.42
  5005.4  404.22  5016.8  405.54  5022.4  406.24  5052.4  410.72  5062.4  411.74
  5072.4  412.49  5112.4  414.57  5142.4  415.97  5162.4  416.72  5172.4  417.32
  5202.4  418.54  5242.4  421.20  5272.4  422.59  5292.4  423.74  5302.2  423.92
#Mann=3,-1,0
  4702.1    0.05       0  4999.4    0.04       0  5005.4    0.05       0
Bank Sta=4967.6,5016.8
Exp/Cntr=0.3,0.1

Type RM Length L Ch R = 1,2689,235,235,235
BEGIN DESCRIPTION:
Mapping XS 06a87791
END DESCRIPTION:
XS GIS Cut Line= 3
      2865662.68      7005510.69      2865193.95      7005566.24
      2864890.09      7005635.70
#Sta/Elev= 30
  4639.6  414.74  4677.5  412.37  4707.7  409.16  4720.8  404.89  4748.0  404.18
  4788.3  405.58  4798.4  404.50  4803.5  401.00  4808.6  404.14  4814.3  403.81
  4818.5  403.56  4868.9  407.35  4939.4  404.76  4959.5  402.39  4967.6  400.64
  4976.6  399.21  4977.1  398.41  4982.1  398.41  4982.6  399.21  5009.8  399.22
  5016.2  400.64  5030.0  404.35  5070.3  407.61  5170.1  410.75  5218.2  413.54
  5284.9  419.14  5336.2  420.97  5346.5  422.38  5367.0  423.42  5423.3  425.23
#Mann=4,-1,0
  4639.6    0.16       0  4814.3    0.05       0  4976.6    0.03       0
  4982.6    0.05       0
Bank Sta=4967.6,5016.2
Exp/Cntr=0.3,0.1

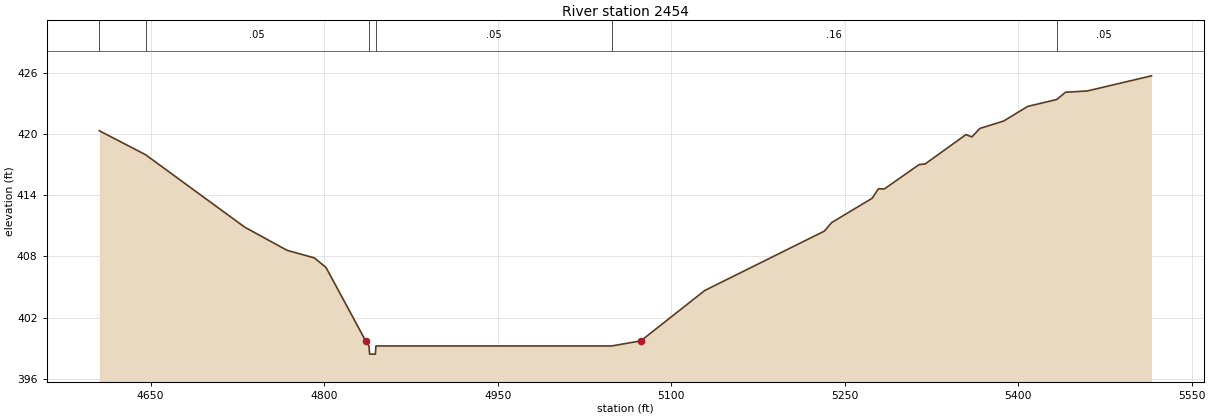
Type RM Length L Ch R = 1,2454,0,0,0
BEGIN DESCRIPTION:
UNT 119 in Running Cr Watershed 5.0
END DESCRIPTION:
XS GIS Cut Line= 3
      2865680.24      7005324.70      2865374.67      7005297.15
      2864791.40      7005449.71
#Sta/Elev= 30
  4605.6  420.31  4645.6  417.96  4731.3  410.86  4767.9  408.59  4791.6  407.84
  4801.6  406.91  4835.9  399.71  4838.8  399.21  4839.3  398.41  4844.3  398.41
  4844.8  399.21  5048.6  399.21  5073.8  399.71  5129.1  404.65  5232.5  410.47
  5238.7  411.30  5273.8  413.69  5279.2  414.62  5284.3  414.60  5314.4  416.99
  5319.6  417.05  5354.9  419.93  5360.0  419.70  5366.9  420.53  5387.5  421.26
  5408.2  422.69  5433.4  423.37  5440.9  424.08  5459.9  424.21  5515.3  425.69
#Mann=6,-1,0
  4605.6    0.16       0  4645.6    0.05       0  4838.8   0.033       0
  4844.8    0.05       0  5048.6    0.16       0  5433.4    0.05       0
Bank Sta=4835.9,5073.8
Exp/Cntr=0.3,0.1

Chan Stop Cuts=-1