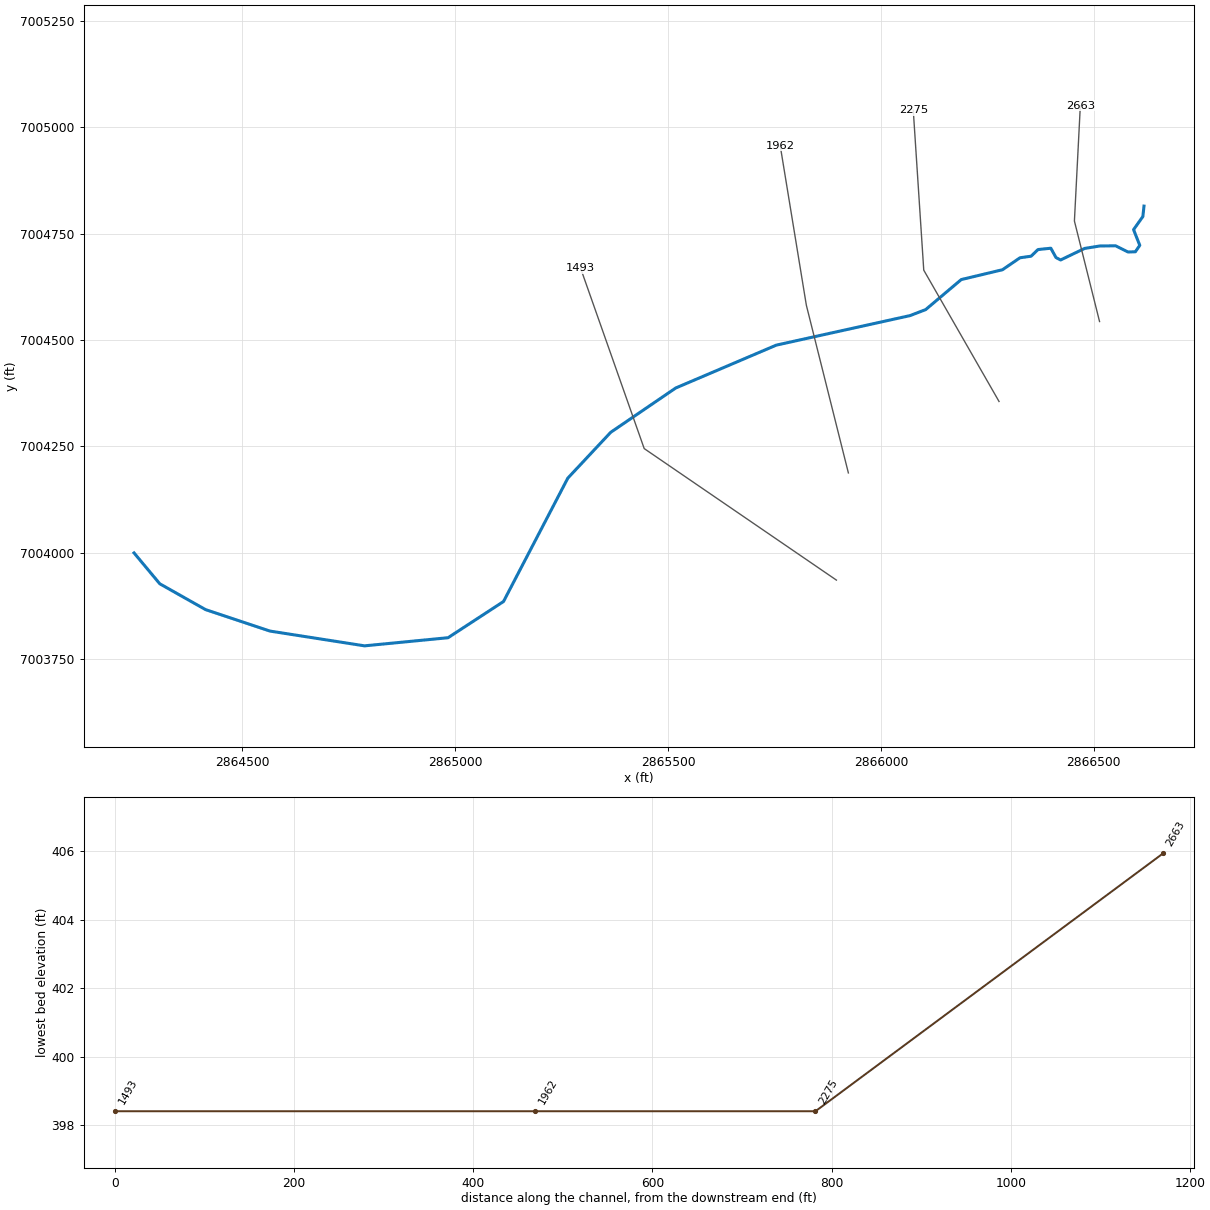
--- UNT 120 in Running Cr Watershed.prj (project) ---

Proj Title=UNT 120 in Running Cr Watershed Base Level Engineering
Current Plan=p01
Default Exp/Contr=0.3,0.1
English Units
Geom File=g01
Flow File=f01
Plan File=p01
BEGIN DESCRIPTION:
UNT 120 in Running Cr Watershed
END DESCRIPTION:

--- UNT 120 in Running Cr Watershed.p01 (plan) ---

Plan Title=Multiple Run
Short Identifier=Multiple
Geom File=g01
Flow File=f01
Subcritical Flow
K Sum by GR= 0
Std Step Tol= 0.01
Critical Tol= 0.01
Num of Std Step Trials= 20
Max Error Tol= 0.3
Flow Tol Ratio= 0.001
Split Flow NTrial= 30
Split Flow Tol= 0.02
Split Flow Ratio= 0.02
Log Output Level= 0
Friction Slope Method= 1
Unsteady Friction Slope Method= 2
Unsteady Bridges Friction Slope Method= 1
Parabolic Critical Depth
Global Vel Dist=  1 , 1 , 1
Global Log Level= 0
CheckData=True
Encroach Param= -1, 0, 0, 0
BEGIN DESCRIPTION:
Multiple Run
END DESCRIPTION:

--- UNT 120 in Running Cr Watershed.f01 (steady flow) ---

Flow Title=Multiple
Number of Profiles=7
Profile Names=10-year,25-year,50-year,1pct_min,100-year,1pct_plu,500-year
River Rch & RM= UNT 120 in Runni,Reach-1,2663
     134     162     183     103     205     410     259
Boundary for River Rch & Prof#=UNT 120 in Runni,Reach-1,1
Up Type=0
Dn Type=3
Dn Slope=0.005
Boundary for River Rch & Prof#=UNT 120 in Runni,Reach-1,2
Up Type=0
Dn Type=3
Dn Slope=0.005
Boundary for River Rch & Prof#=UNT 120 in Runni,Reach-1,3
Up Type=0
Dn Type=3
Dn Slope=0.005
Boundary for River Rch & Prof#=UNT 120 in Runni,Reach-1,4
Up Type=0
Dn Type=3
Dn Slope=0.005
Boundary for River Rch & Prof#=UNT 120 in Runni,Reach-1,5
Up Type=0
Dn Type=3
Dn Slope=0.005
Boundary for River Rch & Prof#=UNT 120 in Runni,Reach-1,6
Up Type=0
Dn Type=3
Dn Slope=0.005
Boundary for River Rch & Prof#=UNT 120 in Runni,Reach-1,7
Up Type=0
Dn Type=3
Dn Slope=0.005

--- UNT 120 in Running Cr Watershed.g01 (geometry) ---

Geom Title=Existing Conditions

River Reach=UNT 120 in Runni,Reach-1
Reach XY= 30
      2866617.98      7004814.62      2866615.37      7004790.14
      2866593.50      7004759.41      2866608.08      7004722.43
      2866597.67      7004707.33      2866580.48      7004706.81
      2866551.31      7004721.39      2866513.81      7004720.87
      2866478.40      7004715.14      2866422.15      7004688.06
      2866411.21      7004693.79      2866399.23      7004715.66
      2866369.02      7004712.54      2866352.87      7004696.91
      2866326.83      7004693.27      2866285.69      7004665.14
      2866188.81      7004641.99      2866105.26      7004571.46
      2866068.59      7004557.35      2865754.35      7004487.91
      2865518.24      7004387.21      2865365.46      7004283.05
      2865264.77      7004175.41      2865113.73      7003885.48
      2864983.52      7003800.41      2864787.34      7003781.31
      2864565.11      7003816.03      2864414.07      7003866.38
      2864306.43      7003927.14      2864245.97      7003999.67

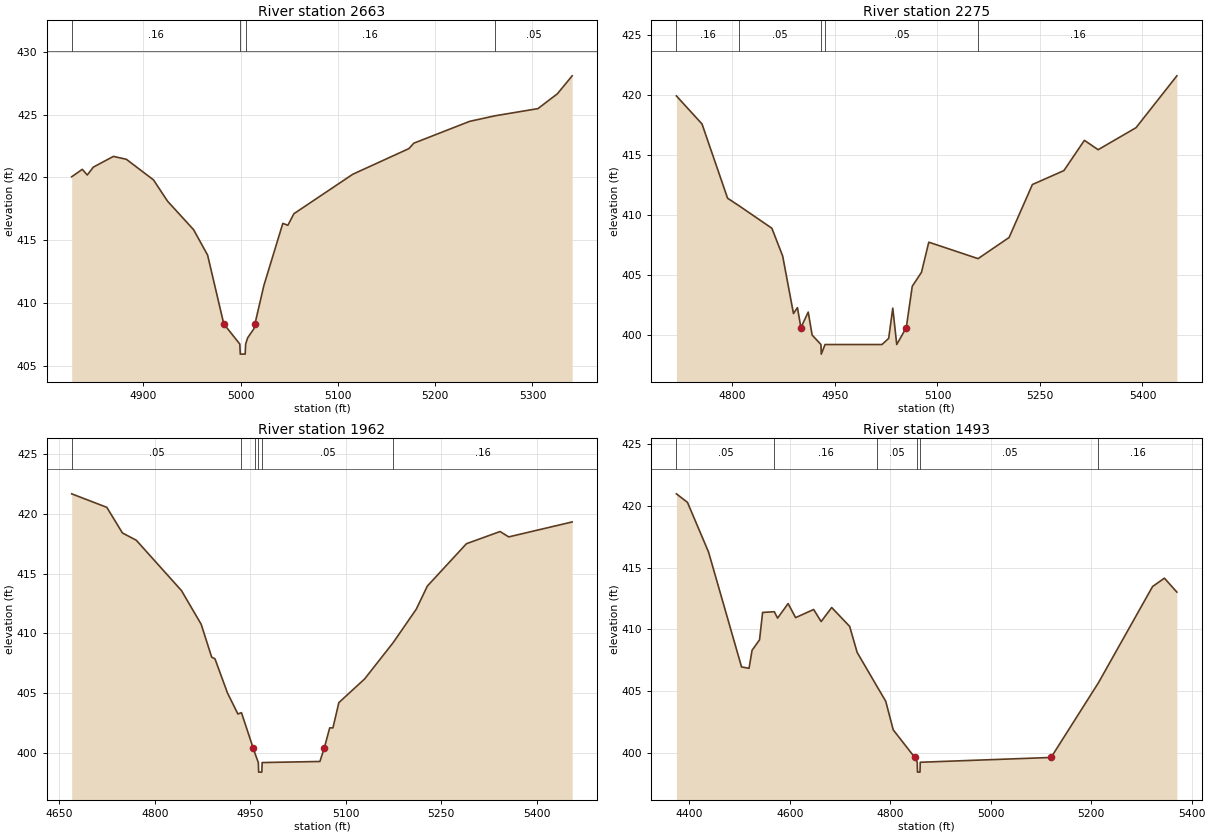
Type RM Length L Ch R = 1,2663,388,388,388
BEGIN DESCRIPTION:
UNT 120 in Running Cr Watershed 5.0
END DESCRIPTION:
XS GIS Cut Line= 3
      2866513.62      7004543.41      2866454.58      7004779.57
      2866468.46      7005050.19
#Sta/Elev= 30
  4826.4  420.05  4837.3  420.64  4842.4  420.19  4848.7  420.82  4869.3  421.67
  4882.6  421.44  4910.5  419.80  4924.9  418.11  4951.7  415.84  4966.1  413.82
  4982.7  408.35  4999.2  406.74  4999.7  405.94  5004.7  405.94  5005.2  406.74
  5007.3  407.24  5013.6  407.95  5014.8  408.36  5023.9  411.39  5043.4  416.34
  5048.6  416.19  5054.8  417.11  5115.3  420.25  5173.0  422.29  5178.0  422.72
  5235.5  424.46  5261.5  424.90  5305.6  425.47  5325.6  426.65  5340.8  428.08
#Mann=4,-1,0
  4826.4    0.16       0  4999.2    0.07       0  5005.2    0.16       0
  5261.5    0.05       0
Bank Sta=4982.7,5014.8
Exp/Cntr=0.3,0.1

Type RM Length L Ch R = 1,2275,313,313,313
BEGIN DESCRIPTION:
UNT 120 in Running Cr Watershed 4.0
END DESCRIPTION:
XS GIS Cut Line= 3
      2866277.55      7004355.54      2866100.75      7004664.10
      2866076.11      7005039.98
#Sta/Elev= 30
  4718.0  419.91  4755.5  417.57  4792.9  411.39  4809.2  410.78  4857.7  408.89
  4873.5  406.58  4889.3  401.79  4895.1  402.28  4900.2  400.62  4910.9  401.91
  4916.6  400.00  4929.5  399.21  4930.0  398.41  4935.5  399.21  5018.8  399.21
  5028.6  399.72  5034.6  402.24  5040.4  399.21  5054.4  400.62  5063.1  404.06
  5076.6  405.22  5087.3  407.73  5159.4  406.36  5204.8  408.12  5238.9  412.53
  5285.0  413.69  5315.0  416.21  5335.1  415.43  5390.5  417.26  5450.3  421.58
#Mann=5,-1,0
  4718.0    0.16       0  4809.2    0.05       0  4929.5    0.03       0
  4935.5    0.05       0  5159.4    0.16       0
Bank Sta=4900.2,5054.4
Exp/Cntr=0.3,0.1

Type RM Length L Ch R = 1,1962,469,469,469
BEGIN DESCRIPTION:
UNT 120 in Running Cr Watershed 3.0
END DESCRIPTION:
XS GIS Cut Line= 3
      2865923.69      7004187.65      2865825.00      7004581.65
      2865763.60      7004956.69
#Sta/Elev= 30
  4669.3  421.67  4724.5  420.54  4749.0  418.40  4770.8  417.79  4841.8  413.58
  4872.7  410.77  4889.2  408.02  4894.4  407.88  4914.0  405.03  4930.4  403.27
  4936.0  403.38  4954.3  400.44  4957.8  399.89  4962.5  399.21  4963.0  398.41
  4968.0  398.41  4968.5  399.21  5059.2  399.30  5066.2  400.44  5074.6  402.11
  5079.7  402.11  5089.0  404.22  5129.5  406.20  5174.4  409.24  5210.6  412.03
  5228.0  413.96  5289.4  417.50  5342.3  418.52  5355.8  418.07  5455.5  419.32
#Mann=6,-1,0
  4669.3    0.05       0  4936.0    0.16       0  4957.8    0.05       0
  4962.5   0.033       0  4968.5    0.05       0  5174.4    0.16       0
Bank Sta=4954.3,5066.2
Exp/Cntr=0.3,0.1

Type RM Length L Ch R = 1,1493,0,0,0
BEGIN DESCRIPTION:
Mapping XS c99c485b
END DESCRIPTION:
XS GIS Cut Line= 3
      2865895.58      7003935.80      2865444.17      7004244.85
      2865294.87      7004668.44
#Sta/Elev= 30
  4374.4  420.98  4396.4  420.29  4438.4  416.26  4504.1  406.94  4519.0  406.83
  4525.0  408.29  4539.9  409.14  4546.0  411.36  4569.3  411.42  4575.8  410.90
  4596.8  412.08  4611.7  410.94  4647.6  411.60  4662.5  410.62  4683.5  411.76
  4719.3  410.23  4734.2  408.12  4774.3  405.32  4791.1  404.16  4806.0  401.84
  4848.9  399.60  4853.8  399.21  4854.3  398.41  4859.3  398.41  4859.8  399.21
  5120.2  399.60  5214.5  405.66  5322.2  413.46  5345.8  414.14  5370.6  413.01
#Mann=6,-1,0
  4374.4    0.05       0  4569.3    0.16       0  4774.3    0.05       0
  4853.8   0.033       0  4859.8    0.05       0  5214.5    0.16       0
Bank Sta=4848.9,5120.2
Exp/Cntr=0.3,0.1

Chan Stop Cuts=-1