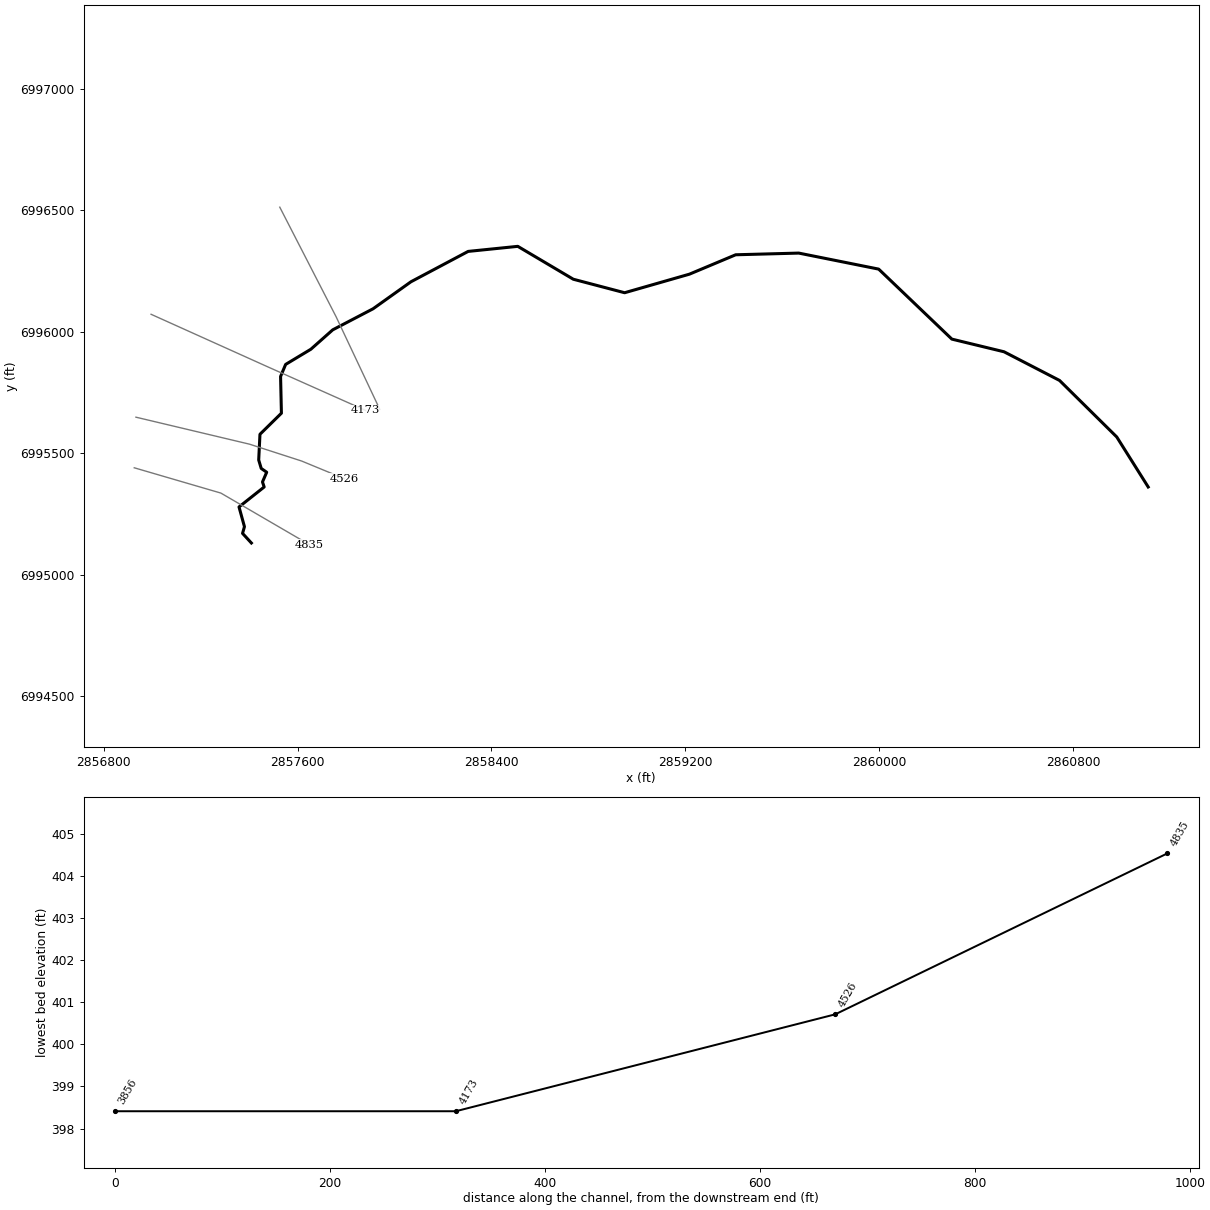
--- UNT 121 in Running Cr Watershed.prj (project) ---

Proj Title=UNT 121 in Running Cr Watershed Base Level Engineering
Current Plan=p01
Default Exp/Contr=0.3,0.1
English Units
Geom File=g01
Flow File=f01
Plan File=p01
BEGIN DESCRIPTION:
UNT 121 in Running Cr Watershed
END DESCRIPTION:

--- UNT 121 in Running Cr Watershed.p01 (plan) ---

Plan Title=Multiple Run
Short Identifier=Multiple
Geom File=g01
Flow File=f01
Subcritical Flow
K Sum by GR= 0
Std Step Tol= 0.01
Critical Tol= 0.01
Num of Std Step Trials= 20
Max Error Tol= 0.3
Flow Tol Ratio= 0.001
Split Flow NTrial= 30
Split Flow Tol= 0.02
Split Flow Ratio= 0.02
Log Output Level= 0
Friction Slope Method= 1
Unsteady Friction Slope Method= 2
Unsteady Bridges Friction Slope Method= 1
Parabolic Critical Depth
Global Vel Dist=  1 , 1 , 1
Global Log Level= 0
CheckData=True
Encroach Param= -1, 0, 0, 0
BEGIN DESCRIPTION:
Multiple Run
END DESCRIPTION:

--- UNT 121 in Running Cr Watershed.f01 (steady flow) ---

Flow Title=Multiple
Number of Profiles=7
Profile Names=10-year,25-year,50-year,1pct_min,100-year,1pct_plu,500-year
River Rch & RM= UNT 121 in Runni,Reach-1,4835
     257     322     372     213     426     850     559
Boundary for River Rch & Prof#=UNT 121 in Runni,Reach-1,1
Up Type=0
Dn Type=3
Dn Slope=0.005
Boundary for River Rch & Prof#=UNT 121 in Runni,Reach-1,2
Up Type=0
Dn Type=3
Dn Slope=0.005
Boundary for River Rch & Prof#=UNT 121 in Runni,Reach-1,3
Up Type=0
Dn Type=3
Dn Slope=0.005
Boundary for River Rch & Prof#=UNT 121 in Runni,Reach-1,4
Up Type=0
Dn Type=3
Dn Slope=0.005
Boundary for River Rch & Prof#=UNT 121 in Runni,Reach-1,5
Up Type=0
Dn Type=3
Dn Slope=0.005
Boundary for River Rch & Prof#=UNT 121 in Runni,Reach-1,6
Up Type=0
Dn Type=3
Dn Slope=0.005
Boundary for River Rch & Prof#=UNT 121 in Runni,Reach-1,7
Up Type=0
Dn Type=3
Dn Slope=0.005

--- UNT 121 in Running Cr Watershed.g01 (geometry) ---

Geom Title=Existing Conditions

River Reach=UNT 121 in Runni,Reach-1
Reach XY= 30
      2857408.97      6995129.84      2857372.51      6995169.42
      2857380.32      6995197.03      2857357.92      6995278.28
      2857461.74      6995360.39      2857454.80      6995381.23
      2857472.16      6995421.16      2857449.59      6995436.78
      2857439.17      6995471.50      2857444.38      6995577.41
      2857532.92      6995664.21      2857529.45      6995815.25
      2857550.29      6995865.02      2857654.45      6995927.52
      2857744.73      6996007.38      2857911.40      6996094.19
      2858067.65      6996205.30      2858303.76      6996330.30
      2858508.62      6996351.13      2858737.79      6996215.72
      2858949.59      6996160.16      2859216.95      6996236.55
      2859407.92      6996316.41      2859668.34      6996323.36
      2859998.20      6996257.38      2860300.29      6995969.19
      2860515.56      6995917.11      2860744.73      6995799.05
      2860980.84      6995566.41      2861110.70      6995360.44

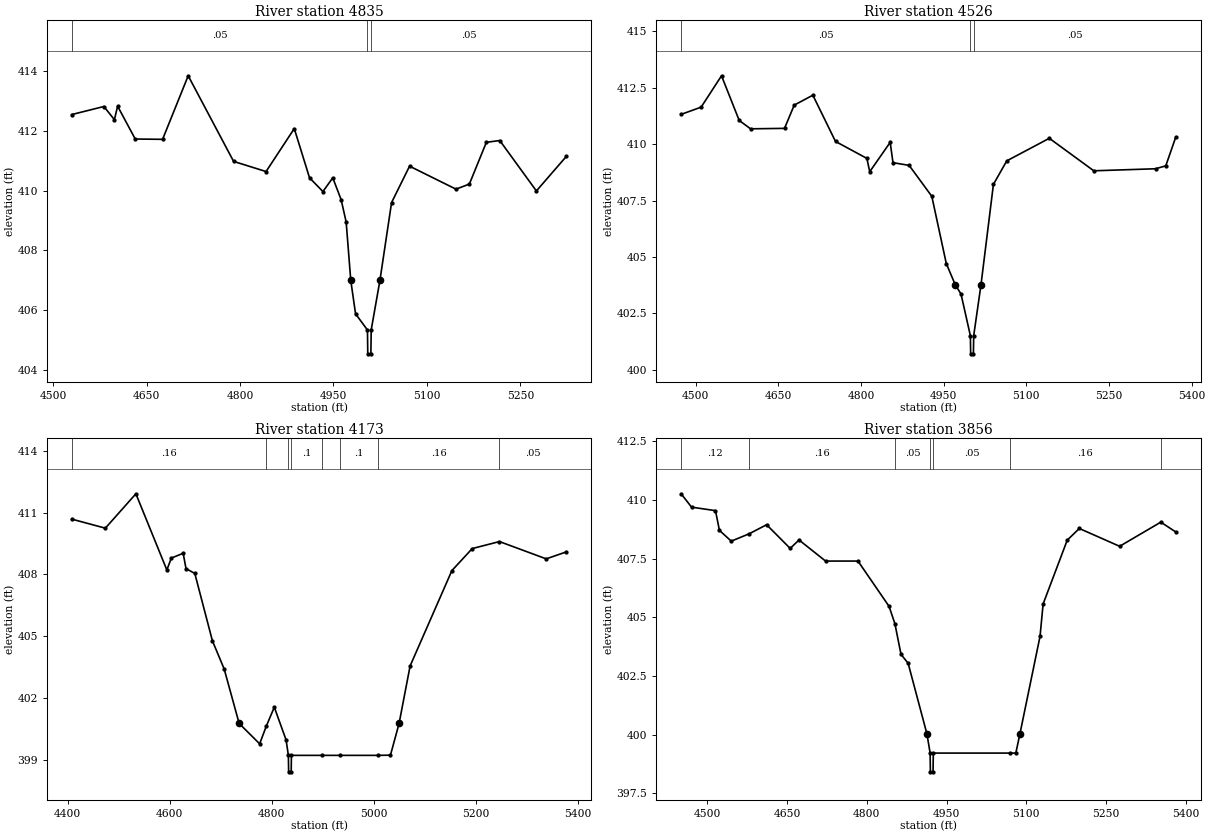
Type RM Length L Ch R = 1,4835,309,309,309
BEGIN DESCRIPTION:
UNT 121 in Running Cr Watershed 2.0
END DESCRIPTION:
XS GIS Cut Line= 3
      2856925.44      6995439.50      2857283.10      6995335.32
      2857647.71      6995123.50
#Sta/Elev= 30
  4529.8  412.55  4581.4  412.82  4598.3  412.38  4603.5  412.83  4631.8  411.73
  4675.7  411.72  4716.8  413.85  4789.7  410.98  4841.8  410.64  4887.1  412.08
  4911.6  410.43  4933.1  409.97  4948.9  410.43  4962.3  409.70  4970.4  408.95
  4977.8  406.99  4985.5  405.87  5004.6  405.33  5005.1  404.53  5010.1  404.53
  5010.6  405.33  5024.6  406.99  5043.3  409.60  5072.2  410.82  5146.7  410.05
  5168.2  410.22  5195.5  411.62  5217.0  411.68  5275.8  409.99  5324.0  411.15
#Mann=3,-1,0
  4529.8    0.05       0  5004.6    0.03       0  5010.6    0.05       0
Bank Sta=4977.8,5024.6
Exp/Cntr=0.3,0.1

Type RM Length L Ch R = 1,4526,353,353,353
BEGIN DESCRIPTION:
Mapping XS a417d22a
END DESCRIPTION:
XS GIS Cut Line= 4
      2856932.43      6995647.82      2857401.15      6995536.71
      2857616.43      6995467.27      2857791.74      6995395.08
#Sta/Elev= 30
  4473.7  411.32  4510.0  411.64  4547.0  413.03  4579.1  411.05  4599.7  410.68
  4661.3  410.70  4678.9  411.73  4712.7  412.17  4753.8  410.12  4810.7  409.37
  4815.9  408.78  4853.0  410.08  4858.1  409.18  4887.4  409.06  4928.5  407.69
  4954.8  404.71  4970.9  403.78  4981.5  403.36  4998.5  401.51  4999.0  400.71
  5004.0  400.71  5004.5  401.51  5017.8  403.78  5040.3  408.22  5064.5  409.26
  5141.7  410.26  5222.4  408.82  5334.4  408.91  5353.0  409.04  5371.2  410.32
#Mann=3,-1,0
  4473.7    0.05       0  4998.5    0.03       0  5004.5    0.05       0
Bank Sta=4970.9,5017.8
Exp/Cntr=0.3,0.1

Type RM Length L Ch R = 1,4173,317,317,317
BEGIN DESCRIPTION:
Mapping XS 65dfd7a5
END DESCRIPTION:
XS GIS Cut Line= 3
      2856994.91      6996071.43      2857474.07      6995856.16
      2857880.17      6995675.67
#Sta/Elev= 30
  4407.8  410.68  4473.7  410.24  4533.6  411.91  4594.3  408.21  4603.1  408.79
  4626.3  409.02  4631.8  408.28  4649.1  408.04  4683.6  404.77  4706.7  403.40
  4736.0  400.76  4776.2  399.77  4789.1  400.62  4804.9  401.55  4828.0  399.96
  4832.5  399.21  4833.0  398.41  4838.0  398.41  4838.5  399.21  4898.9  399.21
  4933.0  399.21  5008.4  399.21  5032.6  399.22  5049.5  400.76  5071.1  403.55
  5153.0  408.18  5192.9  409.25  5246.3  409.59  5337.9  408.75  5377.5  409.09
#Mann=8,-1,0
  4407.8    0.16       0  4789.1     0.1       0  4832.5    0.07       0
  4838.5     0.1       0  4898.9    0.05       0  4933.0     0.1       0
  5008.4    0.16       0  5246.3    0.05       0
Bank Sta=4736,5049.5
Exp/Cntr=0.3,0.1

Type RM Length L Ch R = 1,3856,0,0,0
BEGIN DESCRIPTION:
Mapping XS 0204a9db
END DESCRIPTION:
XS GIS Cut Line= 3
      2857526.16      6996512.39      2857758.79      6996061.02
      2857939.15      6995679.50
#Sta/Elev= 30
  4451.1  410.27  4470.7  409.70  4515.7  409.55  4523.1  408.71  4545.3  408.25
  4578.7  408.56  4611.8  408.95  4656.1  407.94  4672.7  408.30  4722.6  407.40
  4783.5  407.40  4841.9  405.47  4852.9  404.73  4864.4  403.42  4877.8  403.04
  4913.2  400.02  4919.1  399.21  4919.6  398.41  4924.6  398.41  4925.1  399.21
  5068.6  399.21  5080.2  399.21  5087.8  400.02  5125.7  404.19  5131.5  405.57
  5176.8  408.29  5199.5  408.79  5275.3  408.03  5352.7  409.06  5380.9  408.64
#Mann=7,-1,0
  4451.1    0.12       0  4578.7    0.16       0  4852.9    0.05       0
  4919.1   0.033       0  4925.1    0.05       0  5068.6    0.16       0
  5352.7    0.05       0
Bank Sta=4913.2,5087.8
Exp/Cntr=0.3,0.1

Chan Stop Cuts=-1