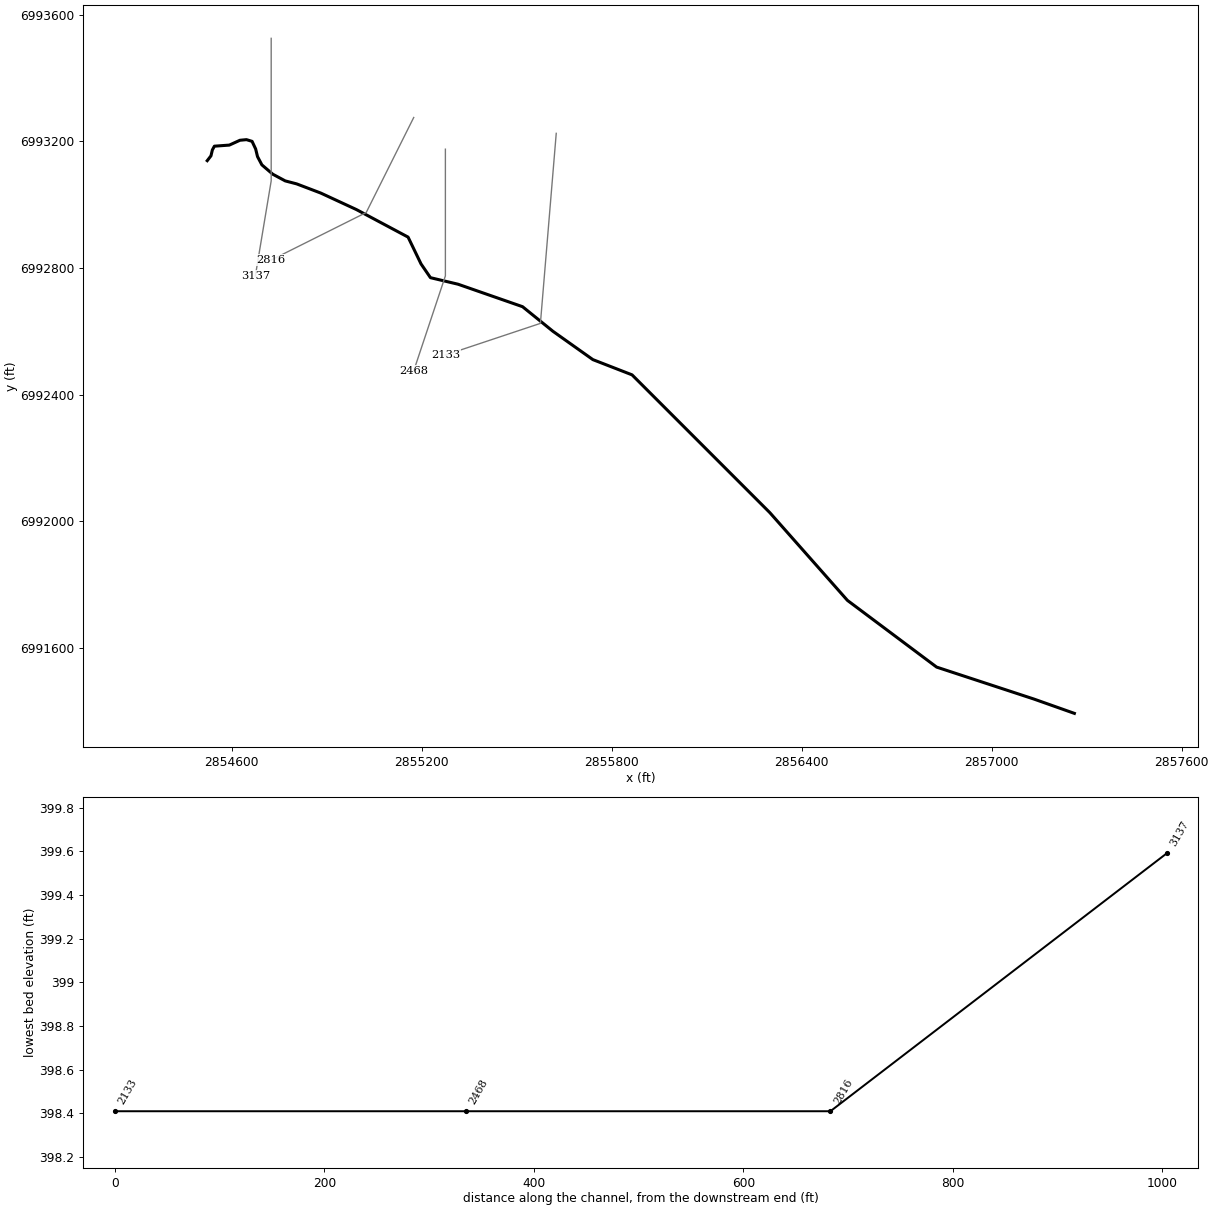
--- UNT 122 in Running Cr Watershed.prj (project) ---

Proj Title=UNT 122 in Running Cr Watershed Base Level Engineering
Current Plan=p01
Default Exp/Contr=0.3,0.1
English Units
Geom File=g01
Flow File=f01
Plan File=p01
BEGIN DESCRIPTION:
UNT 122 in Running Cr Watershed
END DESCRIPTION:

--- UNT 122 in Running Cr Watershed.p01 (plan) ---

Plan Title=Multiple Run
Short Identifier=Multiple
Geom File=g01
Flow File=f01
Subcritical Flow
K Sum by GR= 0
Std Step Tol= 0.01
Critical Tol= 0.01
Num of Std Step Trials= 20
Max Error Tol= 0.3
Flow Tol Ratio= 0.001
Split Flow NTrial= 30
Split Flow Tol= 0.02
Split Flow Ratio= 0.02
Log Output Level= 0
Friction Slope Method= 1
Unsteady Friction Slope Method= 2
Unsteady Bridges Friction Slope Method= 1
Parabolic Critical Depth
Global Vel Dist=  1 , 1 , 1
Global Log Level= 0
CheckData=True
Encroach Param= -1, 0, 0, 0
BEGIN DESCRIPTION:
Multiple Run
END DESCRIPTION:

--- UNT 122 in Running Cr Watershed.f01 (steady flow) ---

Flow Title=Multiple
Number of Profiles=7
Profile Names=10-year,25-year,50-year,1pct_min,100-year,1pct_plu,500-year
River Rch & RM= UNT 122 in Runni,Reach-1,3137
     480     636     760     453     903    1802    1274
Boundary for River Rch & Prof#=UNT 122 in Runni,Reach-1,1
Up Type=0
Dn Type=3
Dn Slope=0.005
Boundary for River Rch & Prof#=UNT 122 in Runni,Reach-1,2
Up Type=0
Dn Type=3
Dn Slope=0.005
Boundary for River Rch & Prof#=UNT 122 in Runni,Reach-1,3
Up Type=0
Dn Type=3
Dn Slope=0.005
Boundary for River Rch & Prof#=UNT 122 in Runni,Reach-1,4
Up Type=0
Dn Type=3
Dn Slope=0.005
Boundary for River Rch & Prof#=UNT 122 in Runni,Reach-1,5
Up Type=0
Dn Type=3
Dn Slope=0.005
Boundary for River Rch & Prof#=UNT 122 in Runni,Reach-1,6
Up Type=0
Dn Type=3
Dn Slope=0.005
Boundary for River Rch & Prof#=UNT 122 in Runni,Reach-1,7
Up Type=0
Dn Type=3
Dn Slope=0.005

--- UNT 122 in Running Cr Watershed.g01 (geometry) ---

Geom Title=Existing Conditions

River Reach=UNT 122 in Runni,Reach-1
Reach XY= 29
      2854523.06      6993138.73      2854534.86      6993153.97
      2854539.28      6993172.65      2854545.67      6993184.45
      2854592.86      6993187.89      2854626.29      6993203.13
      2854646.94      6993205.09      2854664.64      6993199.69
      2854675.95      6993175.60      2854681.84      6993151.51
      2854695.61      6993125.45      2854730.02      6993095.96
      2854769.35      6993074.82      2854805.24      6993065.48
      2854881.44      6993036.47      2854994.01      6992984.36
      2855157.22      6992897.35      2855198.06      6992812.78
      2855227.82      6992769.28      2855314.83      6992748.67
      2855518.60      6992677.69      2855614.77      6992599.85
      2855740.70      6992510.55      2855864.34      6992462.47
      2856299.36      6992027.44      2856544.35      6991750.40
      2856825.98      6991539.75      2857132.78      6991439.01
      2857260.92      6991393.65

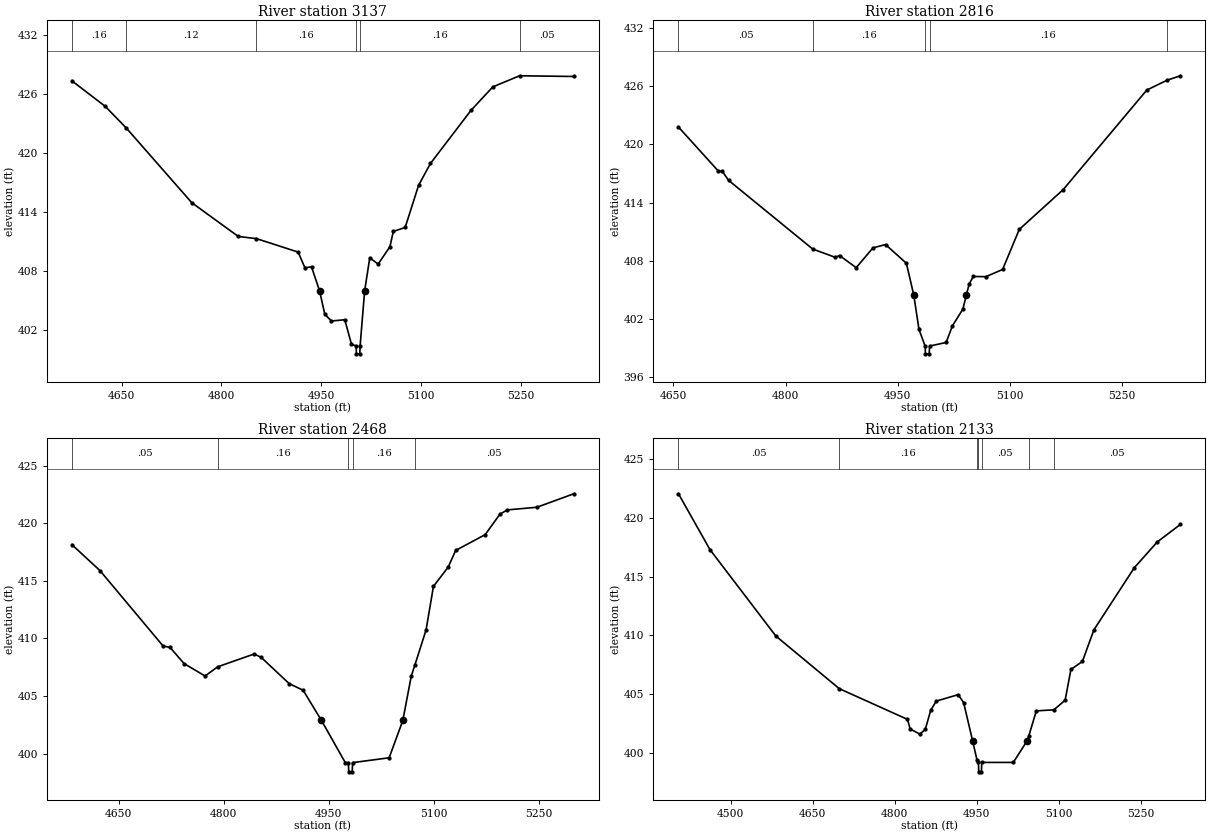
Type RM Length L Ch R = 1,3137,321,321,321
BEGIN DESCRIPTION:
UNT 122 in Running Cr Watershed 9.0
END DESCRIPTION:
XS GIS Cut Line= 3
      2854725.00      6993524.96      2854725.00      6993075.00
      2854675.00      6992775.00
#Sta/Elev= 30
  4575.3  427.36  4625.3  424.77  4656.9  422.57  4755.3  414.97  4825.3  411.53
  4852.6  411.31  4915.3  409.94  4925.3  408.35  4935.3  408.44  4947.4  405.99
  4955.3  403.60  4965.3  402.93  4985.3  403.06  4995.3  400.57  5002.3  400.39
  5002.8  399.59  5007.8  399.59  5008.3  400.39  5015.1  405.99  5022.8  409.36
  5035.4  408.72  5053.1  410.49  5058.2  412.04  5076.0  412.45  5096.2  416.74
  5114.0  418.96  5174.8  424.35  5207.7  426.75  5247.9  427.88  5329.4  427.81
#Mann=6,-1,0
  4575.3    0.16       0  4656.9    0.12       0  4852.6    0.16       0
  5002.3    0.07       0  5008.3    0.16       0  5247.9    0.05       0
Bank Sta=4947.4,5015.1
Exp/Cntr=0.3,0.1

Type RM Length L Ch R = 1,2816,348,348,348
BEGIN DESCRIPTION:
UNT 122 in Running Cr Watershed 8.0
END DESCRIPTION:
XS GIS Cut Line= 3
      2855175.02      6993275.04      2855025.00      6992975.00
      2854724.97      6992824.98
#Sta/Elev= 30
  4656.8  421.78  4710.0  417.25  4715.5  417.20  4723.9  416.28  4836.2  409.21
  4866.5  408.35  4872.1  408.54  4894.4  407.29  4916.8  409.33  4933.6  409.67
  4961.5  407.74  4971.4  404.45  4978.3  400.94  4986.5  399.21  4987.0  398.41
  4992.0  398.41  4992.5  399.21  5014.6  399.58  5023.0  401.29  5037.0  403.02
  5041.6  404.45  5045.4  405.61  5051.0  406.38  5067.7  406.36  5090.1  407.10
  5112.4  411.23  5171.1  415.33  5282.9  425.59  5310.0  426.60  5327.7  427.06
#Mann=5,-1,0
  4656.8    0.05       0  4836.2    0.16       0  4986.5    0.07       0
  4992.5    0.16       0  5310.0    0.05       0
Bank Sta=4971.4,5041.6
Exp/Cntr=0.3,0.1

Type RM Length L Ch R = 1,2468,335,335,335
BEGIN DESCRIPTION:
UNT 122 in Running Cr Watershed 7.0
END DESCRIPTION:
XS GIS Cut Line= 3
      2855275.00      6993174.99      2855275.00      6992775.00
      2855175.01      6992475.02
#Sta/Elev= 30
  4583.5  418.13  4623.5  415.88  4713.5  409.34  4723.5  409.21  4743.5  407.81
  4773.5  406.73  4791.5  407.53  4843.5  408.64  4853.5  408.35  4893.5  406.07
  4913.5  405.49  4939.6  402.87  4973.5  399.22  4978.0  399.21  4978.5  398.41
  4983.5  398.41  4984.0  399.21  5036.2  399.63  5055.7  402.87  5067.8  406.74
  5072.9  407.68  5088.9  410.73  5099.4  414.51  5120.5  416.19  5131.1  417.63
  5173.2  419.00  5194.3  420.78  5204.9  421.15  5247.0  421.38  5299.7  422.55
#Mann=5,-1,0
  4583.5    0.05       0  4791.5    0.16       0  4978.0    0.07       0
  4984.0    0.16       0  5072.9    0.05       0
Bank Sta=4939.6,5055.7
Exp/Cntr=0.3,0.1

Type RM Length L Ch R = 1,2133,0,0,0
BEGIN DESCRIPTION:
UNT 122 in Running Cr Watershed 6.0
END DESCRIPTION:
XS GIS Cut Line= 3
      2855625.00      6993225.04      2855575.00      6992625.00
      2855275.04      6992525.01
#Sta/Elev= 30
  4404.5  422.04  4462.2  417.29  4582.7  409.95  4698.7  405.48  4823.5  402.87
  4828.5  402.05  4846.1  401.62  4856.1  402.01  4866.1  403.65  4876.2  404.42
  4916.3  404.97  4926.3  404.29  4942.6  401.07  4950.8  399.40  4953.4  399.21
  4953.9  398.41  4958.9  398.41  4959.4  399.21  5017.2  399.21  5042.8  401.07
  5045.4  401.44  5059.3  403.59  5091.3  403.68  5112.0  404.49  5122.6  407.11
  5143.6  407.79  5164.7  410.48  5238.5  415.75  5280.7  417.95  5322.8  419.43
#Mann=7,-1,0
  4404.5    0.05       0  4698.7    0.16       0  4950.8    0.05       0
  4953.4   0.035       0  4959.4    0.05       0  5045.4    0.16       0
  5091.3    0.05       0
Bank Sta=4942.6,5042.8
Exp/Cntr=0.3,0.1

Chan Stop Cuts=-1