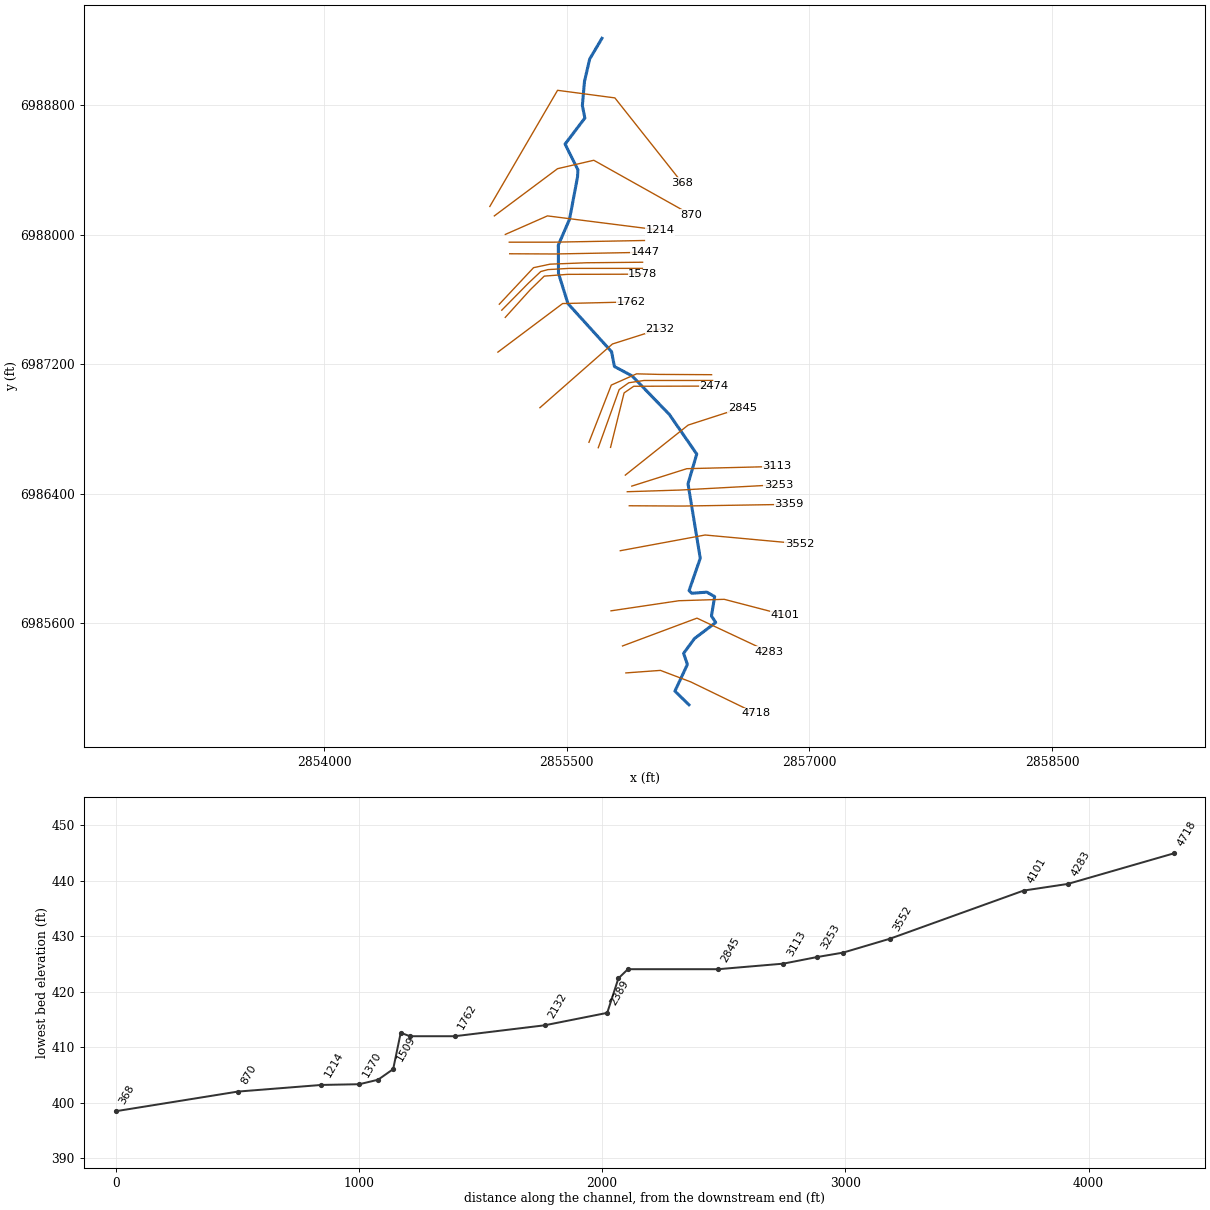
--- UNT 123 in Running Cr Watershed.prj (project) ---

Proj Title=UNT 123 in Running Cr Watershed Base Level Engineering
Current Plan=p01
Default Exp/Contr=0.3,0.1
English Units
Geom File=g01
Flow File=f01
Plan File=p01
BEGIN DESCRIPTION:
UNT 123 in Running Cr Watershed
END DESCRIPTION:

--- UNT 123 in Running Cr Watershed.p01 (plan) ---

Plan Title=Multiple Run
Short Identifier=Multiple
Geom File=g01
Flow File=f01
Subcritical Flow
K Sum by GR= 0
Std Step Tol= 0.01
Critical Tol= 0.01
Num of Std Step Trials= 20
Max Error Tol= 0.3
Flow Tol Ratio= 0.001
Split Flow NTrial= 30
Split Flow Tol= 0.02
Split Flow Ratio= 0.02
Log Output Level= 0
Friction Slope Method= 1
Unsteady Friction Slope Method= 2
Unsteady Bridges Friction Slope Method= 1
Parabolic Critical Depth
Global Vel Dist=  1 , 1 , 1
Global Log Level= 0
CheckData=True
Encroach Param= -1, 0, 0, 0
BEGIN DESCRIPTION:
Multiple Run
END DESCRIPTION:

--- UNT 123 in Running Cr Watershed.f01 (steady flow) ---

Flow Title=Multiple
Number of Profiles=7
Profile Names=10-year,25-year,50-year,1pct_min,100-year,1pct_plu,500-year
River Rch & RM= UNT 123 in Runni,Reach-1,4718
     288     370     434     254     508    1013     693
Boundary for River Rch & Prof#=UNT 123 in Runni,Reach-1,1
Up Type=0
Dn Type=3
Dn Slope=0.005
Boundary for River Rch & Prof#=UNT 123 in Runni,Reach-1,2
Up Type=0
Dn Type=3
Dn Slope=0.005
Boundary for River Rch & Prof#=UNT 123 in Runni,Reach-1,3
Up Type=0
Dn Type=3
Dn Slope=0.005
Boundary for River Rch & Prof#=UNT 123 in Runni,Reach-1,4
Up Type=0
Dn Type=3
Dn Slope=0.005
Boundary for River Rch & Prof#=UNT 123 in Runni,Reach-1,5
Up Type=0
Dn Type=3
Dn Slope=0.005
Boundary for River Rch & Prof#=UNT 123 in Runni,Reach-1,6
Up Type=0
Dn Type=3
Dn Slope=0.005
Boundary for River Rch & Prof#=UNT 123 in Runni,Reach-1,7
Up Type=0
Dn Type=3
Dn Slope=0.005

--- UNT 123 in Running Cr Watershed.g01 (geometry) ---

Geom Title=Existing Conditions

River Reach=UNT 123 in Runni,Reach-1
Reach XY= 30
      2856255.58      6985095.67      2856168.78      6985179.87
      2856246.03      6985344.80      2856222.59      6985413.37
      2856289.44      6985504.52      2856420.95      6985603.91
      2856394.59      6985644.59      2856414.44      6985764.07
      2856366.26      6985791.41      2856272.74      6985784.75
      2856256.38      6985801.12      2856325.41      6986000.87
      2856249.80      6986461.22      2856303.77      6986644.76
      2856134.25      6986889.90      2855904.09      6987127.77
      2855794.92      6987186.11      2855777.46      6987277.18
      2855507.65      6987574.87      2855449.28      6987762.08
      2855448.18      6987936.08      2855517.56      6988095.76
      2855567.11      6988357.86      2855569.32      6988401.91
      2855490.03      6988560.49      2855612.26      6988721.27
      2855596.85      6988798.35      2855610.06      6988948.12
      2855642.00      6989085.78      2855717.86      6989213.97

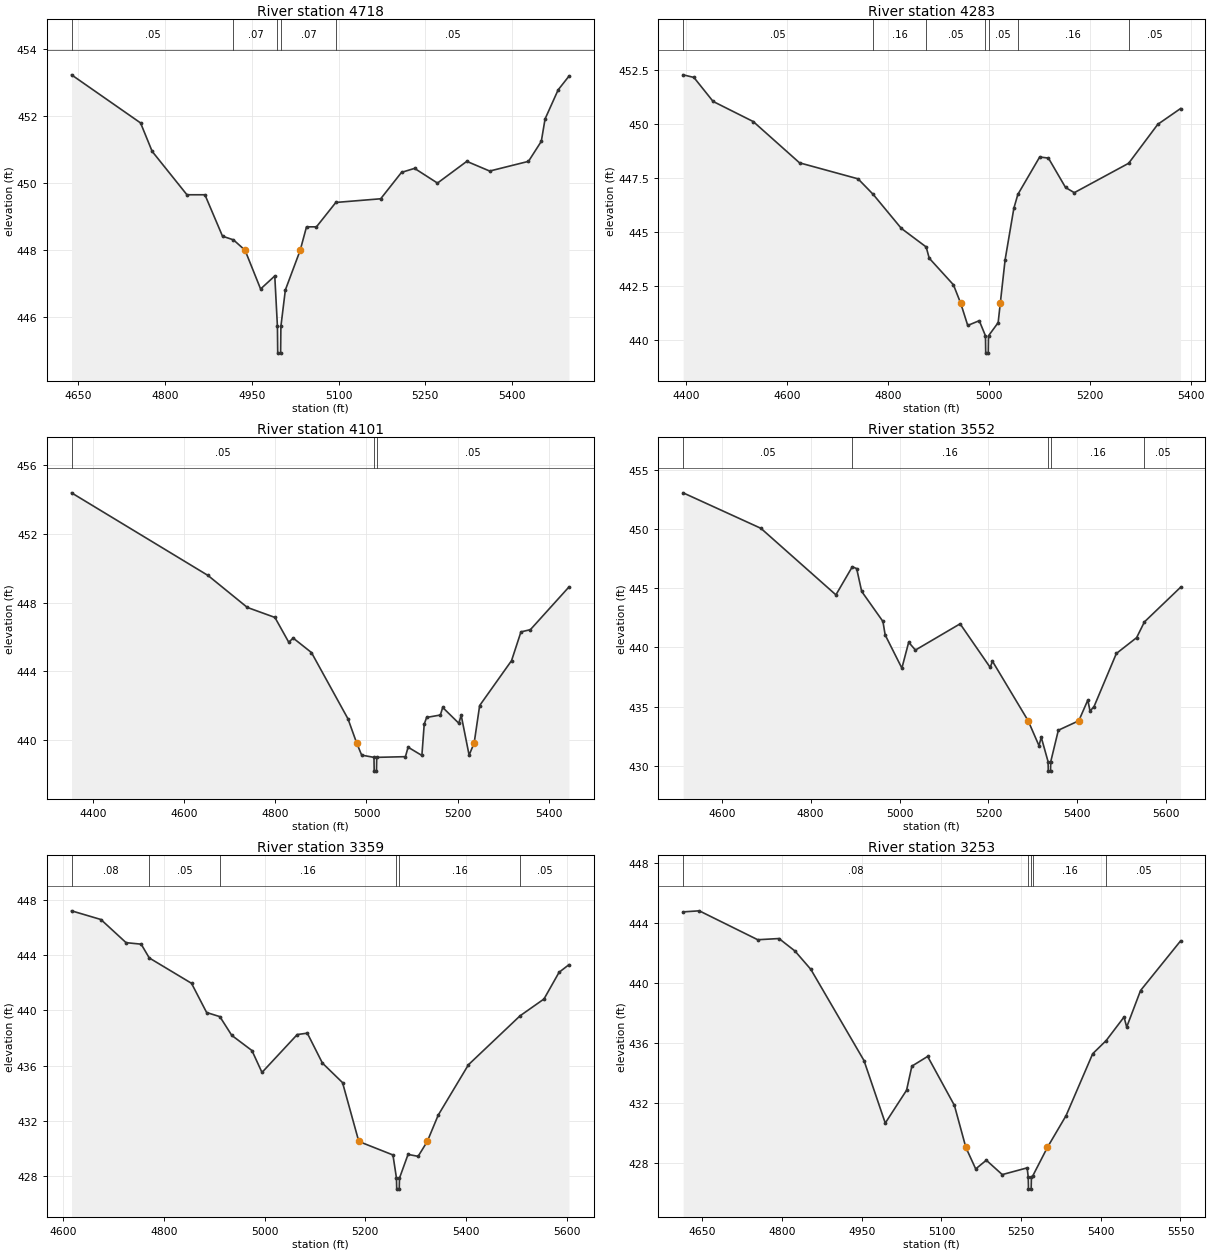
Type RM Length L Ch R = 1,4718,435,435,435
BEGIN DESCRIPTION:
UNT 123 in Running Cr Watershed 12.0
END DESCRIPTION:
XS GIS Cut Line= 4
      2855865.95      6985292.38      2856079.44      6985308.00
      2856266.94      6985236.82      2856667.97      6985042.38
#Sta/Elev= 30
  4638.1  453.24  4757.5  451.80  4777.5  450.95  4837.7  449.65  4868.8  449.65
  4899.2  448.41  4918.2  448.30  4938.2  447.99  4965.1  446.83  4989.6  447.22
  4994.2  445.71  4994.7  444.91  4999.7  444.91  5000.2  445.71  5007.9  446.80
  5033.6  447.99  5044.5  448.69  5061.7  448.69  5095.2  449.42  5172.8  449.53
  5208.8  450.32  5231.4  450.44  5271.0  450.00  5321.7  450.65  5361.3  450.36
  5428.4  450.65  5450.6  451.25  5457.1  451.92  5479.7  452.79  5498.4  453.20
#Mann=5,-1,0
  4638.1    0.05       0  4918.2    0.07       0  4994.2    0.07       0
  5000.2    0.07       0  5095.2    0.05       0
Bank Sta=4938.2,5033.6
Exp/Cntr=0.3,0.1

Type RM Length L Ch R = 1,4283,182,182,182
BEGIN DESCRIPTION:
UNT 123 in Running Cr Watershed 11.0
END DESCRIPTION:
XS GIS Cut Line= 3
      2855845.07      6985459.04      2856305.14      6985630.92
      2856751.76      6985421.29
#Sta/Elev= 30
  4394.7  452.28  4416.0  452.16  4454.0  451.05  4533.4  450.12  4625.1  448.21
  4740.9  447.47  4770.9  446.75  4826.5  445.18  4875.7  444.32  4881.8  443.80
  4929.7  442.57  4944.2  441.71  4958.0  440.69  4980.8  440.91  4993.1  440.21
  4993.6  439.41  4998.6  439.41  4999.1  440.21  5018.2  440.82  5022.4  441.71
  5032.0  443.73  5049.3  446.11  5057.2  446.75  5100.4  448.48  5117.7  448.43
  5151.6  447.07  5168.9  446.83  5276.5  448.19  5334.1  449.99  5379.2  450.72
#Mann=7,-1,0
  4394.7    0.05       0  4770.9    0.16       0  4875.7    0.05       0
  4993.1   0.035       0  4999.1    0.05       0  5057.2    0.16       0
  5276.5    0.05       0
Bank Sta=4944.2,5022.4
Exp/Cntr=0.3,0.1

Type RM Length L Ch R = 1,4101,549,549,549
BEGIN DESCRIPTION:
UNT 123 in Running Cr Watershed 10.0
END DESCRIPTION:
XS GIS Cut Line= 4
      2855773.89      6985676.06      2856194.03      6985738.56
      2856473.54      6985747.24      2856846.78      6985650.02
#Sta/Elev= 30
  4353.6  454.38  4652.6  449.58  4738.9  447.72  4799.3  447.14  4829.6  445.70
  4839.4  445.94  4879.4  445.10  4959.4  441.25  4978.4  439.85  4989.4  439.14
  5016.4  439.01  5016.9  438.21  5021.9  438.21  5022.4  439.01  5085.3  439.05
  5091.2  439.60  5121.4  439.12  5126.5  440.94  5131.8  441.33  5161.9  441.47
  5167.0  441.91  5202.4  440.99  5207.5  441.46  5224.9  439.14  5236.0  439.85
  5248.0  442.02  5317.9  444.63  5338.5  446.30  5359.2  446.43  5443.7  448.91
#Mann=3,-1,0
  4353.6    0.05       0  5016.4   0.033       0  5022.4    0.05       0
Bank Sta=4978.4,5236
Exp/Cntr=0.3,0.1

Type RM Length L Ch R = 1,3552,193,193,193
BEGIN DESCRIPTION:
UNT 123 in Running Cr Watershed 9.0
END DESCRIPTION:
XS GIS Cut Line= 3
      2855831.15      6986047.58      2856355.34      6986144.66
      2856938.78      6986090.99
#Sta/Elev= 30
  4513.2  453.08  4688.1  450.08  4856.9  444.45  4893.8  446.83  4903.6  446.67
  4914.9  444.74  4962.7  442.20  4967.7  441.06  5005.3  438.25  5020.6  440.44
  5035.8  439.78  5136.3  442.00  5204.0  438.31  5209.0  438.84  5289.4  433.80
  5313.8  431.69  5318.8  432.41  5334.2  430.34  5334.7  429.54  5339.7  429.54
  5340.2  430.34  5357.3  433.00  5403.3  433.80  5423.6  435.55  5428.6  434.62
  5437.6  435.00  5487.8  439.49  5533.4  440.83  5550.9  442.16  5632.2  445.09
#Mann=5,-1,0
  4513.2    0.05       0  4893.8    0.16       0  5334.2    0.07       0
  5340.2    0.16       0  5550.9    0.05       0
Bank Sta=5289.4,5403.3
Exp/Cntr=0.3,0.1

Type RM Length L Ch R = 1,3359,106,106,106
BEGIN DESCRIPTION:
Mapping XS f8f176c3
END DESCRIPTION:
XS GIS Cut Line= 3
      2855886.69      6986325.36      2856218.33      6986323.63
      2856874.60      6986334.04
#Sta/Elev= 30
  4616.6  447.23  4674.9  446.60  4724.9  444.92  4754.9  444.81  4771.0  443.81
  4854.9  441.97  4884.9  439.85  4911.2  439.55  4934.9  438.19  4974.9  437.09
  4994.9  435.50  5064.9  438.25  5084.9  438.35  5114.9  436.18  5154.9  434.76
  5187.2  430.49  5255.0  429.51  5262.0  427.83  5262.5  427.03  5267.5  427.03
  5268.0  427.83  5285.0  429.55  5305.0  429.41  5323.2  430.49  5344.9  432.40
  5405.0  436.06  5507.5  439.61  5555.0  440.83  5585.0  442.77  5604.6  443.32
#Mann=6,-1,0
  4616.6    0.08       0  4771.0    0.05       0  4911.2    0.16       0
  5262.0    0.07       0  5268.0    0.16       0  5507.5    0.05       0
Bank Sta=5187.2,5323.2
Exp/Cntr=0.3,0.1

Type RM Length L Ch R = 1,3253,140,140,140
BEGIN DESCRIPTION:
Mapping XS 466a399d
END DESCRIPTION:
XS GIS Cut Line= 3
      2855874.62      6986412.17      2856202.71      6986422.58
      2856810.16      6986455.56
#Sta/Elev= 30
  4613.6  444.75  4644.0  444.82  4754.1  442.89  4794.1  442.97  4824.1  442.14
  4854.1  440.91  4954.2  434.82  4994.2  430.65  5034.3  432.84  5044.3  434.45
  5074.0  435.10  5124.4  431.83  5146.0  429.02  5164.5  427.59  5184.5  428.17
  5214.5  427.21  5261.4  427.66  5263.4  427.04  5263.9  426.24  5268.9  426.24
  5269.4  427.04  5271.6  427.10  5299.4  429.02  5334.7  431.15  5384.8  435.28
  5410.2  436.16  5443.8  437.73  5448.8  437.06  5474.9  439.50  5550.2  442.81
#Mann=5,-1,0
  4613.6    0.08       0  5263.4    0.07       0  5269.4    0.08       0
  5271.6    0.16       0  5410.2    0.05       0
Bank Sta=5146,5299.4
Exp/Cntr=0.3,0.1

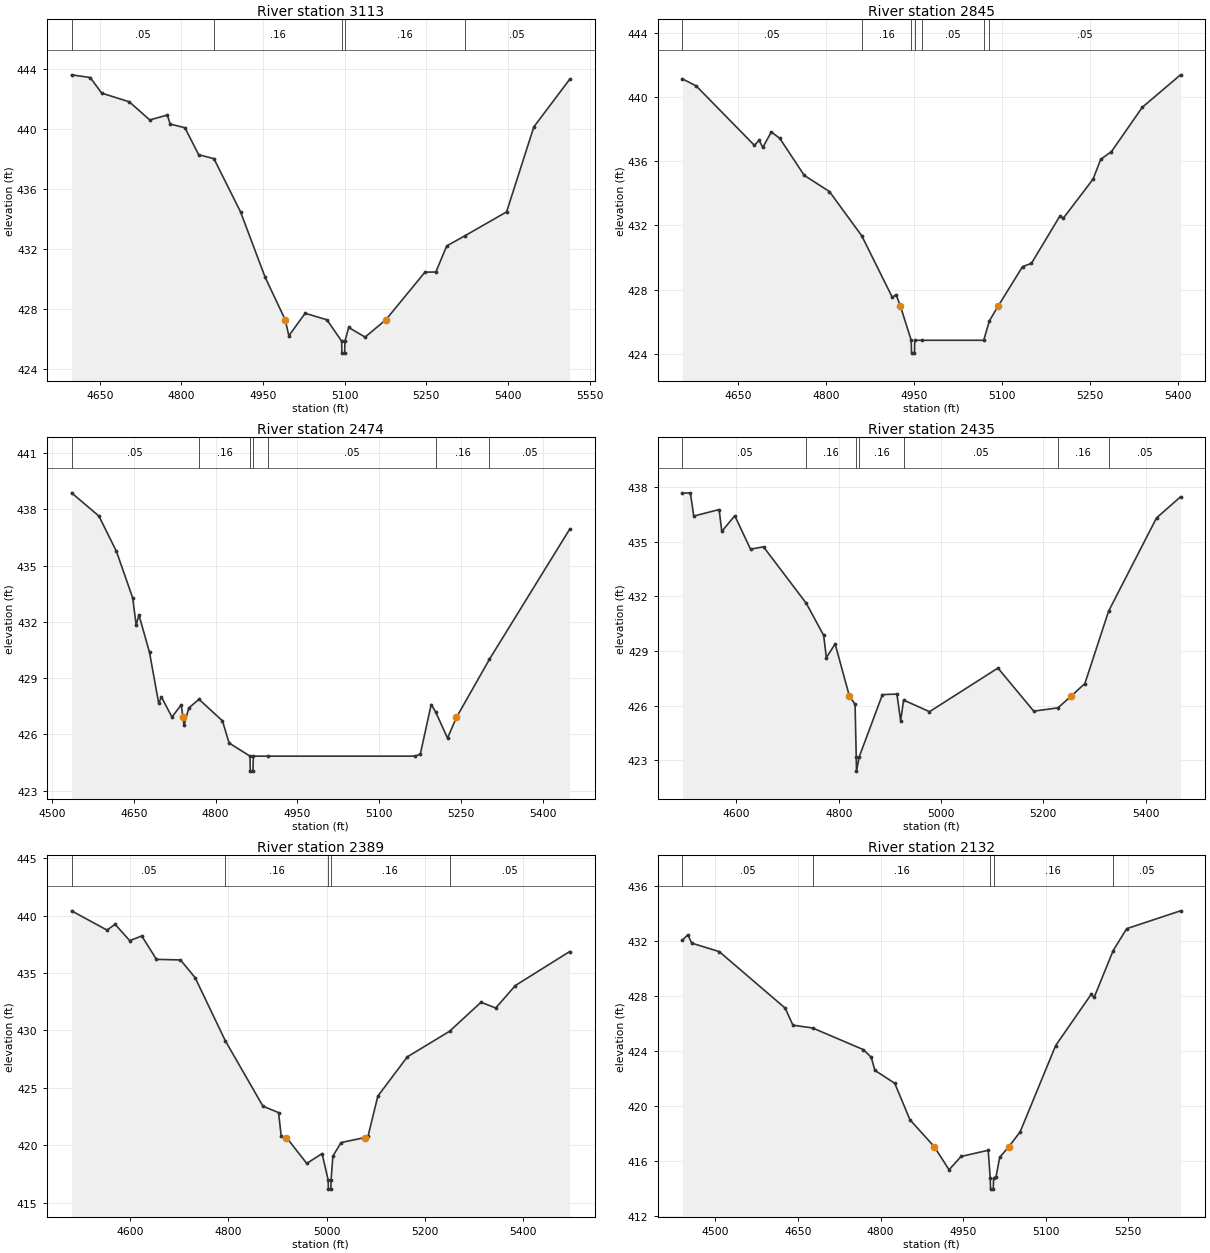
Type RM Length L Ch R = 1,3113,268,268,268
BEGIN DESCRIPTION:
UNT 123 in Running Cr Watershed 8.0
END DESCRIPTION:
XS GIS Cut Line= 3
      2855902.32      6986446.88      2856242.64      6986554.53
      2856800.83      6986568.40
#Sta/Elev= 30
  4598.1  443.60  4632.4  443.42  4653.4  442.38  4704.2  441.80  4741.8  440.59
  4774.1  440.92  4779.3  440.32  4806.4  440.07  4831.7  438.27  4859.7  438.01
  4908.6  434.46  4953.7  430.11  4990.6  427.27  4997.4  426.20  5027.4  427.70
  5067.4  427.26  5094.4  425.84  5094.9  425.04  5099.9  425.04  5100.4  425.84
  5107.4  426.75  5137.5  426.11  5175.8  427.27  5247.5  430.44  5267.5  430.45
  5287.5  432.19  5320.2  432.85  5397.5  434.46  5447.6  440.13  5513.4  443.30
#Mann=5,-1,0
  4598.1    0.05       0  4859.7    0.16       0  5094.4    0.07       0
  5100.4    0.16       0  5320.2    0.05       0
Bank Sta=4990.6,5175.8
Exp/Cntr=0.3,0.1

Type RM Length L Ch R = 1,2845,371,371,371
BEGIN DESCRIPTION:
UNT 123 in Running Cr Watershed 7.0
END DESCRIPTION:
XS GIS Cut Line= 3
      2855862.32      6986514.84      2856250.74      6986824.06
      2856587.10      6986932.56
#Sta/Elev= 30
  4555.1  441.12  4578.6  440.68  4677.9  436.98  4685.9  437.29  4692.3  436.85
  4706.7  437.81  4721.1  437.42  4763.0  435.11  4806.0  434.10  4861.2  431.34
  4913.3  427.51  4919.7  427.69  4927.2  426.95  4945.5  424.84  4946.0  424.04
  4951.0  424.04  4951.5  424.84  4963.1  424.84  5069.2  424.84  5078.9  426.05
  5093.5  426.95  5135.5  429.43  5150.6  429.63  5199.6  432.60  5204.8  432.43
  5255.7  434.87  5268.9  436.11  5287.2  436.59  5339.8  439.35  5405.0  441.37
#Mann=7,-1,0
  4555.1    0.05       0  4861.2    0.16       0  4945.5   0.033       0
  4951.5    0.16       0  4963.1    0.05       0  5069.2    0.16       0
  5078.9    0.05       0
Bank Sta=4927.2,5093.5
Exp/Cntr=0.3,0.1

Type RM Length L Ch R = 1,2474,39,39,39
BEGIN DESCRIPTION:
Mapping XS afb1eb46
END DESCRIPTION:
XS GIS Cut Line= 4
      2855771.14      6986686.25      2855854.69      6987022.63
      2855914.37      6987063.86      2856409.13      6987064.94
#Sta/Elev= 30
  4535.9  438.88  4586.1  437.64  4618.2  435.76  4648.0  433.28  4654.4  431.83
  4659.5  432.37  4678.9  430.37  4695.7  427.67  4700.9  427.99  4720.1  426.92
  4737.1  427.58  4740.3  426.90  4742.2  426.48  4751.0  427.41  4769.7  427.87
  4812.8  426.72  4824.9  425.54  4863.3  424.84  4863.8  424.04  4868.8  424.04
  4869.3  424.84  4897.1  424.84  5165.7  424.84  5175.7  424.94  5195.7  427.59
  5203.7  427.21  5225.7  425.80  5242.0  426.90  5302.7  430.01  5449.8  436.94
#Mann=7,-1,0
  4535.9    0.05       0  4769.7    0.16       0  4863.3   0.033       0
  4869.3    0.16       0  4897.1    0.05       0  5203.7    0.16       0
  5302.7    0.05       0
Bank Sta=4740.3,5242
Exp/Cntr=0.3,0.1

Type RM Length L Ch R = 1,2435,46,46,46
BEGIN DESCRIPTION:
Mapping XS f07397fd
END DESCRIPTION:
XS GIS Cut Line= 5
      2855695.20      6986684.12      2855824.31      6987043.24
      2855883.99      6987085.56      2855978.39      6987099.67
      2856401.85      6987099.67
#Sta/Elev= 30
  4494.5  437.68  4510.0  437.70  4516.7  436.42  4566.2  436.78  4571.5  435.58
  4596.9  436.44  4627.6  434.60  4653.0  434.73  4736.7  431.62  4770.6  429.86
  4775.9  428.63  4793.0  429.39  4821.1  426.50  4832.0  426.07  4834.3  423.19
  4834.8  422.39  4840.3  423.19  4885.5  426.60  4913.8  426.63  4921.1  425.16
  4926.9  426.30  4977.5  425.66  5111.3  428.06  5181.3  425.69  5228.5  425.87
  5253.7  426.50  5281.3  427.21  5327.6  431.19  5421.3  436.32  5468.2  437.48
#Mann=7,-1,0
  4494.5    0.05       0  4736.7    0.16       0  4834.3   0.033       0
  4840.3    0.16       0  4926.9    0.05       0  5228.5    0.16       0
  5327.6    0.05       0
Bank Sta=4821.1,5253.7
Exp/Cntr=0.3,0.1

Type RM Length L Ch R = 1,2389,257,257,257
BEGIN DESCRIPTION:
UNT 123 in Running Cr Watershed 6.0
END DESCRIPTION:
XS GIS Cut Line= 5
      2855637.69      6986717.75      2855775.62      6987071.17
      2855931.87      6987140.61      2856070.76      6987137.14
      2856395.46      6987135.40
#Sta/Elev= 30
  4480.6  440.43  4552.8  438.75  4569.2  439.26  4599.0  437.83  4623.5  438.24
  4653.4  436.20  4702.3  436.15  4732.2  434.60  4793.5  429.11  4870.2  423.40
  4902.0  422.84  4907.4  420.78  4918.1  420.67  4959.4  418.41  4990.6  419.27
  5002.9  416.97  5003.4  416.17  5008.4  416.17  5008.9  416.97  5012.5  419.04
  5029.2  420.23  5078.2  420.67  5084.1  420.78  5104.1  424.28  5164.1  427.70
  5250.1  429.93  5314.1  432.46  5344.1  431.96  5384.1  433.92  5494.6  436.88
#Mann=5,-1,0
  4480.6    0.05       0  4793.5    0.16       0  5002.9    0.07       0
  5008.9    0.16       0  5250.1    0.05       0
Bank Sta=4918.1,5078.2
Exp/Cntr=0.3,0.1

Type RM Length L Ch R = 1,2132,370,370,370
BEGIN DESCRIPTION:
UNT 123 in Running Cr Watershed 5.0
END DESCRIPTION:
XS GIS Cut Line= 3
      2855334.69      6986931.44      2855782.57      6987325.00
      2856076.87      6987418.40
#Sta/Elev= 30
  4440.1  432.06  4450.1  432.46  4456.8  431.85  4507.0  431.23  4626.9  427.11
  4640.9  425.87  4676.5  425.67  4768.9  424.09  4783.2  423.53  4789.8  422.58
  4825.9  421.64  4853.4  418.99  4897.7  417.02  4924.6  415.34  4946.4  416.31
  4995.7  416.76  4999.4  414.73  4999.9  413.93  5004.9  413.93  5005.4  414.73
  5009.9  414.83  5016.6  416.25  5033.2  417.02  5053.7  418.10  5118.3  424.39
  5182.8  428.12  5188.1  427.89  5222.8  431.31  5247.3  432.90  5345.1  434.20
#Mann=5,-1,0
  4440.1    0.05       0  4676.5    0.16       0  4999.4    0.07       0
  5005.4    0.16       0  5222.8    0.05       0
Bank Sta=4897.7,5033.2
Exp/Cntr=0.3,0.1

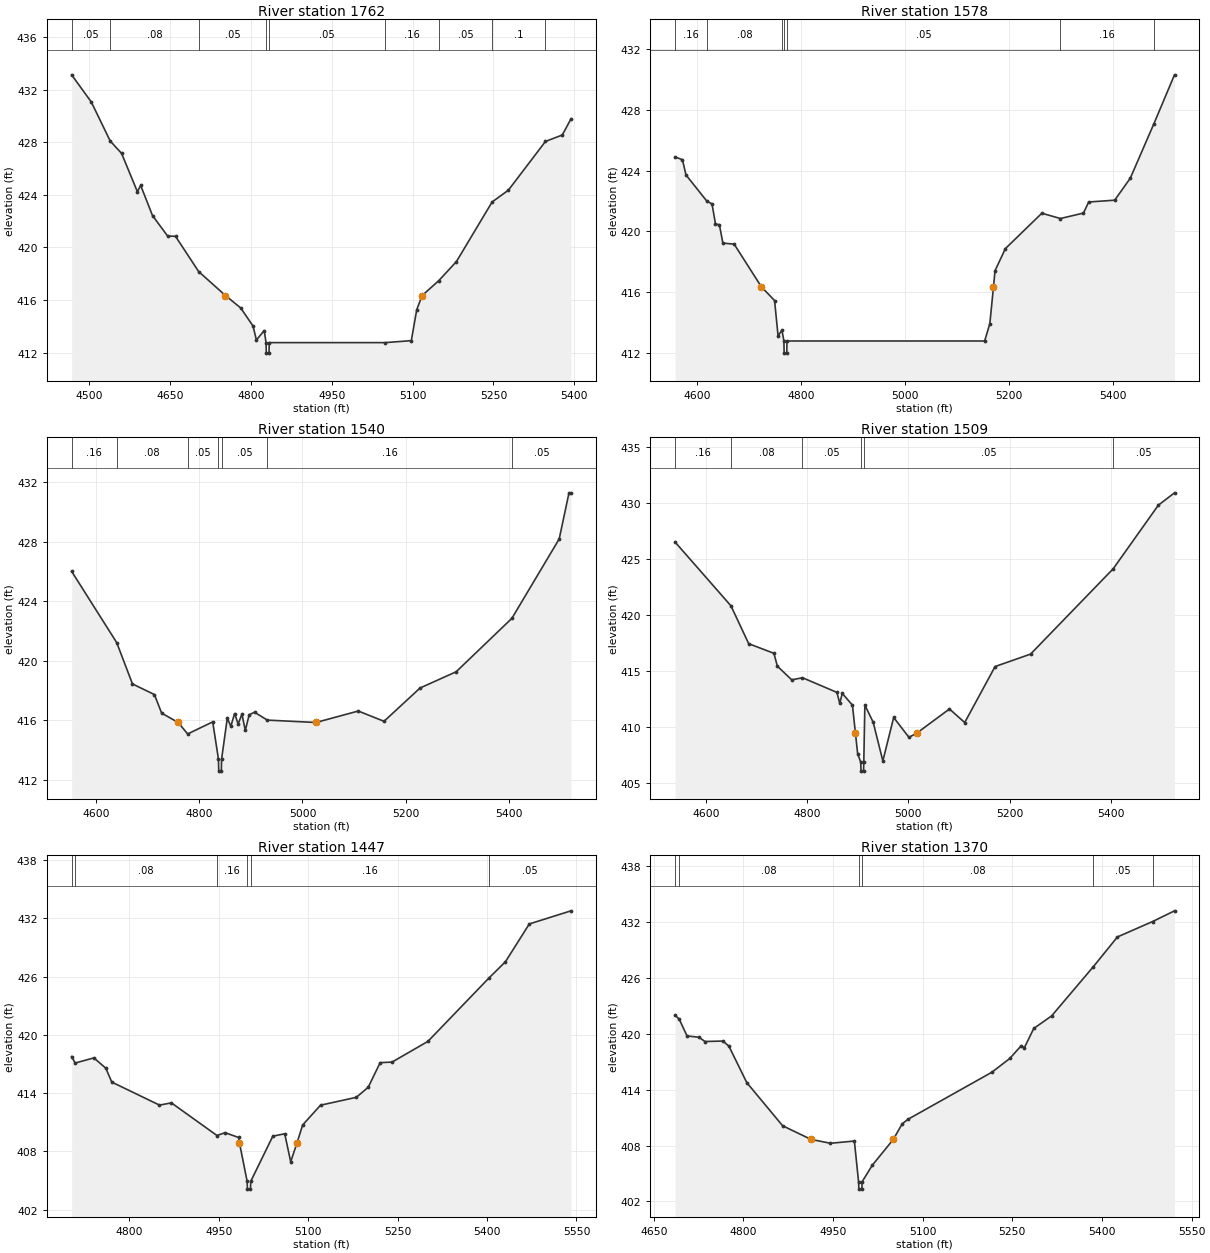
Type RM Length L Ch R = 1,1762,184,184,184
BEGIN DESCRIPTION:
UNT 123 in Running Cr Watershed 4.0
END DESCRIPTION:
XS GIS Cut Line= 3
      2855074.98      6987274.99      2855475.00      6987575.00
      2855901.16      6987585.03
#Sta/Elev= 30
  4467.6  433.14  4504.1  431.07  4539.2  428.10  4560.3  427.16  4589.5  424.25
  4595.7  424.72  4617.6  422.43  4645.7  420.87  4660.3  420.85  4703.2  418.17
  4753.0  416.34  4781.2  415.40  4804.1  414.02  4810.3  412.96  4824.9  413.68
  4828.2  412.76  4828.7  411.96  4833.7  411.96  4834.2  412.76  5049.5  412.76
  5097.7  412.91  5107.7  415.26  5117.7  416.34  5148.5  417.47  5181.4  418.93
  5247.5  423.46  5277.7  424.36  5346.5  428.07  5377.7  428.56  5393.9  429.79
#Mann=9,-1,0
  4467.6    0.05       0  4539.2    0.08       0  4703.2    0.05       0
  4828.2   0.033       0  4834.2    0.05       0  5049.5    0.16       0
  5148.5    0.05       0  5247.5     0.1       0  5346.5    0.16       0
Bank Sta=4753,5117.7
Exp/Cntr=0.3,0.1

Type RM Length L Ch R = 1,1578,38,38,38
BEGIN DESCRIPTION:
Mapping XS 3564aa6f
END DESCRIPTION:
XS GIS Cut Line= 5
      2855120.52      6987489.58      2855274.63      6987659.97
      2855361.43      6987744.60      2855505.75      6987755.45
      2855970.04      6987756.54
#Sta/Elev= 30
  4557.6  424.90  4571.7  424.72  4578.4  423.72  4619.0  421.97  4628.5  421.81
  4635.2  420.48  4642.7  420.43  4649.4  419.22  4671.1  419.15  4723.5  416.33
  4748.8  415.43  4755.5  413.10  4762.9  413.47  4766.7  412.76  4767.2  411.96
  4772.2  411.96  4772.7  412.76  5152.6  412.76  5162.6  413.90  5169.6  416.33
  5172.6  417.40  5192.6  418.86  5262.6  421.19  5298.3  420.84  5342.6  421.20
  5352.6  421.93  5402.6  422.05  5432.6  423.50  5477.7  427.07  5517.6  430.32
#Mann=7,-1,0
  4557.6    0.16       0  4619.0    0.08       0  4762.9    0.05       0
  4766.7   0.033       0  4772.7    0.05       0  5298.3    0.16       0
  5477.7    0.05       0
Bank Sta=4723.5,5169.6
Exp/Cntr=0.3,0.1

Type RM Length L Ch R = 1,1540,31,31,31
BEGIN DESCRIPTION:
Mapping XS 8b99cb3c
END DESCRIPTION:
XS GIS Cut Line= 6
      2855098.83      6987534.09      2855262.69      6987700.12
      2855339.73      6987772.81      2855384.22      6987784.75
      2855514.43      6987792.35      2855967.94      6987792.35
#Sta/Elev= 30
  4552.0  426.01  4639.5  421.22  4670.1  418.44  4712.6  417.73  4726.7  416.48
  4758.8  415.85  4777.2  415.08  4825.8  415.89  4837.0  413.38  4837.5  412.58
  4842.5  412.58  4843.0  413.38  4854.1  416.14  4861.0  415.60  4868.3  416.45
  4875.2  415.75  4882.5  416.41  4889.1  415.32  4896.6  416.37  4907.0  416.54
  4931.8  416.01  5026.2  415.85  5108.3  416.62  5158.3  415.93  5228.3  418.17
  5298.3  419.26  5406.4  422.85  5498.3  428.19  5517.3  431.29  5521.2  431.29
#Mann=7,-1,0
  4552.0    0.16       0  4639.5    0.08       0  4777.2    0.05       0
  4837.0    0.07       0  4843.0    0.05       0  4931.8    0.16       0
  5406.4    0.05       0
Bank Sta=4758.8,5026.2
Exp/Cntr=0.3,0.1

Type RM Length L Ch R = 1,1509,62,62,62
BEGIN DESCRIPTION:
Mapping XS a37ae835
END DESCRIPTION:
XS GIS Cut Line= 5
      2855083.63      6987570.97      2855295.24      6987796.69
      2855397.24      6987818.39      2855622.93      6987827.07
      2855969.08      6987830.32
#Sta/Elev= 30
  4539.6  426.48  4649.8  420.79  4684.8  417.41  4734.6  416.55  4741.4  415.40
  4769.8  414.18  4791.0  414.37  4859.0  413.06  4864.5  412.09  4869.6  412.97
  4889.6  411.92  4895.5  409.42  4899.9  407.58  4906.0  406.83  4906.5  406.03
  4911.5  406.03  4912.0  406.83  4914.1  411.93  4930.5  410.40  4949.6  406.94
  4971.0  410.82  5001.1  409.05  5016.5  409.42  5081.1  411.58  5111.2  410.37
  5171.2  415.37  5241.2  416.48  5404.3  424.10  5493.5  429.78  5525.3  430.88
#Mann=6,-1,0
  4539.6    0.16       0  4649.8    0.08       0  4791.0    0.05       0
  4906.0    0.07       0  4912.0    0.05       0  5404.3    0.05       0
Bank Sta=4895.5,5016.5
Exp/Cntr=0.3,0.1

Type RM Length L Ch R = 1,1447,77,77,77
BEGIN DESCRIPTION:
Mapping XS f9704c21
END DESCRIPTION:
XS GIS Cut Line= 3
      2855147.71      6987882.62      2855425.02      6987881.32
      2855984.91      6987891.74
#Sta/Elev= 30
  4703.5  417.77  4709.4  417.10  4740.8  417.63  4760.8  416.57  4770.8  415.14
  4850.8  412.77  4870.8  413.00  4947.2  409.64  4960.8  409.93  4983.3  409.44
  4984.9  408.88  4997.8  404.92  4998.3  404.12  5003.3  404.12  5003.8  404.92
  5040.8  409.57  5060.8  409.82  5070.8  406.94  5081.4  408.88  5090.8  410.72
  5120.8  412.76  5180.8  413.57  5200.8  414.61  5220.8  417.14  5240.8  417.20
  5300.9  419.33  5402.5  425.81  5430.9  427.53  5470.9  431.42  5540.8  432.77
#Mann=6,-1,0
  4703.5    0.05       0  4709.4    0.08       0  4947.2    0.16       0
  4997.8    0.07       0  5003.8    0.16       0  5402.5    0.05       0
Bank Sta=4984.9,5081.4
Exp/Cntr=0.3,0.1

Type RM Length L Ch R = 1,1370,156,156,156
BEGIN DESCRIPTION:
Mapping XS c4954d49
END DESCRIPTION:
XS GIS Cut Line= 3
      2855145.08      6987954.24      2855415.90      6987954.24
      2855980.49      6987964.65
#Sta/Elev= 30
  4685.8  422.00  4692.6  421.59  4705.7  419.78  4725.7  419.64  4735.7  419.18
  4765.7  419.23  4775.7  418.69  4805.7  414.76  4865.7  410.12  4913.1  408.66
  4945.7  408.24  4985.7  408.48  4992.7  404.11  4993.2  403.31  4998.2  403.31
  4998.7  404.11  5015.7  405.88  5050.9  408.66  5065.7  410.33  5075.7  410.83
  5215.8  415.88  5245.8  417.36  5265.0  418.74  5270.0  418.50  5285.8  420.58
  5315.8  421.94  5385.7  427.24  5425.8  430.42  5484.7  432.08  5521.3  433.23
#Mann=6,-1,0
  4685.8    0.05       0  4692.6    0.08       0  4992.7    0.07       0
  4998.7    0.08       0  5385.7    0.05       0  5484.7    0.08       0
Bank Sta=4913.1,5050.9
Exp/Cntr=0.3,0.1

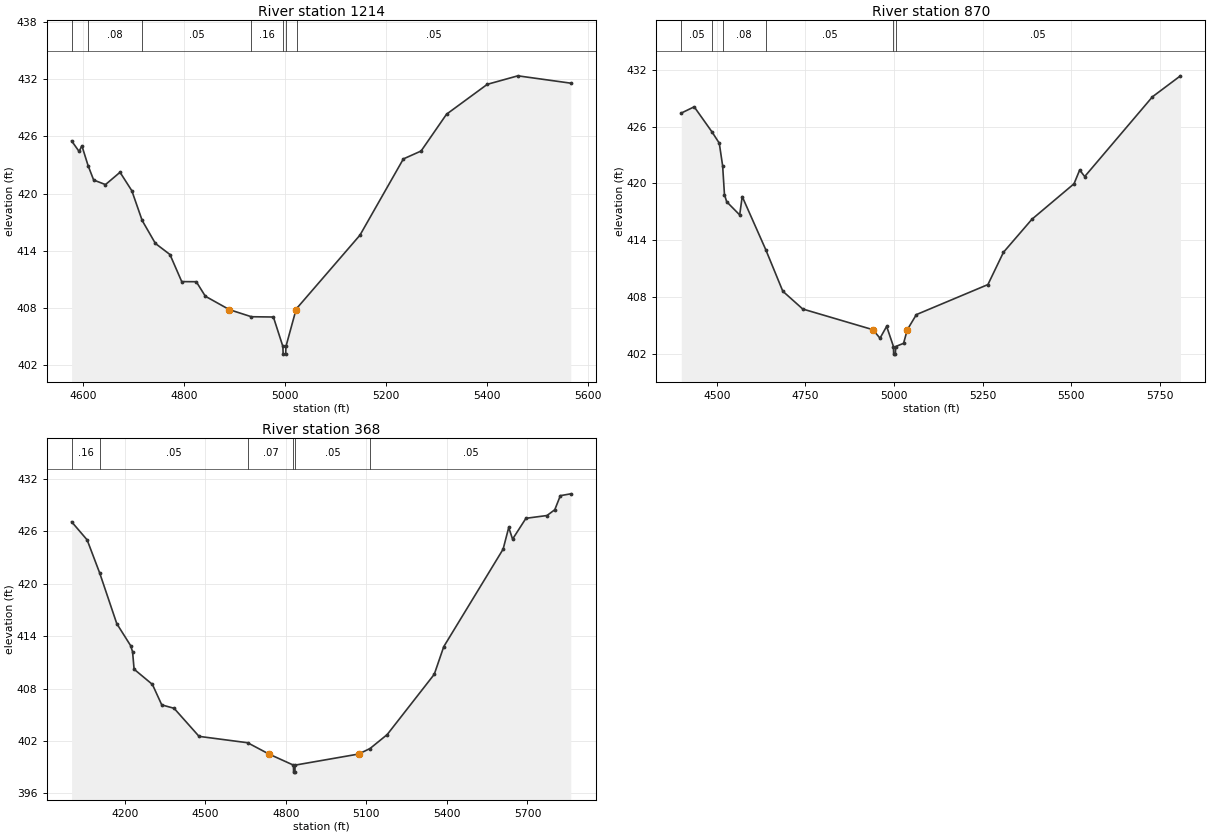
Type RM Length L Ch R = 1,1214,344,344,344
BEGIN DESCRIPTION:
UNT 123 in Running Cr Watershed 3.0
END DESCRIPTION:
XS GIS Cut Line= 3
      2855120.71      6988002.15      2855381.08      6988116.71
      2856078.86      6988028.46
#Sta/Elev= 30
  4577.3  425.53  4592.1  424.42  4597.6  425.02  4609.8  422.95  4620.9  421.43
  4644.3  420.95  4673.1  422.24  4696.4  420.31  4716.9  417.19  4743.1  414.78
  4771.9  413.62  4795.2  410.78  4824.0  410.77  4841.9  409.25  4889.6  407.84
  4933.0  407.10  4976.6  407.07  4995.4  403.98  4995.9  403.18  5000.9  403.18
  5001.4  403.98  5021.4  407.84  5023.2  408.00  5147.9  415.65  5233.8  423.64
  5268.9  424.47  5319.3  428.33  5399.9  431.46  5460.4  432.35  5565.1  431.58
#Mann=7,-1,0
  4577.3    0.05       0  4609.8    0.08       0  4716.9    0.05       0
  4933.0    0.16       0  4995.4    0.07       0  5001.4    0.16       0
  5023.2    0.05       0
Bank Sta=4889.6,5021.4
Exp/Cntr=0.3,0.1

Type RM Length L Ch R = 1,870,502,502,502
BEGIN DESCRIPTION:
UNT 123 in Running Cr Watershed 2.0
END DESCRIPTION:
XS GIS Cut Line= 4
      2855052.93      6988116.69      2855443.58      6988408.38
      2855667.54      6988460.46      2856270.82      6988122.41
#Sta/Elev= 30
  4399.5  427.42  4435.9  428.08  4486.5  425.41  4506.7  424.24  4516.2  421.84
  4521.3  418.82  4527.6  418.06  4564.3  416.67  4571.4  418.61  4637.7  413.02
  4686.0  408.62  4742.3  406.74  4940.2  404.56  4960.4  403.66  4979.1  404.91
  4998.4  402.78  4998.9  401.98  5003.9  401.98  5004.4  402.78  5026.9  403.12
  5037.5  404.56  5063.0  406.15  5265.0  409.32  5308.9  412.73  5389.4  416.22
  5508.1  419.96  5524.0  421.41  5538.2  420.72  5729.5  429.14  5808.5  431.35
#Mann=6,-1,0
  4399.5    0.05       0  4486.5    0.16       0  4516.2    0.08       0
  4637.7    0.05       0  4998.4    0.03       0  5004.4    0.05       0
Bank Sta=4940.2,5037.5
Exp/Cntr=0.3,0.1

Type RM Length L Ch R = 1,368,0,0,0
BEGIN DESCRIPTION:
UNT 123 in Running Cr Watershed 1.0
END DESCRIPTION:
XS GIS Cut Line= 4
      2855025.02      6988175.04      2855443.58      6988892.75
      2855797.74      6988845.88      2856214.37      6988319.88
#Sta/Elev= 30
  4002.1  427.07  4059.9  425.00  4106.8  421.20  4170.3  415.42  4222.0  412.90
  4229.1  412.20  4234.8  410.21  4303.0  408.47  4337.8  406.13  4383.7  405.74
  4476.7  402.53  4657.7  401.80  4736.9  400.51  4828.3  399.24  4828.8  398.44
  4833.8  398.44  4834.3  399.24  5071.2  400.51  5113.5  401.14  5177.3  402.73
  5352.8  409.63  5388.1  412.79  5609.2  423.94  5630.1  426.42  5644.5  425.09
  5694.2  427.47  5772.7  427.79  5801.6  428.45  5822.4  430.06  5861.2  430.27
#Mann=6,-1,0
  4002.1    0.16       0  4106.8    0.05       0  4657.7    0.07       0
  4828.3    0.07       0  4834.3    0.05       0  5113.5    0.05       0
Bank Sta=4736.9,5071.2
Exp/Cntr=0.3,0.1

Chan Stop Cuts=-1