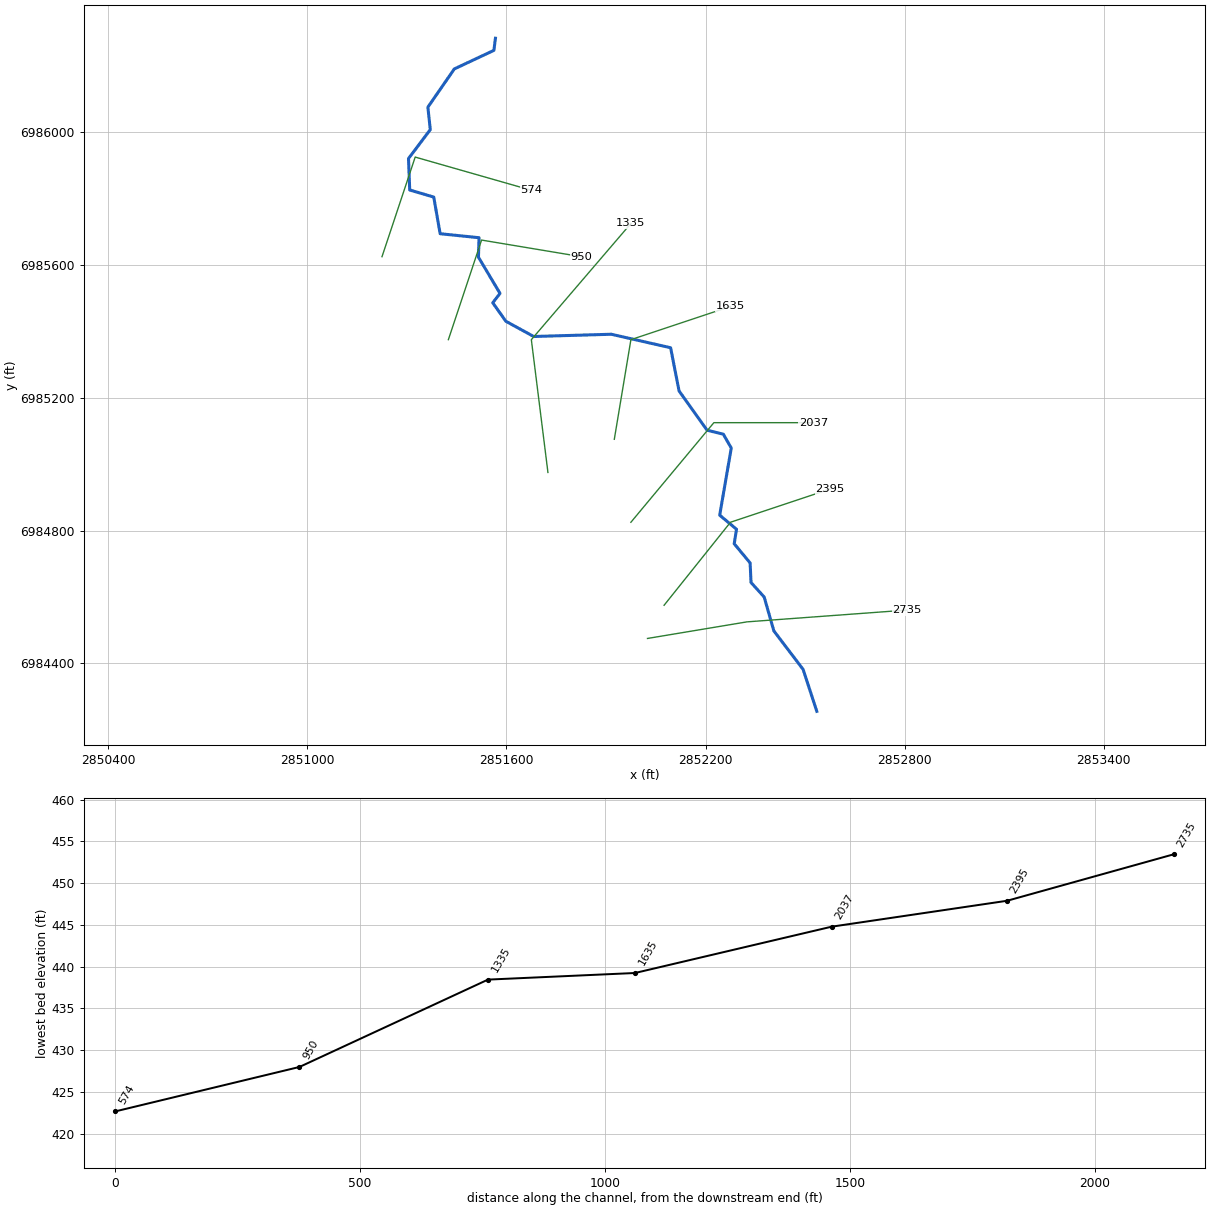
--- UNT 124 in Running Cr Watershed.prj (project) ---

Proj Title=UNT 124 in Running Cr Watershed Base Level Engineering
Current Plan=p01
Default Exp/Contr=0.3,0.1
English Units
Geom File=g01
Flow File=f01
Plan File=p01
BEGIN DESCRIPTION:
UNT 124 in Running Cr Watershed
END DESCRIPTION:

--- UNT 124 in Running Cr Watershed.p01 (plan) ---

Plan Title=Multiple Run
Short Identifier=Multiple
Geom File=g01
Flow File=f01
Subcritical Flow
K Sum by GR= 0
Std Step Tol= 0.01
Critical Tol= 0.01
Num of Std Step Trials= 20
Max Error Tol= 0.3
Flow Tol Ratio= 0.001
Split Flow NTrial= 30
Split Flow Tol= 0.02
Split Flow Ratio= 0.02
Log Output Level= 0
Friction Slope Method= 1
Unsteady Friction Slope Method= 2
Unsteady Bridges Friction Slope Method= 1
Parabolic Critical Depth
Global Vel Dist=  1 , 1 , 1
Global Log Level= 0
CheckData=True
Encroach Param= -1, 0, 0, 0
BEGIN DESCRIPTION:
Multiple Run
END DESCRIPTION:

--- UNT 124 in Running Cr Watershed.f01 (steady flow) ---

Flow Title=Multiple
Number of Profiles=7
Profile Names=10-year,25-year,50-year,1pct_min,100-year,1pct_plu,500-year
River Rch & RM= UNT 124 in Runni,Reach-1,2735
     205     259     300     174     347     691     462
Boundary for River Rch & Prof#=UNT 124 in Runni,Reach-1,1
Up Type=0
Dn Type=3
Dn Slope=0.005
Boundary for River Rch & Prof#=UNT 124 in Runni,Reach-1,2
Up Type=0
Dn Type=3
Dn Slope=0.005
Boundary for River Rch & Prof#=UNT 124 in Runni,Reach-1,3
Up Type=0
Dn Type=3
Dn Slope=0.005
Boundary for River Rch & Prof#=UNT 124 in Runni,Reach-1,4
Up Type=0
Dn Type=3
Dn Slope=0.005
Boundary for River Rch & Prof#=UNT 124 in Runni,Reach-1,5
Up Type=0
Dn Type=3
Dn Slope=0.005
Boundary for River Rch & Prof#=UNT 124 in Runni,Reach-1,6
Up Type=0
Dn Type=3
Dn Slope=0.005
Boundary for River Rch & Prof#=UNT 124 in Runni,Reach-1,7
Up Type=0
Dn Type=3
Dn Slope=0.005

--- UNT 124 in Running Cr Watershed.g01 (geometry) ---

Geom Title=Existing Conditions

River Reach=UNT 124 in Runni,Reach-1
Reach XY= 30
      2852535.12      6984255.54      2852493.93      6984381.76
      2852405.73      6984497.73      2852376.57      6984599.81
      2852336.98      6984643.56      2852334.21      6984702.59
      2852286.29      6984760.23      2852293.23      6984803.98
      2852242.54      6984846.34      2852277.44      6985048.60
      2852253.48      6985090.27      2852204.52      6985102.24
      2852120.14      6985220.47      2852094.62      6985350.68
      2851915.98      6985391.31      2851682.12      6985384.54
      2851598.27      6985430.37      2851558.69      6985486.10
      2851580.56      6985514.40      2851515.63      6985623.43
      2851517.37      6985682.11      2851400.18      6985694.09
      2851380.91      6985804.50      2851308.51      6985825.86
      2851304.87      6985920.65      2851370.49      6986007.63
      2851363.20      6986075.34      2851442.89      6986190.44
      2851562.16      6986246.43      2851566.83      6986282.94

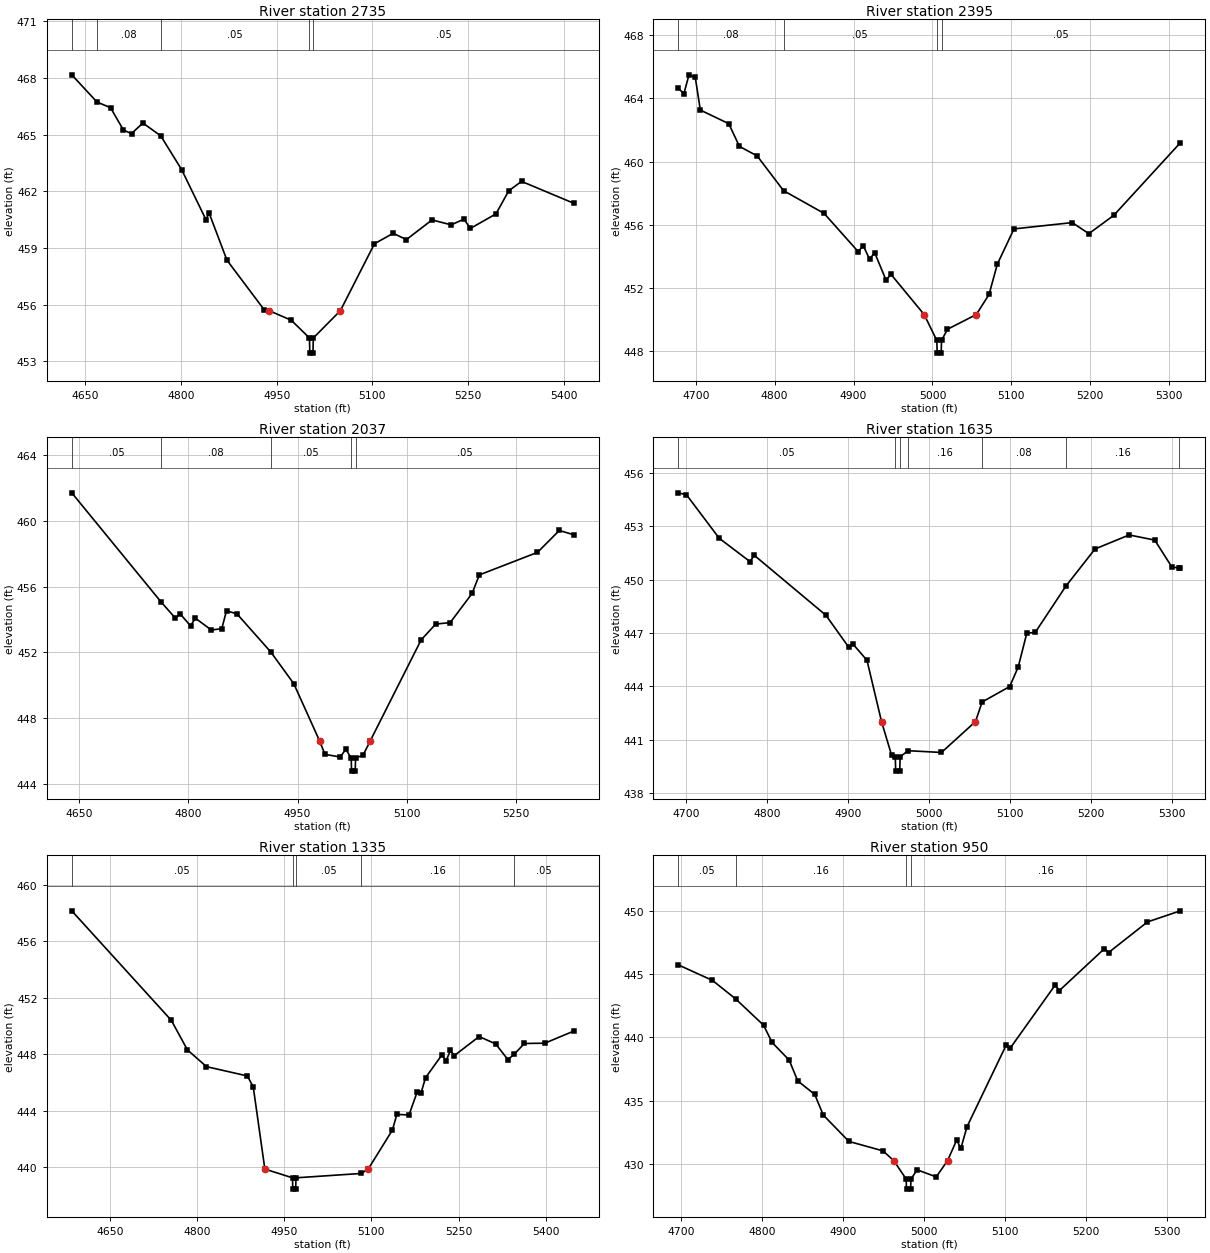
Type RM Length L Ch R = 1,2735,340,340,340
BEGIN DESCRIPTION:
UNT 124 in Running Cr Watershed 7.0
END DESCRIPTION:
XS GIS Cut Line= 3
      2852025.04      6984475.01      2852325.00      6984525.00
      2852806.80      6984560.51
#Sta/Elev= 30
  4628.7  468.17  4668.2  466.73  4689.5  466.43  4709.8  465.24  4722.4  465.06
  4740.2  465.62  4768.2  464.94  4801.0  463.15  4839.0  460.51  4844.1  460.85
  4872.0  458.36  4930.3  455.74  4938.0  455.69  4972.9  455.18  5001.4  454.24
  5001.9  453.44  5006.9  453.44  5007.4  454.24  5049.9  455.69  5103.3  459.23
  5132.6  459.78  5153.4  459.45  5193.5  460.49  5223.6  460.23  5243.6  460.53
  5253.7  460.04  5293.8  460.81  5313.8  462.03  5333.9  462.53  5415.9  461.37
#Mann=5,-1,0
  4628.7    0.05       0  4668.2    0.08       0  4768.2    0.05       0
  5001.4    0.03       0  5007.4    0.05       0
Bank Sta=4938,5049.9
Exp/Cntr=0.3,0.1

Type RM Length L Ch R = 1,2395,358,358,358
BEGIN DESCRIPTION:
UNT 124 in Running Cr Watershed 6.0
END DESCRIPTION:
XS GIS Cut Line= 3
      2852075.02      6984575.03      2852275.00      6984825.00
      2852574.96      6984924.99
#Sta/Elev= 30
  4677.8  464.64  4685.0  464.30  4691.4  465.49  4699.4  465.33  4705.8  463.26
  4741.8  462.40  4755.4  460.96  4777.8  460.36  4811.3  458.16  4862.7  456.72
  4905.9  454.30  4912.3  454.68  4920.3  453.82  4926.7  454.24  4941.1  452.51
  4947.5  452.86  4989.5  450.32  5005.5  448.68  5006.0  447.88  5011.0  447.88
  5011.5  448.68  5019.0  449.39  5055.5  450.32  5071.7  451.59  5082.2  453.51
  5103.3  455.74  5177.1  456.14  5198.2  455.44  5229.8  456.60  5314.1  461.19
#Mann=4,-1,0
  4677.8    0.08       0  4811.3    0.05       0  5005.5    0.03       0
  5011.5    0.05       0
Bank Sta=4989.5,5055.5
Exp/Cntr=0.3,0.1

Type RM Length L Ch R = 1,2037,402,402,402
BEGIN DESCRIPTION:
UNT 124 in Running Cr Watershed 5.0
END DESCRIPTION:
XS GIS Cut Line= 3
      2851974.99      6984824.99      2852225.00      6985125.00
      2852524.98      6985125.00
#Sta/Elev= 30
  4639.5  461.70  4762.6  455.05  4782.0  454.08  4788.6  454.34  4802.9  453.61
  4809.4  454.08  4831.5  453.36  4845.8  453.44  4852.3  454.53  4866.7  454.34
  4913.1  452.03  4944.8  450.10  4980.3  446.62  4987.7  445.80  5008.5  445.64
  5016.4  446.10  5023.8  445.58  5024.3  444.78  5029.3  444.78  5029.8  445.58
  5040.0  445.74  5050.0  446.62  5120.0  452.76  5140.0  453.72  5160.0  453.81
  5190.0  455.58  5200.0  456.71  5280.0  458.08  5310.0  459.41  5330.0  459.15
#Mann=5,-1,0
  4639.5    0.05       0  4762.6    0.08       0  4913.1    0.05       0
  5023.8    0.03       0  5029.8    0.05       0
Bank Sta=4980.3,5050
Exp/Cntr=0.3,0.1

Type RM Length L Ch R = 1,1635,300,300,300
BEGIN DESCRIPTION:
UNT 124 in Running Cr Watershed 4.0
END DESCRIPTION:
XS GIS Cut Line= 3
      2851924.99      6985074.96      2851975.00      6985375.00
      2852275.00      6985475.00
#Sta/Elev= 30
  4690.4  454.89  4700.6  454.78  4741.1  452.33  4779.1  451.02  4784.2  451.38
  4872.9  448.00  4900.8  446.22  4905.9  446.40  4923.6  445.47  4941.6  442.02
  4954.0  440.13  4958.6  440.03  4959.1  439.23  4964.1  439.23  4964.6  440.03
  4974.2  440.38  5015.7  440.28  5057.7  442.02  5065.9  443.12  5100.0  443.99
  5110.5  445.09  5121.1  446.99  5131.6  447.04  5169.4  449.64  5205.4  451.73
  5247.6  452.52  5279.2  452.23  5300.3  450.72  5309.2  450.66  5310.8  450.66
#Mann=7,-1,0
  4690.4    0.05       0  4958.6    0.07       0  4964.6    0.05       0
  4974.2    0.16       0  5065.9    0.08       0  5169.4    0.16       0
  5309.2    0.05       0
Bank Sta=4941.6,5057.7
Exp/Cntr=0.3,0.1

Type RM Length L Ch R = 1,1335,385,385,385
BEGIN DESCRIPTION:
UNT 124 in Running Cr Watershed 3.0
END DESCRIPTION:
XS GIS Cut Line= 3
      2851725.00      6984975.02      2851675.00      6985375.00
      2851975.02      6985725.02
#Sta/Elev= 30
  4584.4  458.14  4755.7  450.39  4783.4  448.30  4816.2  447.11  4886.7  446.45
  4896.8  445.66  4916.7  439.86  4964.3  439.24  4964.8  438.44  4969.8  438.44
  4970.3  439.24  5082.7  439.55  5094.6  439.86  5136.2  442.62  5143.9  443.73
  5164.8  443.69  5179.0  445.33  5185.6  445.26  5193.3  446.33  5221.8  447.96
  5228.4  447.50  5236.1  448.26  5242.7  447.89  5285.5  449.24  5314.0  448.72
  5334.9  447.61  5345.7  447.98  5363.4  448.75  5398.5  448.77  5448.5  449.63
#Mann=5,-1,0
  4584.4    0.05       0  4964.3   0.033       0  4970.3    0.05       0
  5082.7    0.16       0  5345.7    0.05       0
Bank Sta=4916.7,5094.6
Exp/Cntr=0.3,0.1

Type RM Length L Ch R = 1,950,376,376,376
BEGIN DESCRIPTION:
UNT 124 in Running Cr Watershed 2.0
END DESCRIPTION:
XS GIS Cut Line= 3
      2851424.99      6985374.97      2851525.00      6985675.00
      2851825.00      6985625.00
#Sta/Elev= 30
  4696.2  445.75  4738.4  444.52  4767.0  443.06  4801.6  440.97  4812.2  439.60
  4833.3  438.20  4843.8  436.56  4864.9  435.48  4875.4  433.85  4907.1  431.76
  4949.2  431.01  4962.5  430.24  4977.8  428.78  4978.3  427.98  4983.3  427.98
  4983.8  428.78  4991.4  429.51  5015.0  428.95  5029.0  430.24  5040.3  431.87
  5045.4  431.20  5053.0  432.92  5101.2  439.36  5106.2  439.13  5162.0  444.15
  5167.1  443.71  5222.8  447.03  5227.9  446.72  5276.0  449.15  5316.6  450.03
#Mann=4,-1,0
  4696.2    0.05       0  4767.0    0.16       0  4977.8    0.07       0
  4983.8    0.16       0
Bank Sta=4962.5,5029
Exp/Cntr=0.3,0.1

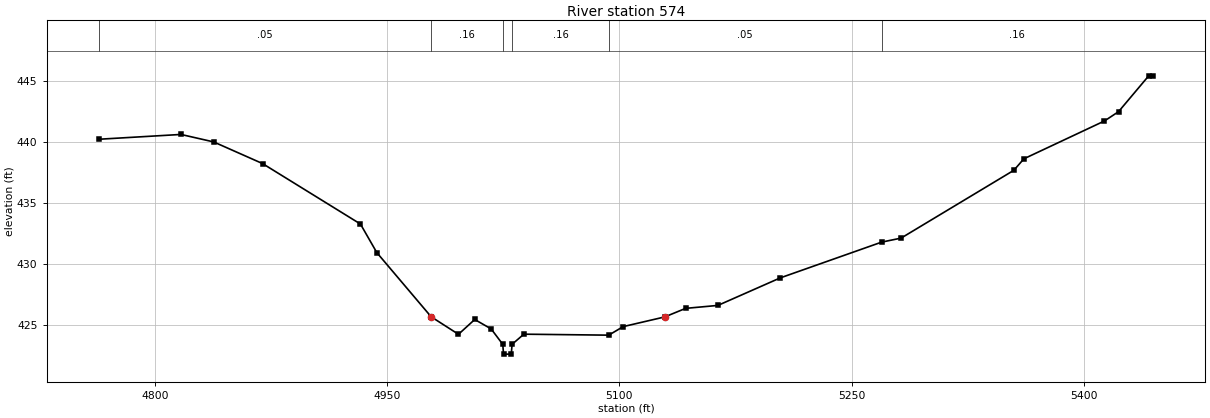
Type RM Length L Ch R = 1,574,0,0,0
BEGIN DESCRIPTION:
UNT 124 in Running Cr Watershed 1.0
END DESCRIPTION:
XS GIS Cut Line= 3
      2851225.00      6985625.01      2851325.00      6985925.00
      2851674.98      6985825.01
#Sta/Elev= 30
  4764.2  440.22  4816.9  440.61  4838.0  440.00  4869.6  438.23  4932.8  433.29
  4943.4  430.95  4978.4  425.72  4978.6  425.70  4996.1  424.28  5006.6  425.49
  5017.2  424.72  5024.7  423.46  5025.2  422.66  5030.2  422.66  5030.7  423.46
  5038.3  424.29  5093.1  424.21  5102.5  424.91  5129.3  425.70  5142.8  426.40
  5163.6  426.64  5203.9  428.89  5269.3  431.81  5281.9  432.14  5354.7  437.68
  5361.2  438.62  5413.2  441.71  5422.3  442.47  5441.8  445.40  5444.4  445.40
#Mann=6,-1,0
  4764.2    0.05       0  4978.4    0.16       0  5024.7    0.07       0
  5030.7    0.16       0  5093.1    0.05       0  5269.3    0.16       0
Bank Sta=4978.6,5129.3
Exp/Cntr=0.3,0.1

Chan Stop Cuts=-1