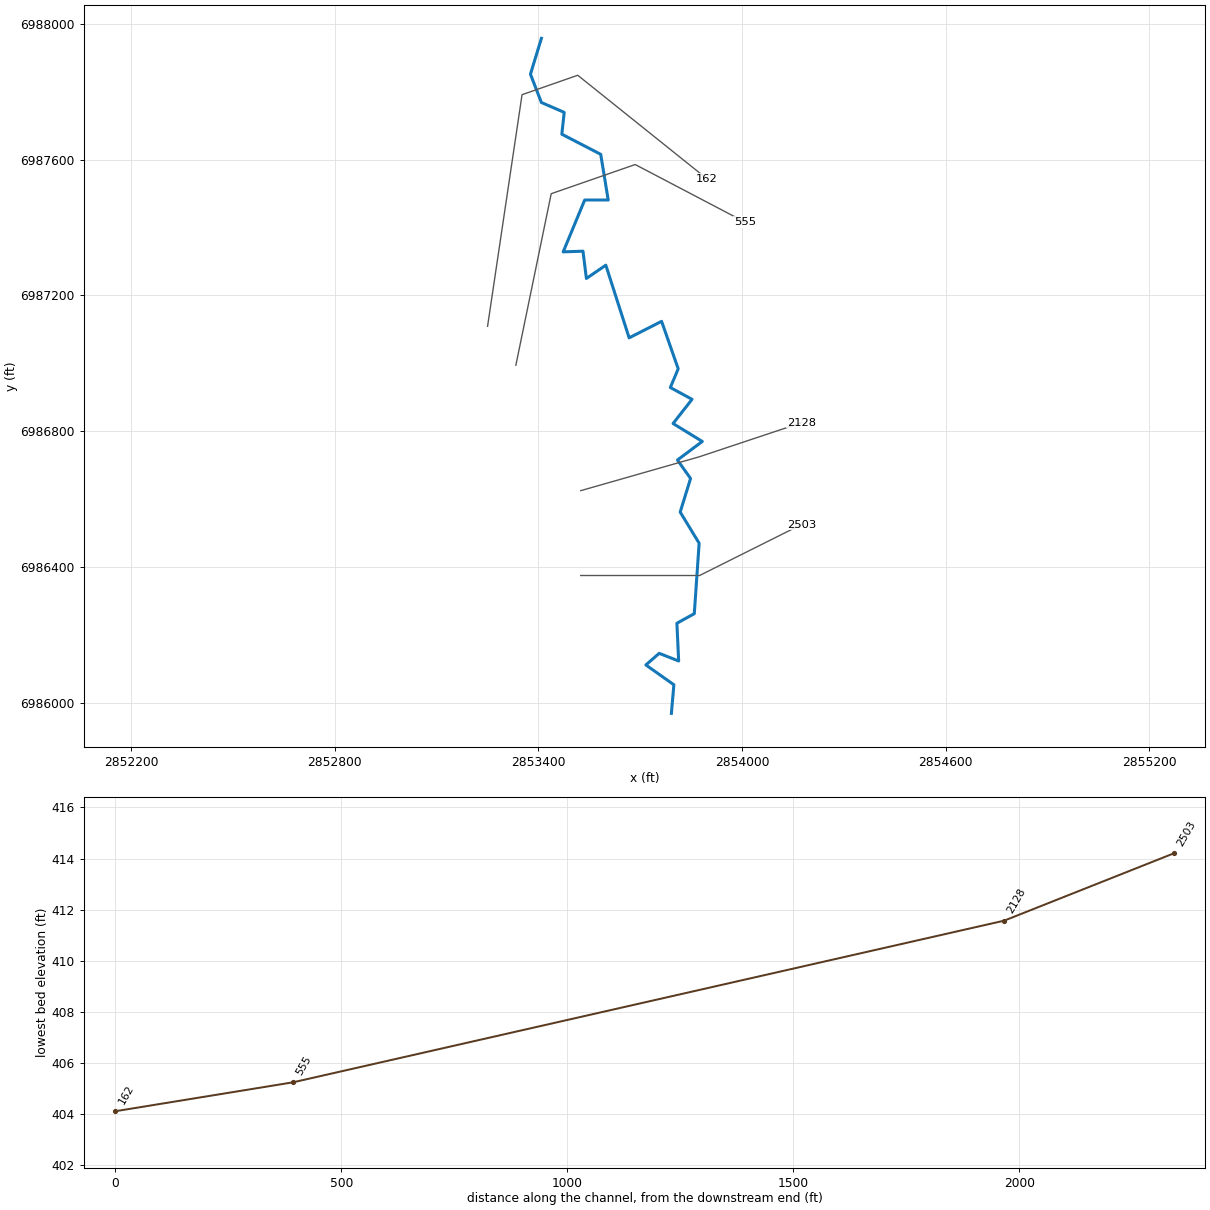
--- UNT 125 in Running Cr Watershed.prj (project) ---

Proj Title=UNT 125 in Running Cr Watershed Base Level Engineering
Current Plan=p01
Default Exp/Contr=0.3,0.1
English Units
Geom File=g01
Flow File=f01
Plan File=p01
BEGIN DESCRIPTION:
UNT 125 in Running Cr Watershed
END DESCRIPTION:

--- UNT 125 in Running Cr Watershed.p01 (plan) ---

Plan Title=Multiple Run
Short Identifier=Multiple
Geom File=g01
Flow File=f01
Subcritical Flow
K Sum by GR= 0
Std Step Tol= 0.01
Critical Tol= 0.01
Num of Std Step Trials= 20
Max Error Tol= 0.3
Flow Tol Ratio= 0.001
Split Flow NTrial= 30
Split Flow Tol= 0.02
Split Flow Ratio= 0.02
Log Output Level= 0
Friction Slope Method= 1
Unsteady Friction Slope Method= 2
Unsteady Bridges Friction Slope Method= 1
Parabolic Critical Depth
Global Vel Dist=  1 , 1 , 1
Global Log Level= 0
CheckData=True
Encroach Param= -1, 0, 0, 0
BEGIN DESCRIPTION:
Multiple Run
END DESCRIPTION:

--- UNT 125 in Running Cr Watershed.f01 (steady flow) ---

Flow Title=Multiple
Number of Profiles=7
Profile Names=10-year,25-year,50-year,1pct_min,100-year,1pct_plu,500-year
River Rch & RM= UNT 125 in Runni,Reach-1,2503
     322     416     489     287     573    1143     784
Boundary for River Rch & Prof#=UNT 125 in Runni,Reach-1,1
Up Type=0
Dn Type=3
Dn Slope=0.005
Boundary for River Rch & Prof#=UNT 125 in Runni,Reach-1,2
Up Type=0
Dn Type=3
Dn Slope=0.005
Boundary for River Rch & Prof#=UNT 125 in Runni,Reach-1,3
Up Type=0
Dn Type=3
Dn Slope=0.005
Boundary for River Rch & Prof#=UNT 125 in Runni,Reach-1,4
Up Type=0
Dn Type=3
Dn Slope=0.005
Boundary for River Rch & Prof#=UNT 125 in Runni,Reach-1,5
Up Type=0
Dn Type=3
Dn Slope=0.005
Boundary for River Rch & Prof#=UNT 125 in Runni,Reach-1,6
Up Type=0
Dn Type=3
Dn Slope=0.005
Boundary for River Rch & Prof#=UNT 125 in Runni,Reach-1,7
Up Type=0
Dn Type=3
Dn Slope=0.005

--- UNT 125 in Running Cr Watershed.g01 (geometry) ---

Geom Title=Existing Conditions

River Reach=UNT 125 in Runni,Reach-1
Reach XY= 30
      2853791.98      6985968.84      2853799.34      6986053.11
      2853716.78      6986111.51      2853756.11      6986145.71
      2853813.40      6986123.15      2853808.22      6986234.34
      2853859.47      6986262.61      2853873.75      6986470.12
      2853817.93      6986561.92      2853848.48      6986660.86
      2853809.88      6986715.26      2853883.05      6986769.95
      2853796.95      6986822.75      2853852.81      6986894.07
      2853788.90      6986928.87      2853812.08      6986983.99
      2853763.15      6987123.82      2853667.53      6987075.16
      2853598.84      6987289.31      2853541.56      6987250.12
      2853531.51      6987330.51      2853473.23      6987328.50
      2853536.54      6987481.24      2853605.87      6987481.24
      2853583.76      6987615.89      2853469.21      6987675.17
      2853476.24      6987739.48      2853408.92      6987768.62
      2853376.76      6987852.03      2853409.09      6987957.58

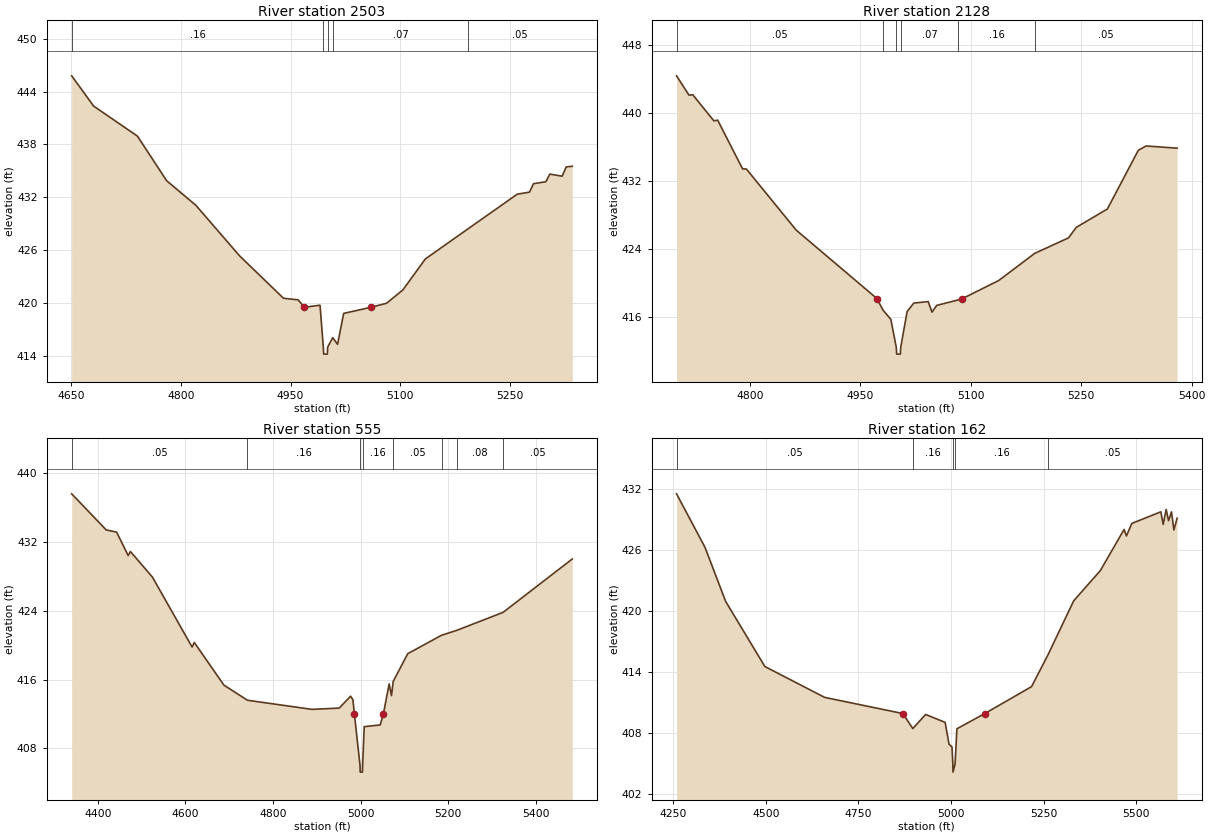
Type RM Length L Ch R = 1,2503,375,375,375
BEGIN DESCRIPTION:
UNT 125 in Running Cr Watershed 4.0
END DESCRIPTION:
XS GIS Cut Line= 3
      2853524.96      6986375.00      2853875.00      6986375.00
      2854174.96      6986524.98
#Sta/Elev= 30
  4650.4  445.78  4680.4  442.35  4740.4  438.94  4780.4  433.88  4820.4  431.09
  4880.4  425.34  4940.4  420.54  4960.4  420.36  4969.1  419.52  4990.4  419.75
  4994.9  415.00  4995.4  414.20  5000.4  414.20  5000.9  415.00  5007.8  416.07
  5014.4  415.31  5022.8  418.82  5060.3  419.52  5081.5  419.97  5103.9  421.49
  5134.6  425.00  5193.1  428.42  5260.4  432.35  5277.2  432.58  5282.7  433.54
  5299.5  433.76  5305.1  434.63  5321.9  434.39  5327.5  435.44  5335.8  435.52
#Mann=5,-1,0
  4650.4    0.16       0  4994.9    0.07       0  5000.9    0.16       0
  5007.8    0.07       0  5193.1    0.05       0
Bank Sta=4969.1,5060.3
Exp/Cntr=0.3,0.1

Type RM Length L Ch R = 1,2128,1573,1573,1573
BEGIN DESCRIPTION:
UNT 125 in Running Cr Watershed 3.0
END DESCRIPTION:
XS GIS Cut Line= 3
      2853525.01      6986625.00      2853875.00      6986725.00
      2854174.98      6986824.99
#Sta/Elev= 30
  4700.1  444.34  4717.0  442.07  4722.2  442.11  4750.8  439.04  4756.0  439.12
  4789.8  433.39  4795.0  433.37  4862.6  426.18  4972.4  418.11  4980.6  416.76
  4991.3  415.66  4998.7  412.37  4999.2  411.57  5004.2  411.57  5004.7  412.37
  5013.4  416.58  5022.5  417.58  5042.0  417.76  5047.2  416.52  5053.7  417.31
  5083.1  417.96  5088.6  418.11  5137.9  420.24  5186.7  423.43  5232.7  425.26
  5243.3  426.50  5285.5  428.66  5327.6  435.58  5338.2  436.08  5380.3  435.82
#Mann=6,-1,0
  4700.1    0.05       0  4980.6    0.07       0  4998.7    0.07       0
  5004.7    0.07       0  5083.1    0.16       0  5186.7    0.05       0
Bank Sta=4972.4,5088.6
Exp/Cntr=0.3,0.1

Type RM Length L Ch R = 1,555,393,393,393
BEGIN DESCRIPTION:
UNT 125 in Running Cr Watershed 2.0
END DESCRIPTION:
XS GIS Cut Line= 4
      2853333.78      6986994.61      2853437.95      6987499.84
      2853685.35      6987585.78      2854008.22      6987416.53
#Sta/Elev= 30
  4340.5  437.58  4419.2  433.39  4443.0  433.13  4469.4  430.41  4474.5  430.88
  4524.8  427.90  4615.2  419.78  4620.3  420.31  4688.0  415.35  4741.6  413.60
  4888.8  412.54  4951.0  412.69  4976.9  414.07  4982.2  413.66  4985.7  411.95
  4998.4  406.05  4998.9  405.25  5003.9  405.25  5004.4  406.05  5008.0  410.53
  5044.4  410.73  5051.5  411.95  5064.9  415.50  5070.2  414.14  5074.2  415.79
  5107.3  419.01  5184.5  421.15  5219.7  421.73  5324.9  423.81  5482.8  430.01
#Mann=8,-1,0
  4340.5    0.05       0  4741.6    0.16       0  4998.4    0.07       0
  5004.4    0.16       0  5074.2    0.05       0  5184.5    0.16       0
  5219.7    0.08       0  5324.9    0.05       0
Bank Sta=4985.7,5051.5
Exp/Cntr=0.3,0.1

Type RM Length L Ch R = 1,162,0,0,0
BEGIN DESCRIPTION:
UNT 125 in Running Cr Watershed 1.0
END DESCRIPTION:
XS GIS Cut Line= 4
      2853250.44      6987109.17      2853352.01      6987791.51
      2853516.08      6987848.80      2853896.31      6987544.09
#Sta/Elev= 30
  4259.4  431.53  4336.1  426.27  4392.0  420.93  4497.8  414.52  4659.2  411.48
  4870.1  409.89  4897.0  408.41  4931.6  409.80  4984.2  409.02  4994.8  406.87
  5002.7  406.60  5005.0  404.92  5005.5  404.12  5011.0  404.92  5016.0  408.39
  5091.3  409.89  5217.4  412.54  5261.5  415.65  5331.1  420.99  5403.1  423.97
  5467.1  428.02  5473.5  427.38  5487.9  428.61  5566.3  429.76  5572.7  428.52
  5580.7  429.99  5587.1  428.89  5595.1  429.75  5601.5  427.97  5610.3  429.13
#Mann=5,-1,0
  4259.4    0.05       0  4897.0    0.16       0  5005.0    0.07       0
  5011.0    0.16       0  5261.5    0.05       0
Bank Sta=4870.1,5091.3
Exp/Cntr=0.3,0.1

Chan Stop Cuts=-1