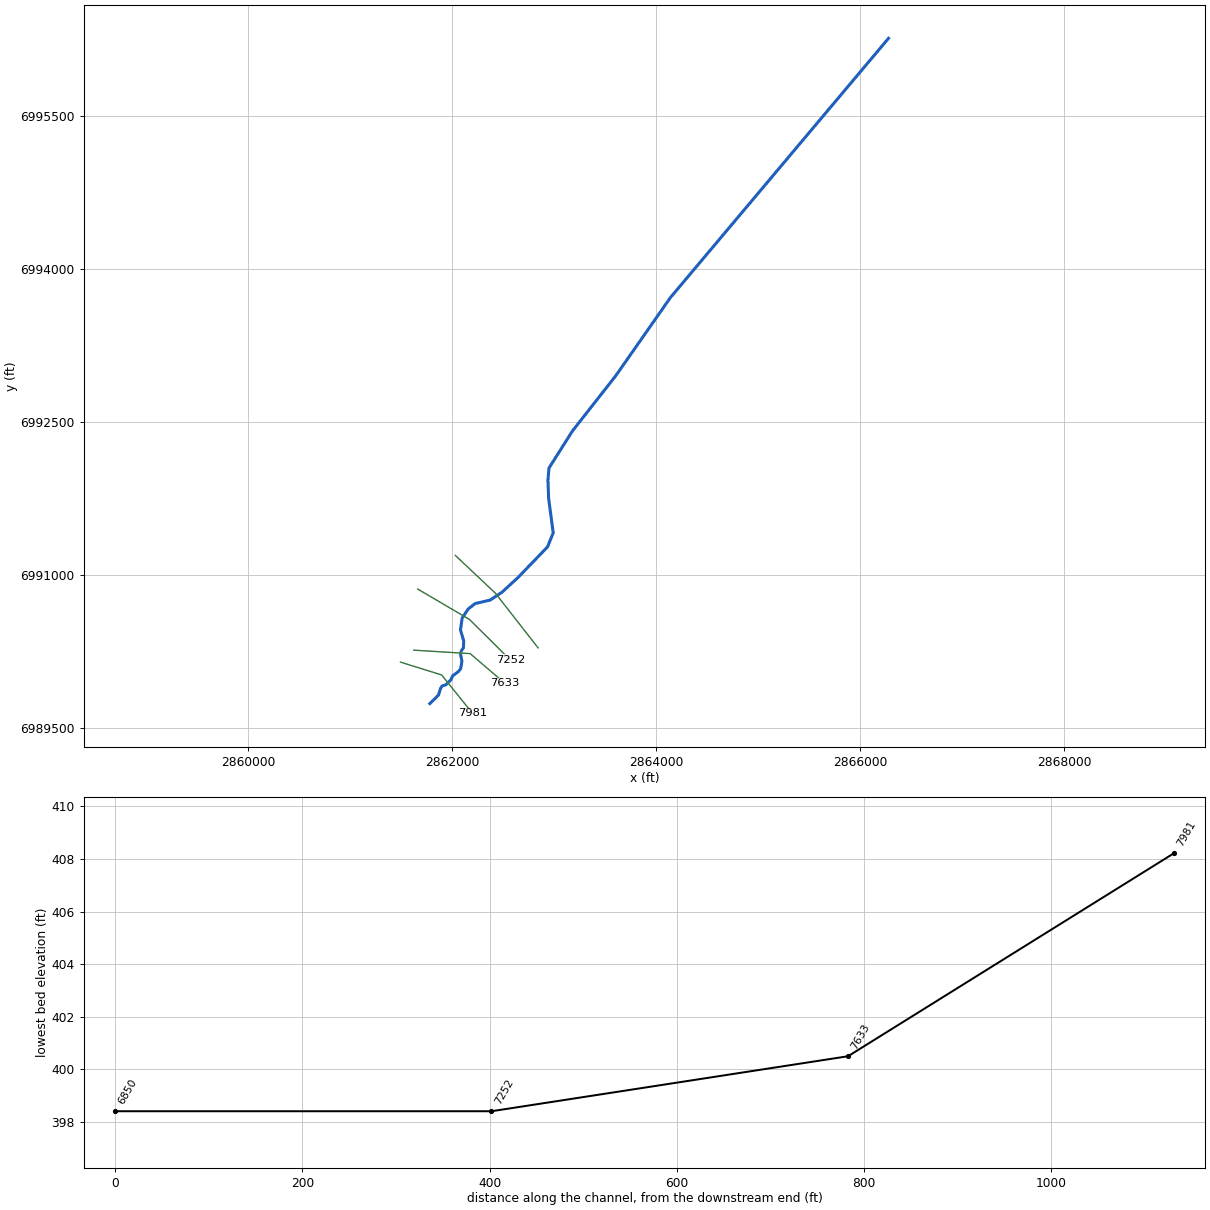
--- UNT 126 in Running Cr Watershed.prj (project) ---

Proj Title=UNT 126 in Running Cr Watershed Base Level Engineering
Current Plan=p01
Default Exp/Contr=0.3,0.1
English Units
Geom File=g01
Flow File=f01
Plan File=p01
BEGIN DESCRIPTION:
UNT 126 in Running Cr Watershed
END DESCRIPTION:

--- UNT 126 in Running Cr Watershed.p01 (plan) ---

Plan Title=Multiple Run
Short Identifier=Multiple
Geom File=g01
Flow File=f01
Subcritical Flow
K Sum by GR= 0
Std Step Tol= 0.01
Critical Tol= 0.01
Num of Std Step Trials= 20
Max Error Tol= 0.3
Flow Tol Ratio= 0.001
Split Flow NTrial= 30
Split Flow Tol= 0.02
Split Flow Ratio= 0.02
Log Output Level= 0
Friction Slope Method= 1
Unsteady Friction Slope Method= 2
Unsteady Bridges Friction Slope Method= 1
Parabolic Critical Depth
Global Vel Dist=  1 , 1 , 1
Global Log Level= 0
CheckData=True
Encroach Param= -1, 0, 0, 0
BEGIN DESCRIPTION:
Multiple Run
END DESCRIPTION:

--- UNT 126 in Running Cr Watershed.f01 (steady flow) ---

Flow Title=Multiple
Number of Profiles=7
Profile Names=10-year,25-year,50-year,1pct_min,100-year,1pct_plu,500-year
River Rch & RM= UNT 126 in Runni,Reach-1,7981
     368     477     562     329     657    1311     899
Boundary for River Rch & Prof#=UNT 126 in Runni,Reach-1,1
Up Type=0
Dn Type=3
Dn Slope=0.005
Boundary for River Rch & Prof#=UNT 126 in Runni,Reach-1,2
Up Type=0
Dn Type=3
Dn Slope=0.005
Boundary for River Rch & Prof#=UNT 126 in Runni,Reach-1,3
Up Type=0
Dn Type=3
Dn Slope=0.005
Boundary for River Rch & Prof#=UNT 126 in Runni,Reach-1,4
Up Type=0
Dn Type=3
Dn Slope=0.005
Boundary for River Rch & Prof#=UNT 126 in Runni,Reach-1,5
Up Type=0
Dn Type=3
Dn Slope=0.005
Boundary for River Rch & Prof#=UNT 126 in Runni,Reach-1,6
Up Type=0
Dn Type=3
Dn Slope=0.005
Boundary for River Rch & Prof#=UNT 126 in Runni,Reach-1,7
Up Type=0
Dn Type=3
Dn Slope=0.005

--- UNT 126 in Running Cr Watershed.g01 (geometry) ---

Geom Title=Existing Conditions

River Reach=UNT 126 in Runni,Reach-1
Reach XY= 30
      2861782.13      6989743.38      2861866.09      6989825.56
      2861887.52      6989893.44      2861903.60      6989916.66
      2861939.32      6989927.38      2861987.56      6989975.61
      2862005.42      6990014.91      2862062.58      6990057.78
      2862084.02      6990084.57      2862096.52      6990159.60
      2862082.23      6990231.05      2862092.95      6990264.99
      2862110.81      6990286.43      2862114.38      6990356.09
      2862082.23      6990465.06      2862098.31      6990579.39
      2862157.26      6990670.49      2862226.92      6990724.08
      2862373.40      6990758.02      2862491.30      6990836.62
      2862646.71      6990979.52      2862936.10      6991279.63
      2862991.47      6991417.17      2862946.81      6991753.00
      2862939.67      6991933.42      2862950.39      6992053.11
      2863181.99      6992418.45      2863603.96      6992956.13
      2864141.64      6993725.20      2866278.75      6996265.44

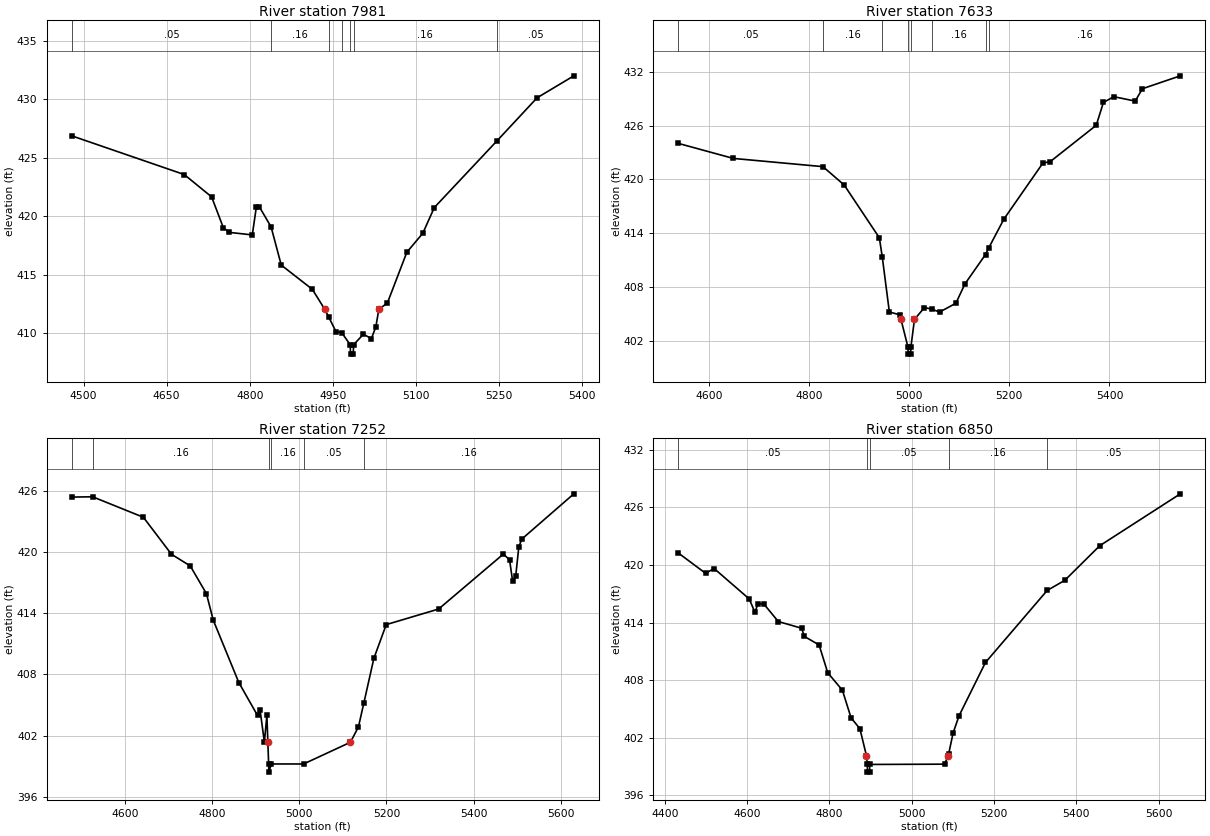
Type RM Length L Ch R = 1,7981,348,348,348
BEGIN DESCRIPTION:
UNT 126 in Running Cr Watershed 15.0
END DESCRIPTION:
XS GIS Cut Line= 3
      2861493.91      6990149.80      2861897.58      6990023.92
      2862200.71      6989647.17
#Sta/Elev= 30
  4478.8  426.87  4681.9  423.56  4731.3  421.65  4752.3  419.03  4762.8  418.62
  4804.7  418.40  4812.0  420.78  4817.2  420.82  4838.6  419.09  4857.0  415.82
  4913.1  413.75  4935.4  412.05  4943.0  411.35  4955.7  410.14  4966.1  410.05
  4981.5  409.01  4982.0  408.21  4987.0  408.21  4987.5  409.01  5005.3  409.91
  5019.7  409.54  5027.7  410.53  5033.2  412.05  5048.5  412.57  5083.7  416.92
  5112.5  418.54  5133.3  420.74  5246.8  426.46  5318.8  430.12  5385.2  432.00
#Mann=7,-1,0
  4478.8    0.05       0  4838.6    0.16       0  4943.0    0.12       0
  4966.1    0.16       0  4981.5    0.07       0  4987.5    0.16       0
  5246.8    0.05       0
Bank Sta=4935.4,5033.2
Exp/Cntr=0.3,0.1

Type RM Length L Ch R = 1,7633,381,381,381
BEGIN DESCRIPTION:
UNT 126 in Running Cr Watershed 14.0
END DESCRIPTION:
XS GIS Cut Line= 3
      2861624.10      6990266.98      2862177.62      6990232.91
      2862518.27      6989941.43
#Sta/Elev= 30
  4538.6  424.03  4648.5  422.35  4827.7  421.43  4870.1  419.38  4940.3  413.49
  4946.1  411.37  4960.3  405.21  4981.5  404.88  4983.5  404.38  4997.4  401.30
  4997.9  400.50  5002.9  400.50  5003.4  401.30  5010.5  404.38  5030.4  405.70
  5045.4  405.52  5060.5  405.19  5093.2  406.18  5111.2  408.33  5152.4  411.62
  5159.1  412.39  5189.2  415.58  5267.1  421.84  5281.4  421.98  5373.6  426.05
  5387.9  428.60  5408.7  429.24  5451.4  428.75  5465.8  430.13  5541.5  431.57
#Mann=8,-1,0
  4538.6    0.05       0  4827.7    0.16       0  4946.1    0.12       0
  4997.4    0.07       0  5003.4    0.12       0  5045.4    0.16       0
  5152.4    0.12       0  5159.1    0.16       0
Bank Sta=4983.5,5010.5
Exp/Cntr=0.3,0.1

Type RM Length L Ch R = 1,7252,402,402,402
BEGIN DESCRIPTION:
UNT 126 in Running Cr Watershed 13.0
END DESCRIPTION:
XS GIS Cut Line= 3
      2861663.17      6990865.96      2862170.67      6990567.91
      2862570.14      6990171.68
#Sta/Elev= 30
  4478.5  425.39  4526.3  425.42  4642.7  423.41  4707.1  419.78  4750.1  418.64
  4787.2  415.92  4802.9  413.32  4861.5  407.20  4904.4  403.97  4910.2  404.52
  4920.1  401.36  4925.9  403.98  4928.1  401.34  4929.9  399.21  4930.4  398.41
  4935.9  399.21  5010.1  399.21  5117.5  401.34  5135.8  402.85  5148.4  405.23
  5171.2  409.57  5199.5  412.88  5319.7  414.41  5468.1  419.80  5482.3  419.24
  5489.4  417.12  5496.4  417.63  5503.5  420.51  5510.6  421.28  5629.7  425.71
#Mann=6,-1,0
  4478.5    0.05       0  4526.3    0.16       0  4929.9    0.07       0
  4935.9    0.16       0  5010.1    0.05       0  5148.4    0.16       0
Bank Sta=4928.1,5117.5
Exp/Cntr=0.3,0.1

Type RM Length L Ch R = 1,6850,0,0,0
BEGIN DESCRIPTION:
UNT 126 in Running Cr Watershed 12.0
END DESCRIPTION:
XS GIS Cut Line= 3
      2862032.13      6991195.79      2862425.00      6990825.00
      2862843.23      6990289.35
#Sta/Elev= 30
  4432.6  421.26  4498.9  419.14  4519.9  419.63  4604.9  416.47  4619.0  415.07
  4626.3  415.97  4640.5  415.94  4675.7  414.11  4732.3  413.41  4739.2  412.55
  4774.8  411.67  4795.8  408.77  4831.4  406.95  4852.5  404.07  4873.9  402.94
  4889.9  400.12  4891.9  399.21  4892.4  398.41  4897.4  398.41  4897.9  399.21
  5079.5  399.24  5088.5  400.12  5089.6  400.31  5100.4  402.49  5114.8  404.28
  5179.0  409.84  5329.0  417.35  5371.7  418.40  5456.7  422.01  5652.4  427.42
#Mann=5,-1,0
  4432.6    0.05       0  4891.9   0.033       0  4897.9    0.05       0
  5089.6    0.16       0  5329.0    0.05       0
Bank Sta=4889.9,5088.5
Exp/Cntr=0.3,0.1

Chan Stop Cuts=-1