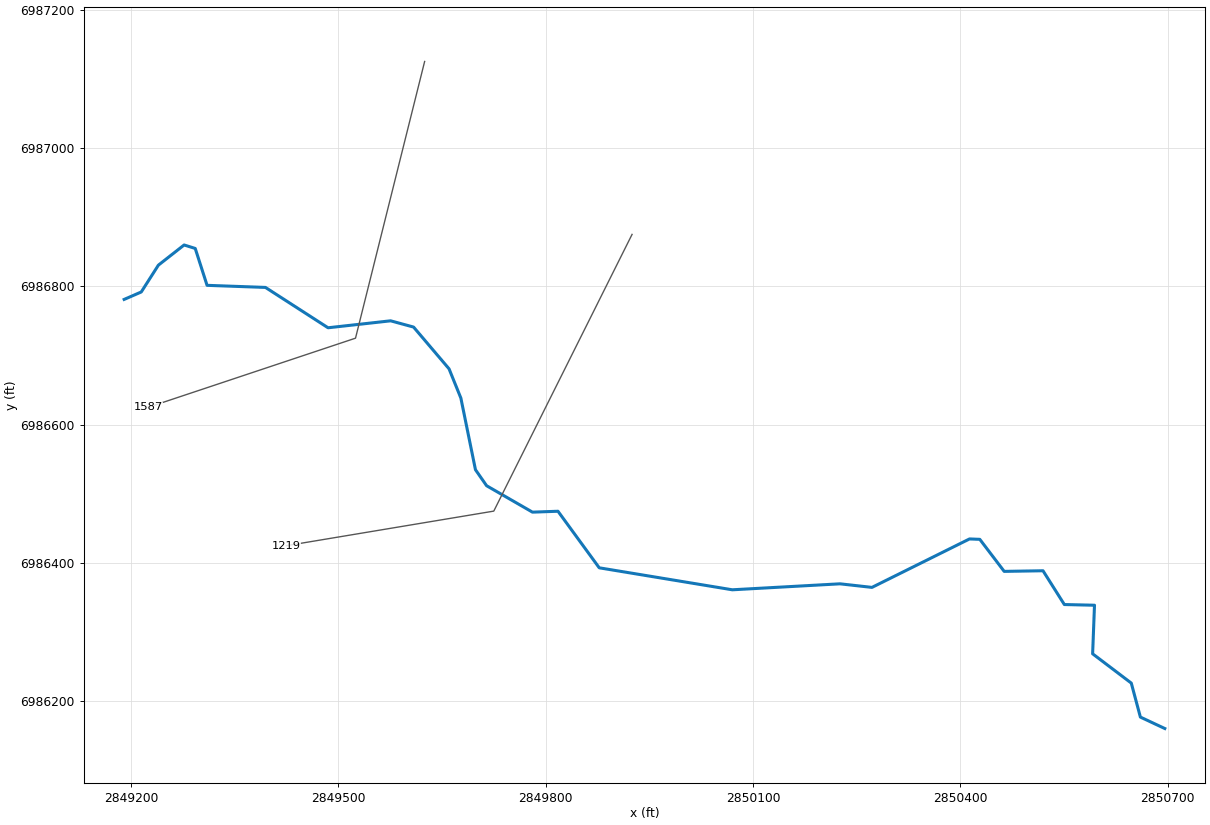
--- UNT 127 in Running Cr Watershed.prj (project) ---

Proj Title=UNT 127 in Running Cr Watershed Base Level Engineering
Current Plan=p01
Default Exp/Contr=0.3,0.1
English Units
Geom File=g01
Flow File=f01
Plan File=p01
BEGIN DESCRIPTION:
UNT 127 in Running Cr Watershed
END DESCRIPTION:

--- UNT 127 in Running Cr Watershed.p01 (plan) ---

Plan Title=Multiple Run
Short Identifier=Multiple
Geom File=g01
Flow File=f01
Subcritical Flow
K Sum by GR= 0
Std Step Tol= 0.01
Critical Tol= 0.01
Num of Std Step Trials= 20
Max Error Tol= 0.3
Flow Tol Ratio= 0.001
Split Flow NTrial= 30
Split Flow Tol= 0.02
Split Flow Ratio= 0.02
Log Output Level= 0
Friction Slope Method= 1
Unsteady Friction Slope Method= 2
Unsteady Bridges Friction Slope Method= 1
Parabolic Critical Depth
Global Vel Dist=  1 , 1 , 1
Global Log Level= 0
CheckData=True
Encroach Param= -1, 0, 0, 0
BEGIN DESCRIPTION:
Multiple Run
END DESCRIPTION:

--- UNT 127 in Running Cr Watershed.f01 (steady flow) ---

Flow Title=Multiple
Number of Profiles=7
Profile Names=10-year,25-year,50-year,1pct_min,100-year,1pct_plu,500-year
River Rch & RM= UNT 127 in Runni,Reach-1,1587
     277     354     414     242     482     962     653
Boundary for River Rch & Prof#=UNT 127 in Runni,Reach-1,1
Up Type=0
Dn Type=3
Dn Slope=0.005
Boundary for River Rch & Prof#=UNT 127 in Runni,Reach-1,2
Up Type=0
Dn Type=3
Dn Slope=0.005
Boundary for River Rch & Prof#=UNT 127 in Runni,Reach-1,3
Up Type=0
Dn Type=3
Dn Slope=0.005
Boundary for River Rch & Prof#=UNT 127 in Runni,Reach-1,4
Up Type=0
Dn Type=3
Dn Slope=0.005
Boundary for River Rch & Prof#=UNT 127 in Runni,Reach-1,5
Up Type=0
Dn Type=3
Dn Slope=0.005
Boundary for River Rch & Prof#=UNT 127 in Runni,Reach-1,6
Up Type=0
Dn Type=3
Dn Slope=0.005
Boundary for River Rch & Prof#=UNT 127 in Runni,Reach-1,7
Up Type=0
Dn Type=3
Dn Slope=0.005

--- UNT 127 in Running Cr Watershed.g01 (geometry) ---

Geom Title=Existing Conditions

River Reach=UNT 127 in Runni,Reach-1
Reach XY= 30
      2849190.36      6986781.02      2849215.11      6986791.78
      2849239.87      6986830.55      2849277.09      6986859.72
      2849293.18      6986854.69      2849310.28      6986801.38
      2849394.76      6986798.36      2849485.28      6986740.03
      2849575.80      6986750.09      2849608.99      6986741.04
      2849660.29      6986680.69      2849677.38      6986638.45
      2849698.50      6986534.85      2849714.60      6986511.72
      2849780.98      6986473.50      2849817.86      6986474.80
      2849877.53      6986393.04      2850070.02      6986361.26
      2850225.77      6986369.90      2850272.03      6986364.74
      2850413.12      6986434.77      2850428.03      6986434.18
      2850463.27      6986387.88      2850519.41      6986388.78
      2850550.28      6986339.95      2850593.89      6986338.94
      2850591.20      6986268.74      2850647.12      6986226.37
      2850660.27      6986177.25      2850695.59      6986160.71

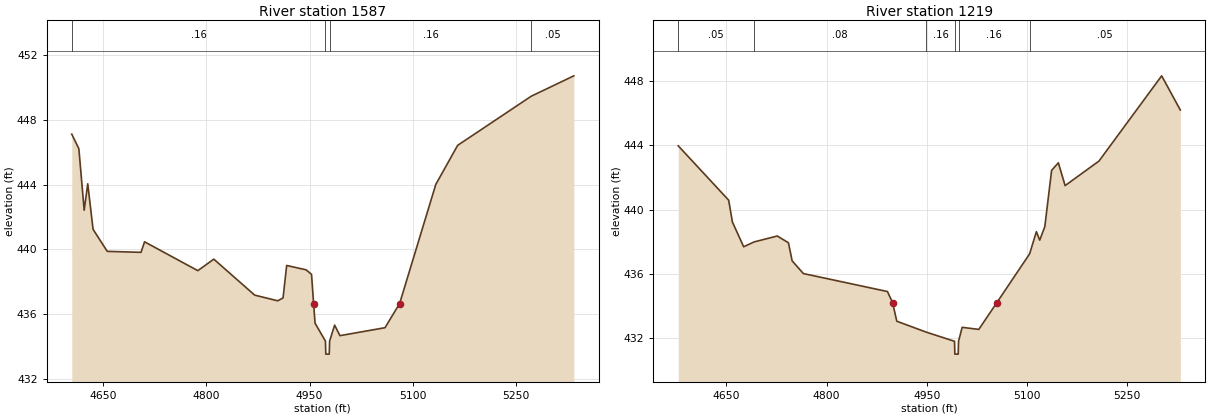
Type RM Length L Ch R = 1,1587,368,368,368
BEGIN DESCRIPTION:
UNT 127 in Running Cr Watershed 2.0
END DESCRIPTION:
XS GIS Cut Line= 3
      2849624.99      6987124.98      2849525.00      6986725.00
      2849225.02      6986625.01
#Sta/Elev= 30
  4604.9  447.11  4615.2  446.21  4622.9  442.42  4628.1  444.05  4635.8  441.24
  4656.4  439.88  4705.4  439.82  4710.5  440.47  4787.8  438.69  4811.0  439.40
  4870.3  437.18  4903.8  436.83  4911.5  437.01  4916.7  439.01  4945.0  438.74
  4952.8  438.46  4955.8  436.66  4957.9  435.45  4973.0  434.34  4973.5  433.54
  4978.5  433.54  4979.0  434.34  4986.3  435.33  4994.0  434.68  5059.4  435.17
  5080.6  436.66  5133.1  444.01  5164.8  446.42  5271.5  449.45  5333.4  450.71
#Mann=4,-1,0
  4604.9    0.16       0  4973.0    0.07       0  4979.0    0.16       0
  5271.5    0.05       0
Bank Sta=4955.8,5080.6
Exp/Cntr=0.3,0.1

Type RM Length L Ch R = 1,1219,0,0,0
BEGIN DESCRIPTION:
UNT 127 in Running Cr Watershed 1.0
END DESCRIPTION:
XS GIS Cut Line= 3
      2849925.02      6986875.03      2849725.00      6986475.00
      2849424.99      6986425.00
#Sta/Elev= 30
  4577.9  443.97  4653.4  440.58  4659.0  439.22  4675.8  437.68  4691.4  437.98
  4726.1  438.35  4742.8  437.93  4748.4  436.80  4765.2  436.01  4891.0  434.89
  4898.8  434.19  4905.0  433.04  4949.1  432.36  4991.4  431.79  4991.9  430.99
  4996.9  430.99  4997.4  431.79  5002.8  432.66  5027.7  432.53  5054.6  434.19
  5103.8  437.24  5113.9  438.62  5118.9  438.09  5126.5  438.93  5136.7  442.44
  5146.8  442.91  5156.9  441.49  5207.6  443.02  5301.4  448.33  5329.3  446.20
#Mann=6,-1,0
  4577.9    0.05       0  4691.4    0.08       0  4949.1    0.16       0
  4991.4    0.07       0  4997.4    0.16       0  5103.8    0.05       0
Bank Sta=4898.8,5054.6
Exp/Cntr=0.3,0.1

Chan Stop Cuts=-1