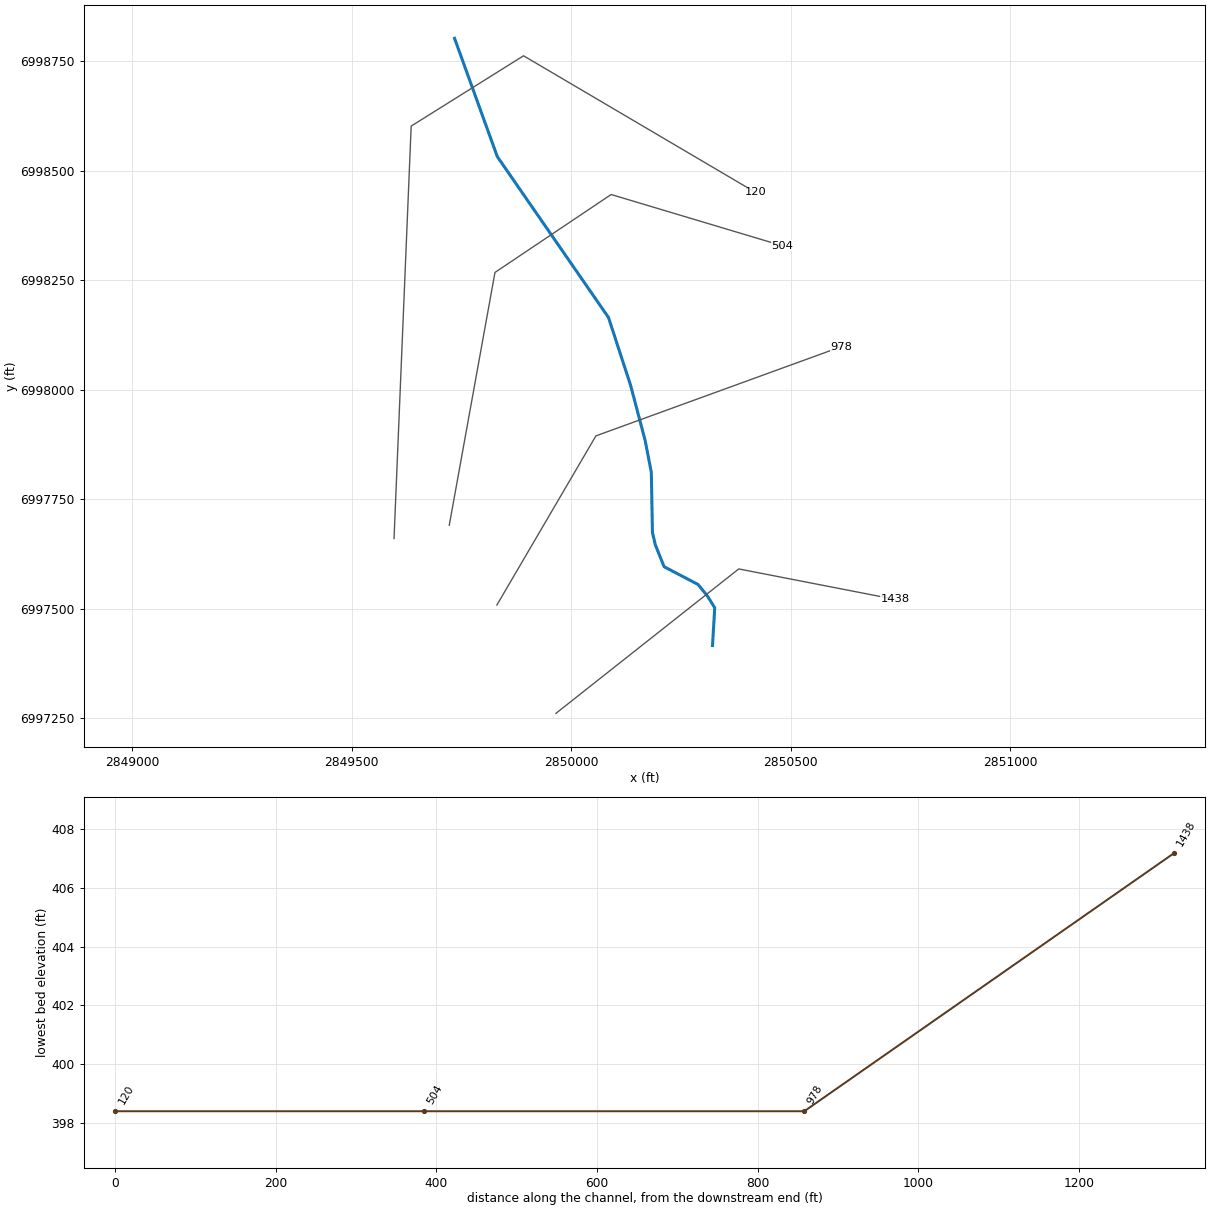
--- UNT 128 in Running Cr Watershed.prj (project) ---

Proj Title=UNT 128 in Running Cr Watershed Base Level Engineering
Current Plan=p01
Default Exp/Contr=0.3,0.1
English Units
Geom File=g01
Flow File=f01
Plan File=p01
BEGIN DESCRIPTION:
UNT 128 in Running Cr Watershed
END DESCRIPTION:

--- UNT 128 in Running Cr Watershed.p01 (plan) ---

Plan Title=Multiple Run
Short Identifier=Multiple
Geom File=g01
Flow File=f01
Subcritical Flow
K Sum by GR= 0
Std Step Tol= 0.01
Critical Tol= 0.01
Num of Std Step Trials= 20
Max Error Tol= 0.3
Flow Tol Ratio= 0.001
Split Flow NTrial= 30
Split Flow Tol= 0.02
Split Flow Ratio= 0.02
Log Output Level= 0
Friction Slope Method= 1
Unsteady Friction Slope Method= 2
Unsteady Bridges Friction Slope Method= 1
Parabolic Critical Depth
Global Vel Dist=  1 , 1 , 1
Global Log Level= 0
CheckData=True
Encroach Param= -1, 0, 0, 0
BEGIN DESCRIPTION:
Multiple Run
END DESCRIPTION:

--- UNT 128 in Running Cr Watershed.f01 (steady flow) ---

Flow Title=Multiple
Number of Profiles=7
Profile Names=10-year,25-year,50-year,1pct_min,100-year,1pct_plu,500-year
River Rch & RM= UNT 128 in Runni,Reach-1,1438
     164     203     232     133     265     529     344
Boundary for River Rch & Prof#=UNT 128 in Runni,Reach-1,1
Up Type=0
Dn Type=3
Dn Slope=0.005
Boundary for River Rch & Prof#=UNT 128 in Runni,Reach-1,2
Up Type=0
Dn Type=3
Dn Slope=0.005
Boundary for River Rch & Prof#=UNT 128 in Runni,Reach-1,3
Up Type=0
Dn Type=3
Dn Slope=0.005
Boundary for River Rch & Prof#=UNT 128 in Runni,Reach-1,4
Up Type=0
Dn Type=3
Dn Slope=0.005
Boundary for River Rch & Prof#=UNT 128 in Runni,Reach-1,5
Up Type=0
Dn Type=3
Dn Slope=0.005
Boundary for River Rch & Prof#=UNT 128 in Runni,Reach-1,6
Up Type=0
Dn Type=3
Dn Slope=0.005
Boundary for River Rch & Prof#=UNT 128 in Runni,Reach-1,7
Up Type=0
Dn Type=3
Dn Slope=0.005

--- UNT 128 in Running Cr Watershed.g01 (geometry) ---

Geom Title=Existing Conditions

River Reach=UNT 128 in Runni,Reach-1
Reach XY= 13
      2850322.15      6997415.47      2850327.22      6997501.65
      2850310.74      6997528.27      2850289.20      6997554.88
      2850211.88      6997595.44      2850191.61      6997646.14
      2850185.27      6997674.02      2850182.73      6997810.90
      2850168.79      6997883.14      2850135.84      6998008.61
      2850085.15      6998164.50      2849831.67      6998532.04
      2849734.27      6998802.11

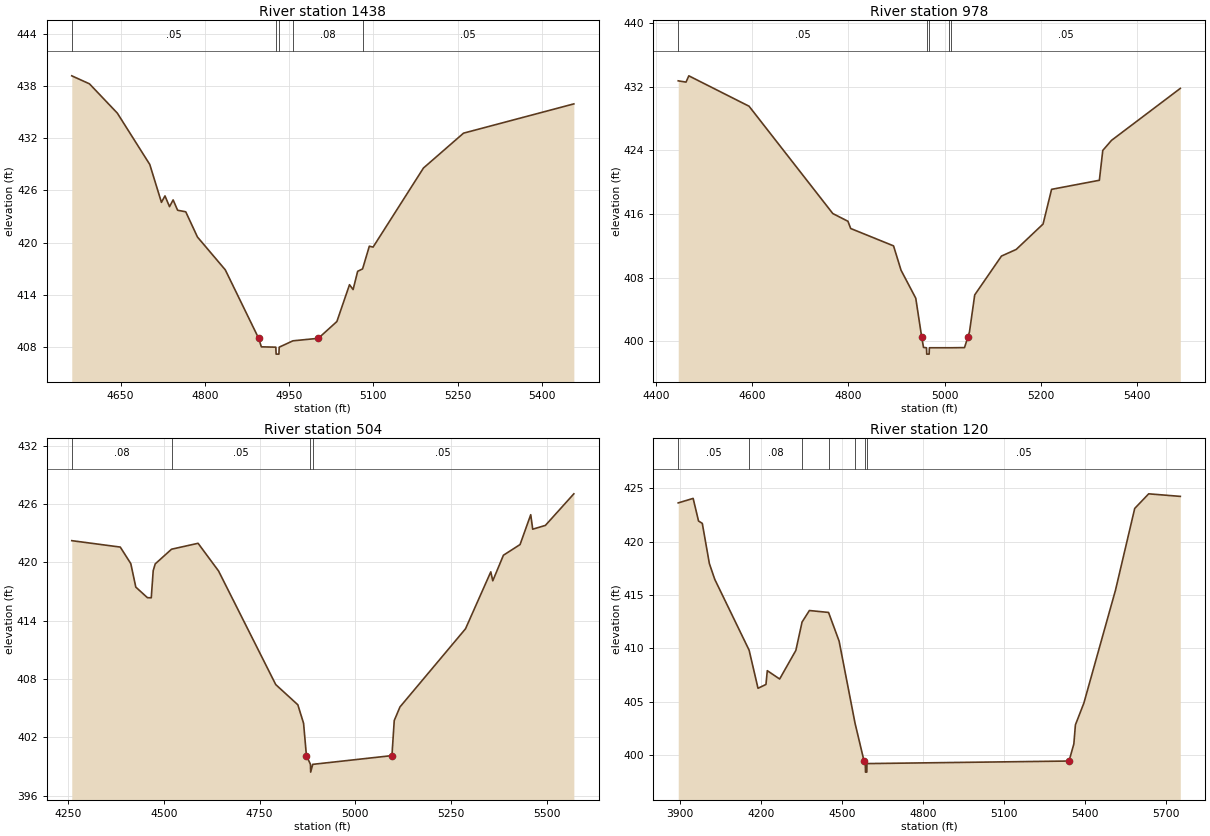
Type RM Length L Ch R = 1,1438,460,460,460
BEGIN DESCRIPTION:
UNT 128 in Running Cr Watershed 3.0
END DESCRIPTION:
XS GIS Cut Line= 3
      2849965.27      6997260.54      2850381.95      6997590.41
      2850737.89      6997520.95
#Sta/Elev= 30
  4563.0  439.19  4594.5  438.27  4644.1  434.90  4701.9  428.99  4722.7  424.63
  4729.0  425.37  4737.1  424.13  4743.5  424.91  4751.5  423.72  4766.0  423.54
  4786.8  420.64  4836.4  416.86  4895.8  408.98  4900.6  408.00  4926.4  407.96
  4926.9  407.16  4931.9  407.16  4932.4  407.96  4956.8  408.69  5002.1  408.98
  5035.1  410.91  5057.6  415.15  5064.0  414.59  5072.1  416.69  5080.9  416.97
  5092.9  419.58  5099.6  419.48  5189.3  428.58  5260.6  432.59  5457.1  435.96
#Mann=5,-1,0
  4563.0    0.05       0  4926.4    0.07       0  4932.4    0.05       0
  4956.8    0.08       0  5080.9    0.05       0
Bank Sta=4895.8,5002.1
Exp/Cntr=0.3,0.1

Type RM Length L Ch R = 1,978,474,474,474
BEGIN DESCRIPTION:
Mapping XS abea6b1a
END DESCRIPTION:
XS GIS Cut Line= 3
      2849830.74      6997507.95      2850056.43      6997894.22
      2850616.34      6998098.23
#Sta/Elev= 30
  4446.3  432.74  4462.5  432.58  4468.3  433.37  4593.5  429.55  4767.5  416.07
  4798.9  415.10  4804.7  414.19  4893.7  412.01  4909.3  408.95  4939.9  405.43
  4952.2  400.56  4956.0  399.25  4962.2  399.21  4962.7  398.41  4967.7  398.41
  4968.2  399.21  5009.2  399.21  5013.6  399.21  5041.2  399.23  5048.2  400.56
  5051.5  401.20  5062.4  405.85  5118.0  410.73  5148.6  411.56  5204.4  414.75
  5222.1  419.11  5321.4  420.25  5328.5  424.00  5346.6  425.26  5489.6  431.79
#Mann=5,-1,0
  4446.3    0.05       0  4962.2    0.03       0  4968.2    0.05       0
  5009.2     0.1       0  5013.6    0.05       0
Bank Sta=4952.2,5048.2
Exp/Cntr=0.3,0.1

Type RM Length L Ch R = 1,504,384,384,384
BEGIN DESCRIPTION:
UNT 128 in Running Cr Watershed 2.0
END DESCRIPTION:
XS GIS Cut Line= 4
      2849722.23      6997690.26      2849826.39      6998267.49
      2850091.15      6998445.44      2850480.93      6998328.50
#Sta/Elev= 30
  4258.9  422.23  4385.7  421.57  4413.2  419.87  4426.3  417.45  4456.8  416.36
  4466.7  416.35  4471.8  419.15  4477.1  419.84  4519.7  421.35  4589.1  421.96
  4642.6  419.11  4792.1  407.42  4849.9  405.34  4864.9  403.43  4872.3  400.11
  4882.9  399.21  4883.4  398.41  4888.9  399.21  5095.9  400.11  5101.9  403.72
  5116.9  405.12  5288.2  413.16  5354.3  419.02  5359.5  418.10  5387.3  420.73
  5430.8  421.83  5458.7  424.90  5463.9  423.41  5497.0  423.80  5571.4  427.05
#Mann=4,-1,0
  4258.9    0.08       0  4519.7    0.05       0  4882.9   0.033       0
  4888.9    0.05       0
Bank Sta=4872.3,5095.9
Exp/Cntr=0.3,0.1

Type RM Length L Ch R = 1,120,0,0,0
BEGIN DESCRIPTION:
UNT 128 in Running Cr Watershed 1.0
END DESCRIPTION:
XS GIS Cut Line= 4
      2849596.36      6997659.84      2849635.42      6998601.69
      2849891.50      6998762.28      2850420.34      6998450.18
#Sta/Elev= 30
  3892.6  423.65  3947.8  424.07  3967.8  421.95  3981.7  421.73  4007.9  417.96
  4027.9  416.48  4155.1  409.84  4188.0  406.27  4217.4  406.63  4222.4  407.92
  4268.1  407.14  4328.1  409.82  4351.1  412.48  4378.2  413.56  4449.2  413.38
  4488.3  410.69  4547.2  403.00  4580.6  399.45  4585.4  399.21  4585.9  398.41
  4590.9  398.41  4591.4  399.21  5339.6  399.45  5357.4  401.05  5363.2  402.84
  5394.5  404.88  5511.6  415.47  5582.8  423.13  5634.5  424.50  5751.6  424.26
#Mann=7,-1,0
  3892.6    0.05       0  4155.1    0.08       0  4351.1     0.1       0
  4449.2    0.15       0  4547.2    0.05       0  4585.4   0.033       0
  4591.4    0.05       0
Bank Sta=4580.6,5339.6
Exp/Cntr=0.3,0.1

Chan Stop Cuts=-1