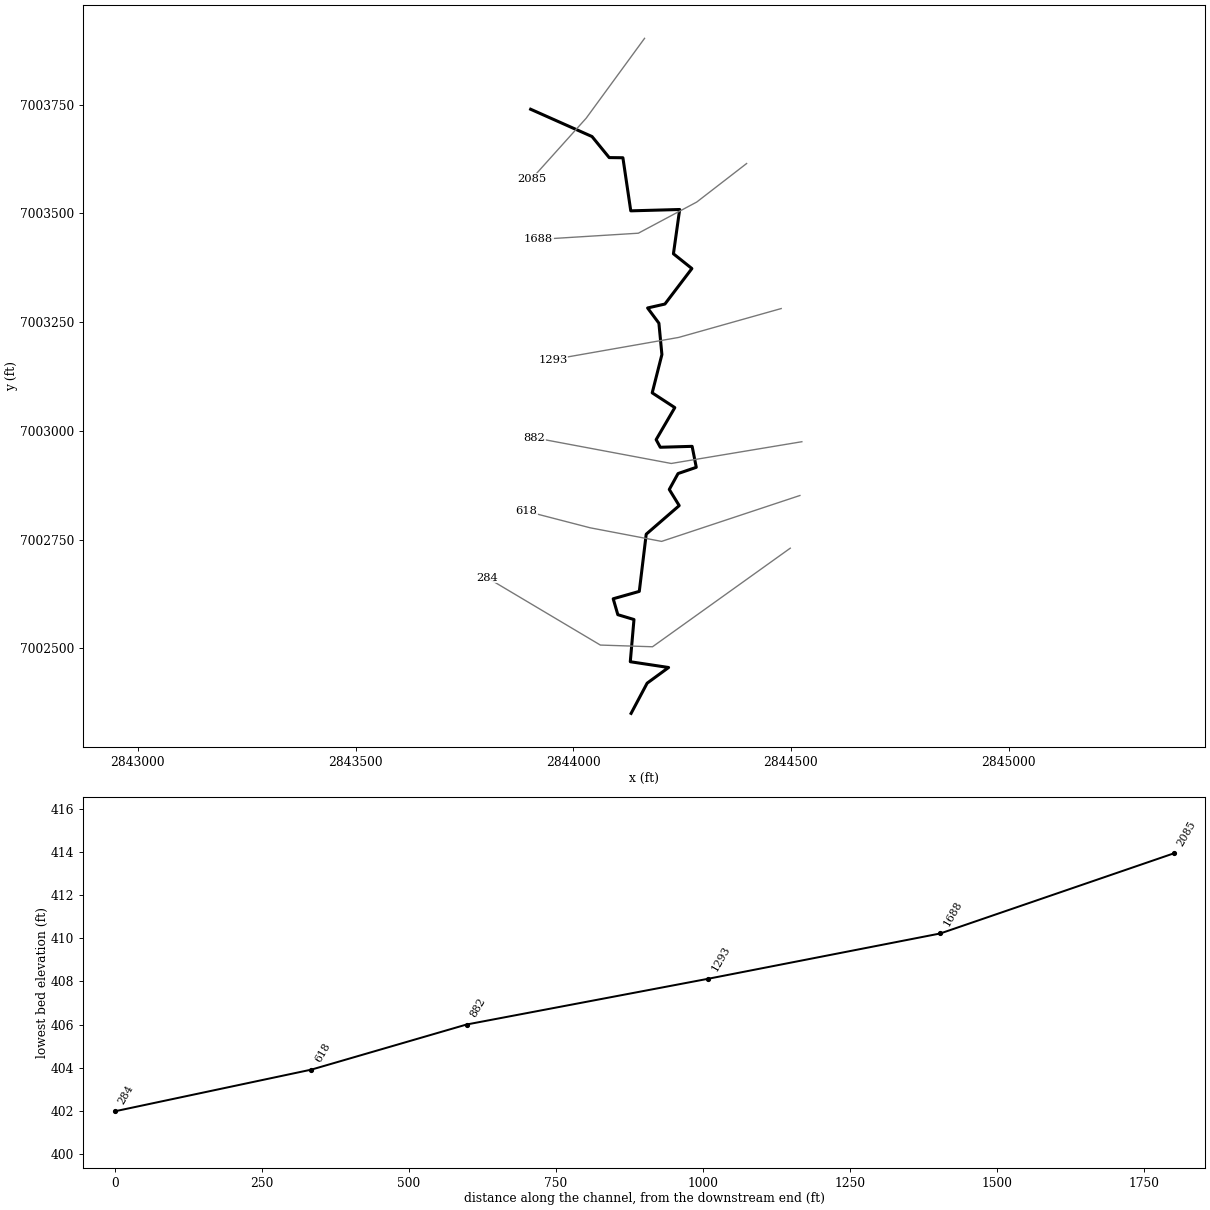
--- UNT 129 in Running Cr Watershed.prj (project) ---

Proj Title=UNT 129 in Running Cr Watershed Base Level Engineering
Current Plan=p01
Default Exp/Contr=0.3,0.1
English Units
Geom File=g01
Flow File=f01
Plan File=p01
BEGIN DESCRIPTION:
UNT 129 in Running Cr Watershed
END DESCRIPTION:

--- UNT 129 in Running Cr Watershed.p01 (plan) ---

Plan Title=Multiple Run
Short Identifier=Multiple
Geom File=g01
Flow File=f01
Subcritical Flow
K Sum by GR= 0
Std Step Tol= 0.01
Critical Tol= 0.01
Num of Std Step Trials= 20
Max Error Tol= 0.3
Flow Tol Ratio= 0.001
Split Flow NTrial= 30
Split Flow Tol= 0.02
Split Flow Ratio= 0.02
Log Output Level= 0
Friction Slope Method= 1
Unsteady Friction Slope Method= 2
Unsteady Bridges Friction Slope Method= 1
Parabolic Critical Depth
Global Vel Dist=  1 , 1 , 1
Global Log Level= 0
CheckData=True
Encroach Param= -1, 0, 0, 0
BEGIN DESCRIPTION:
Multiple Run
END DESCRIPTION:

--- UNT 129 in Running Cr Watershed.f01 (steady flow) ---

Flow Title=Multiple
Number of Profiles=7
Profile Names=10-year,25-year,50-year,1pct_min,100-year,1pct_plu,500-year
River Rch & RM= UNT 129 in Runni,Reach-1,2085
     169     208     237     135     270     538     348
Boundary for River Rch & Prof#=UNT 129 in Runni,Reach-1,1
Up Type=0
Dn Type=3
Dn Slope=0.005
Boundary for River Rch & Prof#=UNT 129 in Runni,Reach-1,2
Up Type=0
Dn Type=3
Dn Slope=0.005
Boundary for River Rch & Prof#=UNT 129 in Runni,Reach-1,3
Up Type=0
Dn Type=3
Dn Slope=0.005
Boundary for River Rch & Prof#=UNT 129 in Runni,Reach-1,4
Up Type=0
Dn Type=3
Dn Slope=0.005
Boundary for River Rch & Prof#=UNT 129 in Runni,Reach-1,5
Up Type=0
Dn Type=3
Dn Slope=0.005
Boundary for River Rch & Prof#=UNT 129 in Runni,Reach-1,6
Up Type=0
Dn Type=3
Dn Slope=0.005
Boundary for River Rch & Prof#=UNT 129 in Runni,Reach-1,7
Up Type=0
Dn Type=3
Dn Slope=0.005

--- UNT 129 in Running Cr Watershed.g01 (geometry) ---

Geom Title=Existing Conditions

River Reach=UNT 129 in Runni,Reach-1
Reach XY= 30
      2843902.08      7003739.13      2844043.05      7003676.39
      2844082.48      7003628.03      2844113.96      7003627.65
      2844132.03      7003505.64      2844244.36      7003508.71
      2844230.05      7003406.94      2844272.45      7003373.02
      2844210.44      7003291.40      2844170.69      7003282.39
      2844196.66      7003247.41      2844203.55      7003175.32
      2844181.29      7003087.34      2844233.23      7003053.41
      2844190.30      7002979.74      2844199.84      7002962.25
      2844272.98      7002964.37      2844282.52      7002916.14
      2844240.65      7002901.83      2844220.51      7002865.25
      2844243.30      7002828.15      2844167.51      7002762.43
      2844151.61      7002630.98      2844091.71      7002614.02
      2844102.31      7002577.45      2844139.41      7002566.32
      2844130.93      7002469.32      2844218.92      7002456.07
      2844169.63      7002420.03      2844132.80      7002350.62

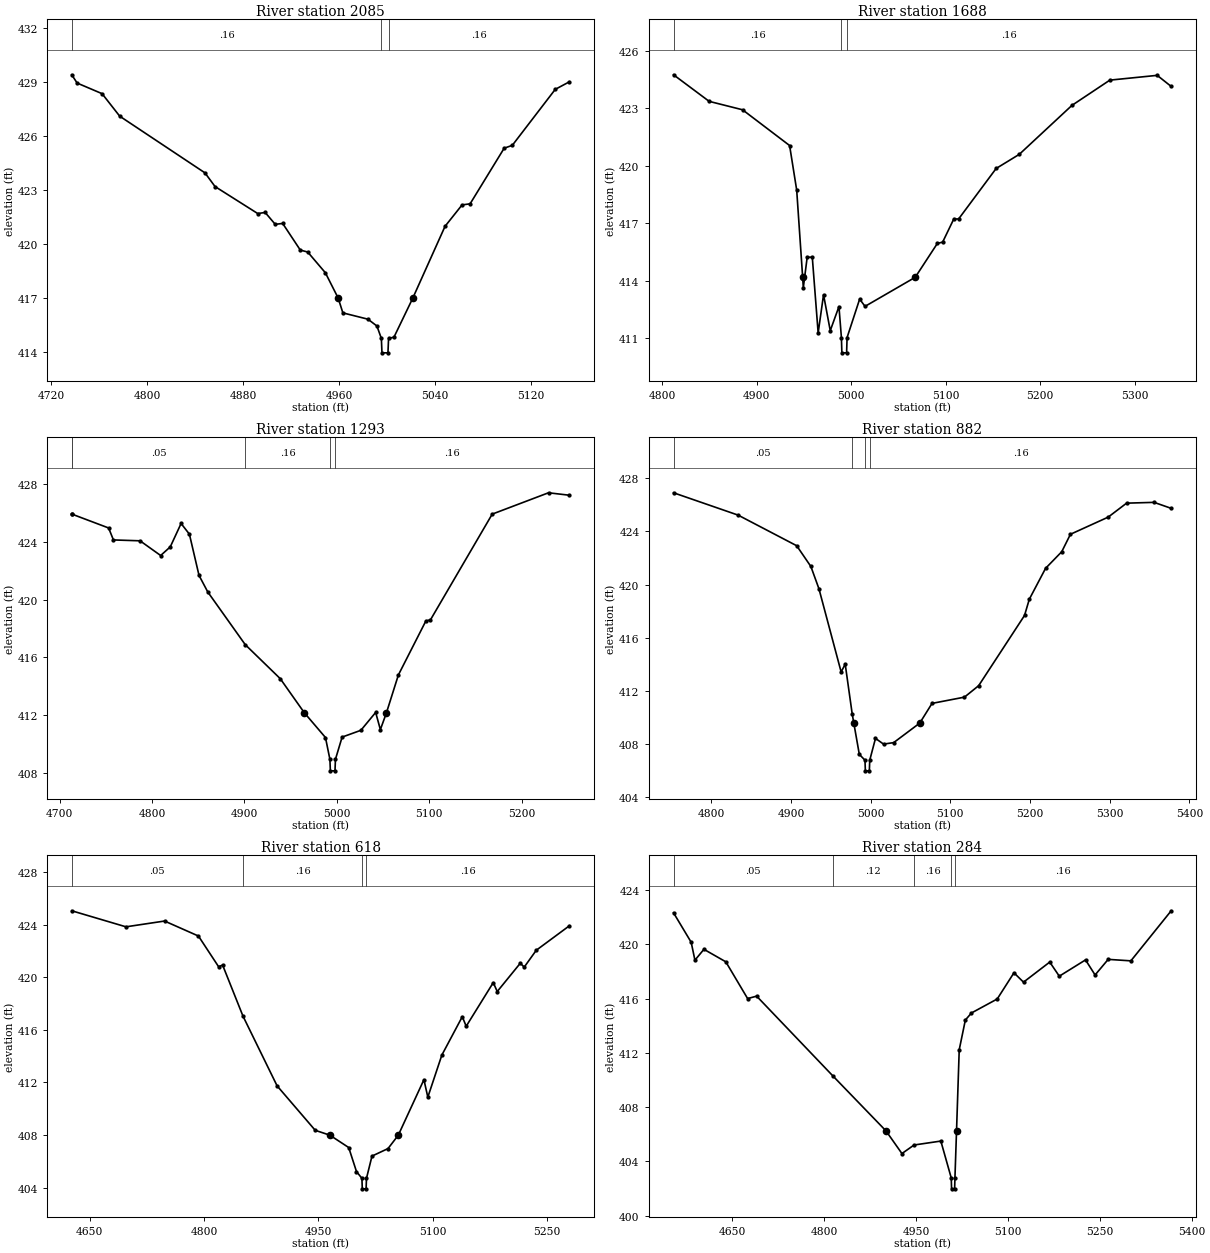
Type RM Length L Ch R = 1,2085,397,397,397
BEGIN DESCRIPTION:
UNT 129 in Running Cr Watershed 4.0
END DESCRIPTION:
XS GIS Cut Line= 3
      2844163.73      7003902.12      2844029.64      7003718.56
      2843904.23      7003578.93
#Sta/Elev= 30
  4737.2  429.38  4741.7  428.92  4762.5  428.33  4777.2  427.08  4848.3  423.93
  4856.7  423.17  4892.3  421.67  4898.5  421.73  4906.9  421.07  4913.1  421.12
  4927.8  419.64  4934.0  419.53  4948.7  418.38  4959.4  416.97  4963.3  416.15
  4984.2  415.80  4991.7  415.42  4995.4  414.73  4995.9  413.93  5000.9  413.93
  5001.4  414.73  5005.9  414.80  5021.6  416.97  5048.5  420.96  5062.7  422.15
  5069.4  422.21  5097.8  425.30  5104.6  425.46  5140.4  428.57  5152.2  428.99
#Mann=3,-1,0
  4737.2    0.16       0  4995.4    0.07       0  5001.4    0.16       0
Bank Sta=4959.4,5021.6
Exp/Cntr=0.3,0.1

Type RM Length L Ch R = 1,1688,395,395,395
BEGIN DESCRIPTION:
Mapping XS f7e9bfe9
END DESCRIPTION:
XS GIS Cut Line= 4
      2844398.12      7003614.38      2844283.55      7003525.85
      2844149.43      7003454.24      2843920.20      7003439.99
#Sta/Elev= 30
  4812.2  424.76  4849.9  423.37  4885.2  422.93  4935.0  421.06  4942.5  418.73
  4948.8  414.17  4949.5  413.63  4953.6  415.22  4959.0  415.22  4965.2  411.26
  4970.9  413.26  4978.0  411.38  4987.2  412.64  4989.8  411.02  4990.3  410.22
  4995.3  410.22  4995.8  411.02  5009.1  413.03  5014.8  412.65  5067.9  414.17
  5091.3  415.94  5096.9  416.01  5108.7  417.22  5113.8  417.22  5153.5  419.86
  5178.0  420.60  5233.7  423.16  5273.8  424.48  5323.9  424.73  5338.7  424.15
#Mann=3,-1,0
  4812.2    0.16       0  4989.8    0.07       0  4995.8    0.16       0
Bank Sta=4948.8,5067.9
Exp/Cntr=0.3,0.1

Type RM Length L Ch R = 1,1293,411,411,411
BEGIN DESCRIPTION:
UNT 129 in Running Cr Watershed 3.0
END DESCRIPTION:
XS GIS Cut Line= 3
      2844477.57      7003281.06      2844241.88      7003214.65
      2843952.78      7003163.86
#Sta/Elev= 30
  4713.1  425.94  4713.3  425.92  4753.0  424.96  4758.2  424.13  4787.0  424.07
  4809.3  423.05  4819.7  423.65  4831.4  425.27  4840.4  424.53  4850.8  421.67
  4860.3  420.52  4900.8  416.87  4938.7  414.51  4964.7  412.15  4987.6  410.43
  4992.4  408.92  4992.9  408.12  4997.9  408.12  4998.4  408.92  5005.6  410.46
  5025.9  410.93  5041.9  412.17  5047.0  410.98  5053.6  412.15  5066.5  414.77
  5096.2  418.51  5101.2  418.59  5168.0  425.92  5228.9  427.40  5251.5  427.23
#Mann=5,-1,0
  4713.1    0.16       0  4713.3    0.05       0  4900.8    0.16       0
  4992.4    0.07       0  4998.4    0.16       0
Bank Sta=4964.7,5053.6
Exp/Cntr=0.3,0.1

Type RM Length L Ch R = 1,882,264,264,264
BEGIN DESCRIPTION:
UNT 129 in Running Cr Watershed 2.0
END DESCRIPTION:
XS GIS Cut Line= 3
      2844525.03      7002975.00      2844225.00      7002925.00
      2843909.97      7002984.16
#Sta/Elev= 30
  4752.5  426.90  4833.6  425.22  4907.1  422.92  4924.9  421.36  4935.0  419.69
  4962.9  413.43  4968.0  414.02  4976.8  410.27  4978.8  409.59  4985.7  407.24
  4992.8  406.80  4993.3  406.00  4998.3  406.00  4998.8  406.80  5006.0  408.44
  5016.1  408.01  5028.8  408.12  5061.6  409.59  5077.0  411.07  5117.7  411.54
  5135.5  412.40  5193.1  417.68  5199.1  418.90  5219.5  421.22  5239.8  422.47
  5250.7  423.78  5298.1  425.07  5321.2  426.12  5355.7  426.18  5377.2  425.73
#Mann=4,-1,0
  4752.5    0.05       0  4976.8    0.16       0  4992.8    0.07       0
  4998.8    0.16       0
Bank Sta=4978.8,5061.6
Exp/Cntr=0.3,0.1

Type RM Length L Ch R = 1,618,334,334,334
BEGIN DESCRIPTION:
Mapping XS 8362536c
END DESCRIPTION:
XS GIS Cut Line= 4
      2844520.54      7002851.38      2844202.82      7002745.90
      2844038.75      7002777.15      2843892.94      7002814.91
#Sta/Elev= 30
  4626.7  425.05  4697.8  423.83  4748.4  424.27  4792.8  423.13  4819.2  420.80
  4824.5  420.92  4851.2  417.04  4895.9  411.74  4945.9  408.36  4965.1  407.99
  4989.8  407.05  5000.0  405.22  5007.1  404.71  5007.6  403.91  5012.6  403.91
  5013.1  404.71  5020.3  406.40  5041.3  406.97  5054.8  407.99  5088.4  412.21
  5093.5  410.88  5111.9  414.08  5138.7  417.00  5143.8  416.27  5179.3  419.59
  5184.5  418.91  5214.7  421.06  5219.9  420.77  5235.7  422.05  5279.1  423.91
#Mann=4,-1,0
  4626.7    0.05       0  4851.2    0.16       0  5007.1    0.07       0
  5013.1    0.16       0
Bank Sta=4965.1,5054.8
Exp/Cntr=0.3,0.1

Type RM Length L Ch R = 1,284,0,0,0
BEGIN DESCRIPTION:
UNT 129 in Running Cr Watershed 1.0
END DESCRIPTION:
XS GIS Cut Line= 4
      2844498.41      7002730.30      2844181.98      7002503.72
      2844062.19      7002507.62      2843801.75      7002662.59
#Sta/Elev= 30
  4554.4  422.32  4583.2  420.15  4589.3  418.83  4604.0  419.63  4639.7  418.71
  4675.3  416.00  4690.0  416.18  4814.0  410.32  4901.1  406.25  4927.1  404.58
  4946.9  405.21  4990.6  405.50  5007.6  402.78  5008.1  401.98  5013.1  401.98
  5013.6  402.78  5016.2  406.25  5020.6  412.23  5030.6  414.42  5040.6  414.94
  5082.6  415.97  5109.9  417.90  5125.5  417.21  5168.3  418.69  5183.9  417.65
  5226.7  418.85  5242.3  417.74  5263.7  418.89  5300.7  418.78  5366.5  422.47
#Mann=5,-1,0
  4554.4    0.05       0  4814.0    0.12       0  4946.9    0.16       0
  5007.6    0.07       0  5013.6    0.16       0
Bank Sta=4901.1,5016.2
Exp/Cntr=0.3,0.1

Chan Stop Cuts=-1