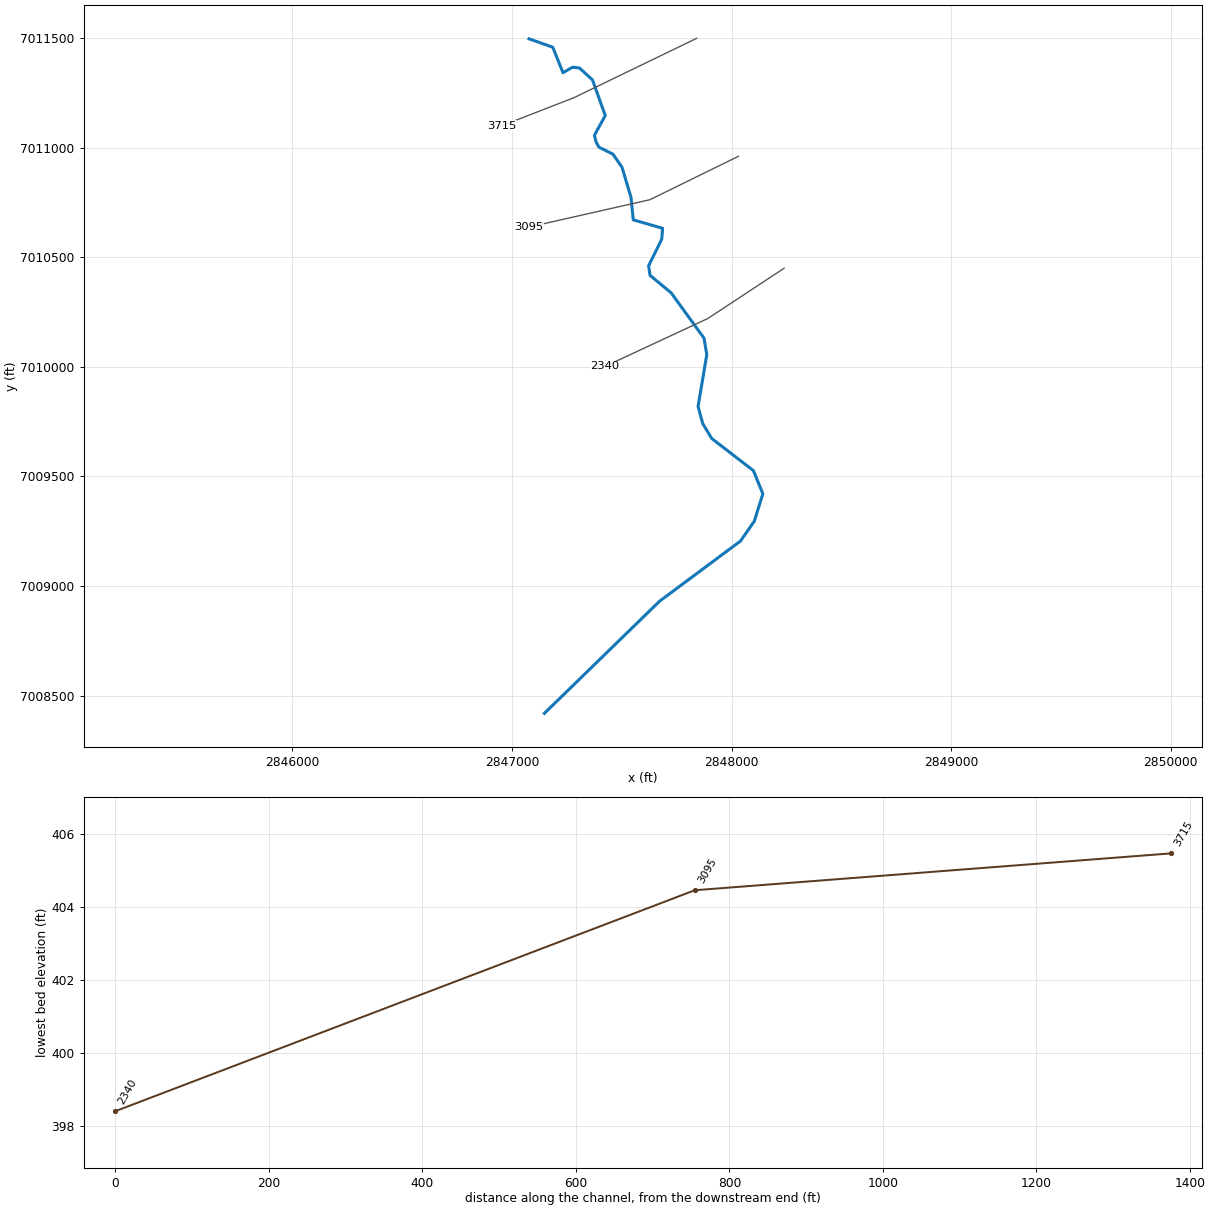
--- UNT 130 in Running Cr Watershed.prj (project) ---

Proj Title=UNT 130 in Running Cr Watershed Base Level Engineering
Current Plan=p01
Default Exp/Contr=0.3,0.1
English Units
Geom File=g01
Flow File=f01
Plan File=p01
BEGIN DESCRIPTION:
UNT 130 in Running Cr Watershed
END DESCRIPTION:

--- UNT 130 in Running Cr Watershed.p01 (plan) ---

Plan Title=Multiple Run
Short Identifier=Multiple
Geom File=g01
Flow File=f01
Subcritical Flow
K Sum by GR= 0
Std Step Tol= 0.01
Critical Tol= 0.01
Num of Std Step Trials= 20
Max Error Tol= 0.3
Flow Tol Ratio= 0.001
Split Flow NTrial= 30
Split Flow Tol= 0.02
Split Flow Ratio= 0.02
Log Output Level= 0
Friction Slope Method= 1
Unsteady Friction Slope Method= 2
Unsteady Bridges Friction Slope Method= 1
Parabolic Critical Depth
Global Vel Dist=  1 , 1 , 1
Global Log Level= 0
CheckData=True
Encroach Param= -1, 0, 0, 0
BEGIN DESCRIPTION:
Multiple Run
END DESCRIPTION:

--- UNT 130 in Running Cr Watershed.f01 (steady flow) ---

Flow Title=Multiple
Number of Profiles=7
Profile Names=10-year,25-year,50-year,1pct_min,100-year,1pct_plu,500-year
River Rch & RM= UNT 130 in Runni,Reach-1,3715
     248     311     358     205     410     818     537
Boundary for River Rch & Prof#=UNT 130 in Runni,Reach-1,1
Up Type=0
Dn Type=3
Dn Slope=0.005
Boundary for River Rch & Prof#=UNT 130 in Runni,Reach-1,2
Up Type=0
Dn Type=3
Dn Slope=0.005
Boundary for River Rch & Prof#=UNT 130 in Runni,Reach-1,3
Up Type=0
Dn Type=3
Dn Slope=0.005
Boundary for River Rch & Prof#=UNT 130 in Runni,Reach-1,4
Up Type=0
Dn Type=3
Dn Slope=0.005
Boundary for River Rch & Prof#=UNT 130 in Runni,Reach-1,5
Up Type=0
Dn Type=3
Dn Slope=0.005
Boundary for River Rch & Prof#=UNT 130 in Runni,Reach-1,6
Up Type=0
Dn Type=3
Dn Slope=0.005
Boundary for River Rch & Prof#=UNT 130 in Runni,Reach-1,7
Up Type=0
Dn Type=3
Dn Slope=0.005

--- UNT 130 in Running Cr Watershed.g01 (geometry) ---

Geom Title=Existing Conditions

River Reach=UNT 130 in Runni,Reach-1
Reach XY= 30
      2847077.91      7011496.17      2847186.21      7011457.49
      2847232.63      7011341.45      2847276.14      7011366.59
      2847308.06      7011362.73      2847367.04      7011308.57
      2847425.07      7011146.11      2847375.75      7011056.18
      2847383.48      7011025.24      2847396.05      7011002.03
      2847459.88      7010970.12      2847501.46      7010910.16
      2847542.07      7010773.81      2847552.71      7010670.34
      2847686.16      7010631.66      2847682.29      7010582.35
      2847622.34      7010460.50      2847629.10      7010416.99
      2847724.84      7010337.69      2847874.73      7010130.75
      2847887.30      7010055.32      2847847.65      7009819.37
      2847868.92      7009741.04      2847909.54      7009673.35
      2848099.50      7009526.62      2848142.61      7009420.80
      2848103.42      7009295.39      2848040.71      7009205.25
      2847672.30      7008930.90      2847147.75      7008419.27

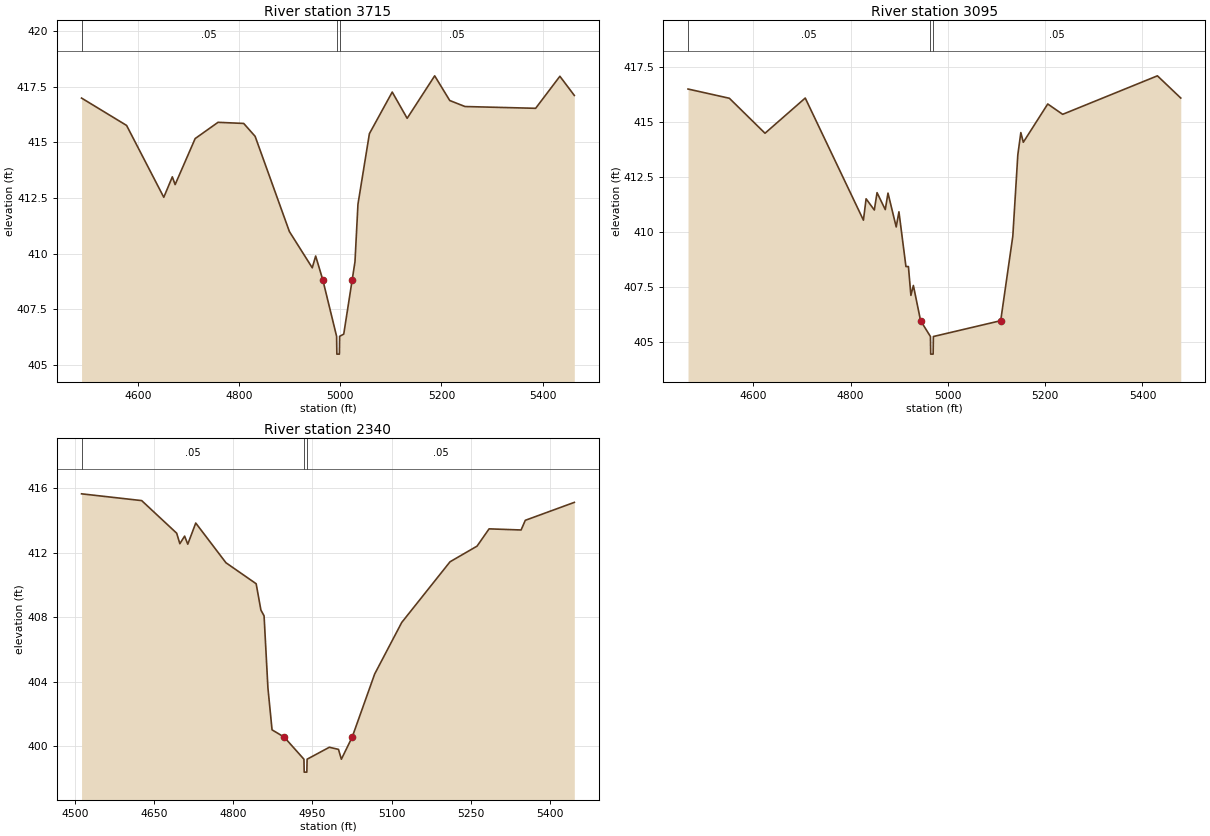
Type RM Length L Ch R = 1,3715,620,620,620
BEGIN DESCRIPTION:
UNT 130 in Running Cr Watershed 3.0
END DESCRIPTION:
XS GIS Cut Line= 3
      2847841.28      7011498.27      2847282.28      7011227.45
      2846953.77      7011099.50
#Sta/Elev= 30
  4488.9  416.99  4577.9  415.76  4651.4  412.53  4668.3  413.45  4673.8  413.10
  4713.4  415.17  4758.6  415.90  4809.3  415.85  4831.9  415.27  4899.6  410.99
  4944.8  409.36  4951.5  409.89  4965.6  408.82  4992.9  406.28  4993.4  405.48
  4998.4  405.48  4998.9  406.28  5007.0  406.38  5023.7  408.82  5029.2  409.63
  5035.1  412.22  5057.7  415.39  5102.8  417.26  5132.3  416.08  5186.7  417.99
  5216.5  416.88  5246.6  416.61  5386.2  416.53  5434.1  417.97  5462.6  417.11
#Mann=3,-1,0
  4488.9    0.05       0  4992.9    0.03       0  4998.9    0.05       0
Bank Sta=4965.6,5023.7
Exp/Cntr=0.3,0.1

Type RM Length L Ch R = 1,3095,755,755,755
BEGIN DESCRIPTION:
Mapping XS df21742e
END DESCRIPTION:
XS GIS Cut Line= 3
      2848031.30      7010960.15      2847628.52      7010762.24
      2847078.22      7010637.64
#Sta/Elev= 30
  4465.8  416.52  4550.8  416.10  4624.1  414.51  4706.8  416.11  4826.4  410.56
  4831.9  411.53  4848.8  411.02  4854.4  411.81  4871.3  411.04  4876.9  411.79
  4893.8  410.25  4899.4  410.94  4913.8  408.45  4918.9  408.45  4924.0  407.14
  4929.1  407.59  4943.9  405.99  4964.2  405.27  4964.7  404.47  4969.7  404.47
  4970.2  405.27  5108.6  405.99  5133.5  409.83  5143.8  413.53  5150.0  414.54
  5155.1  414.10  5205.3  415.84  5236.0  415.37  5430.8  417.12  5478.8  416.11
#Mann=3,-1,0
  4465.8    0.05       0  4964.2    0.03       0  4970.2    0.05       0
Bank Sta=4943.9,5108.6
Exp/Cntr=0.3,0.1

Type RM Length L Ch R = 1,2340,0,0,0
BEGIN DESCRIPTION:
Mapping XS 530fd78a
END DESCRIPTION:
XS GIS Cut Line= 3
      2848239.63      7010449.74      2847892.41      7010220.57
      2847423.66      7010001.82
#Sta/Elev= 30
  4512.7  415.65  4626.6  415.23  4692.9  413.21  4698.9  412.56  4707.9  413.03
  4713.9  412.53  4729.0  413.84  4786.2  411.38  4843.4  410.08  4852.4  408.45
  4858.4  408.09  4865.7  403.63  4873.5  401.03  4896.5  400.58  4933.9  399.21
  4934.4  398.41  4939.4  398.41  4939.9  399.21  4982.0  399.95  4999.3  399.82
  5004.8  399.21  5025.3  400.58  5067.9  404.49  5119.1  407.68  5210.6  411.44
  5261.8  412.41  5284.6  413.48  5345.2  413.41  5353.2  414.01  5446.0  415.12
#Mann=3,-1,0
  4512.7    0.05       0  4933.9    0.03       0  4939.9    0.05       0
Bank Sta=4896.5,5025.3
Exp/Cntr=0.3,0.1

Chan Stop Cuts=-1