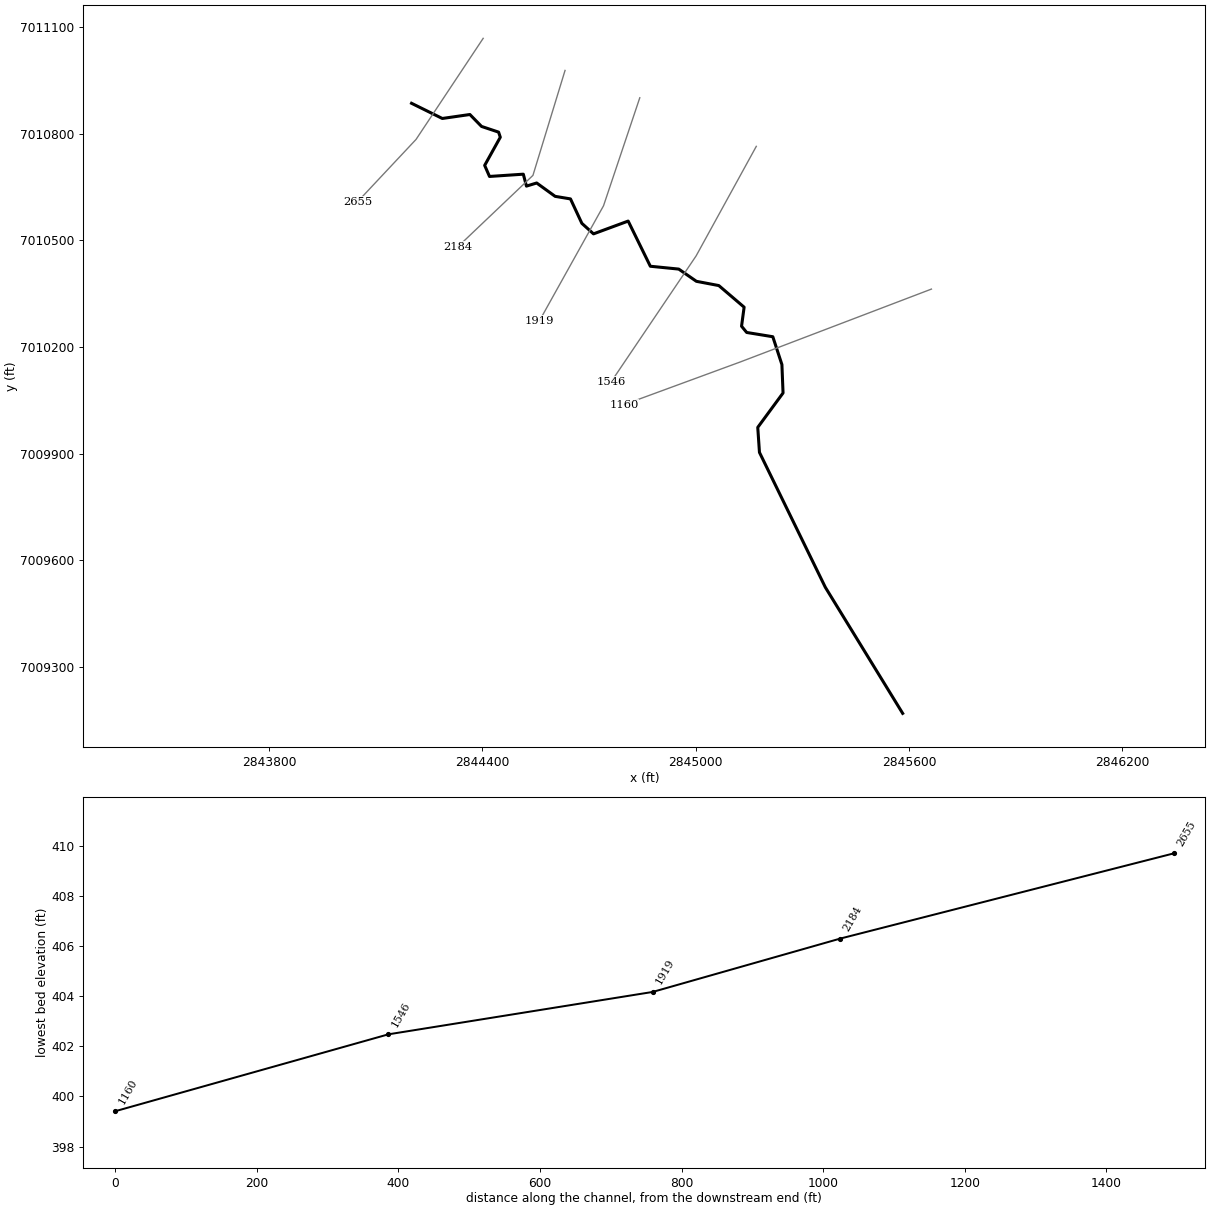
--- UNT 131 in Running Cr Watershed.prj (project) ---

Proj Title=UNT 131 in Running Cr Watershed Base Level Engineering
Current Plan=p01
Default Exp/Contr=0.3,0.1
English Units
Geom File=g01
Flow File=f01
Plan File=p01
BEGIN DESCRIPTION:
UNT 131 in Running Cr Watershed
END DESCRIPTION:

--- UNT 131 in Running Cr Watershed.p01 (plan) ---

Plan Title=Multiple Run
Short Identifier=Multiple
Geom File=g01
Flow File=f01
Subcritical Flow
K Sum by GR= 0
Std Step Tol= 0.01
Critical Tol= 0.01
Num of Std Step Trials= 20
Max Error Tol= 0.3
Flow Tol Ratio= 0.001
Split Flow NTrial= 30
Split Flow Tol= 0.02
Split Flow Ratio= 0.02
Log Output Level= 0
Friction Slope Method= 1
Unsteady Friction Slope Method= 2
Unsteady Bridges Friction Slope Method= 1
Parabolic Critical Depth
Global Vel Dist=  1 , 1 , 1
Global Log Level= 0
CheckData=True
Encroach Param= -1, 0, 0, 0
BEGIN DESCRIPTION:
Multiple Run
END DESCRIPTION:

--- UNT 131 in Running Cr Watershed.f01 (steady flow) ---

Flow Title=Multiple
Number of Profiles=7
Profile Names=10-year,25-year,50-year,1pct_min,100-year,1pct_plu,500-year
River Rch & RM= UNT 131 in Runni,Reach-1,2655
     164     201     228     129     258     515     329
Boundary for River Rch & Prof#=UNT 131 in Runni,Reach-1,1
Up Type=0
Dn Type=3
Dn Slope=0.005
Boundary for River Rch & Prof#=UNT 131 in Runni,Reach-1,2
Up Type=0
Dn Type=3
Dn Slope=0.005
Boundary for River Rch & Prof#=UNT 131 in Runni,Reach-1,3
Up Type=0
Dn Type=3
Dn Slope=0.005
Boundary for River Rch & Prof#=UNT 131 in Runni,Reach-1,4
Up Type=0
Dn Type=3
Dn Slope=0.005
Boundary for River Rch & Prof#=UNT 131 in Runni,Reach-1,5
Up Type=0
Dn Type=3
Dn Slope=0.005
Boundary for River Rch & Prof#=UNT 131 in Runni,Reach-1,6
Up Type=0
Dn Type=3
Dn Slope=0.005
Boundary for River Rch & Prof#=UNT 131 in Runni,Reach-1,7
Up Type=0
Dn Type=3
Dn Slope=0.005

--- UNT 131 in Running Cr Watershed.g01 (geometry) ---

Geom Title=Existing Conditions

River Reach=UNT 131 in Runni,Reach-1
Reach XY= 30
      2844200.59      7010885.71      2844287.14      7010842.99
      2844364.71      7010854.16      2844397.49      7010820.59
      2844445.45      7010804.60      2844450.24      7010790.21
      2844406.28      7010711.08      2844419.87      7010679.91
      2844514.99      7010686.30      2844523.78      7010652.73
      2844552.55      7010661.52      2844604.51      7010623.95
      2844647.67      7010616.76      2844679.65      7010548.02
      2844712.42      7010518.44      2844809.94      7010554.41
      2844872.28      7010427.32      2844952.22      7010419.33
      2845001.78      7010384.96      2845064.92      7010372.97
      2845136.06      7010312.22      2845128.87      7010258.66
      2845143.26      7010241.08      2845216.79      7010229.09
      2845242.37      7010150.75      2845245.57      7010070.82
      2845174.43      7009974.10      2845179.23      7009903.76
      2845364.42      7009524.43      2845582.06      7009169.63

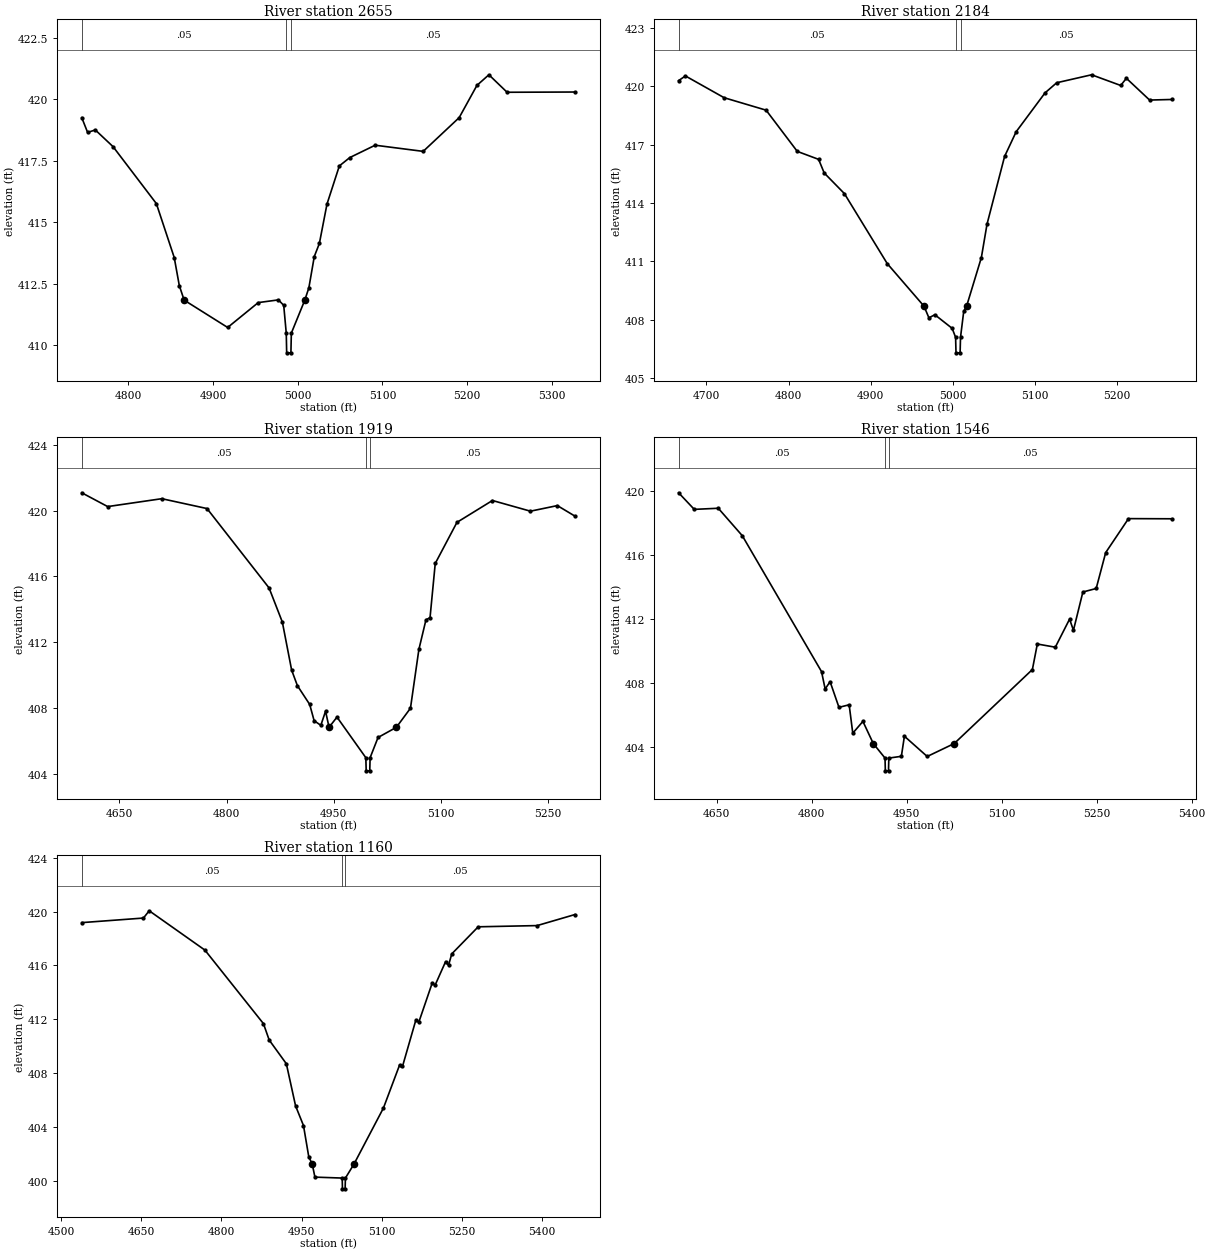
Type RM Length L Ch R = 1,2655,471,471,471
BEGIN DESCRIPTION:
UNT 131 in Running Cr Watershed 6.0
END DESCRIPTION:
XS GIS Cut Line= 3
      2844402.10      7011068.42      2844213.27      7010784.09
      2844048.31      7010608.28
#Sta/Elev= 30
  4744.9  419.25  4751.8  418.65  4760.9  418.75  4781.9  418.07  4833.0  415.76
  4854.1  413.57  4860.1  412.43  4865.8  411.84  4917.2  410.73  4953.3  411.74
  4977.1  411.85  4983.4  411.63  4986.4  410.50  4986.9  409.70  4991.9  409.70
  4992.4  410.50  5008.3  411.84  5013.1  412.34  5019.5  413.61  5025.5  414.14
  5034.5  415.74  5049.1  417.29  5061.5  417.63  5091.4  418.13  5148.1  417.88
  5190.6  419.25  5211.6  420.56  5225.7  420.99  5247.2  420.28  5327.3  420.29
#Mann=3,-1,0
  4744.9    0.05       0  4986.4    0.03       0  4992.4    0.05       0
Bank Sta=4865.8,5008.3
Exp/Cntr=0.3,0.1

Type RM Length L Ch R = 1,2184,265,265,265
BEGIN DESCRIPTION:
Mapping XS 87039112
END DESCRIPTION:
XS GIS Cut Line= 3
      2844632.35      7010978.12      2844542.07      7010682.95
      2844330.28      7010481.59
#Sta/Elev= 30
  4666.1  420.30  4674.4  420.54  4721.6  419.42  4772.7  418.78  4810.7  416.66
  4836.7  416.25  4843.5  415.55  4868.1  414.49  4920.3  410.89  4965.1  408.70
  4971.1  408.10  4978.3  408.26  4999.4  407.56  5003.6  407.10  5004.1  406.30
  5009.1  406.30  5009.6  407.10  5013.5  408.43  5017.0  408.70  5035.0  411.20
  5041.9  412.92  5063.3  416.40  5077.4  417.67  5112.6  419.67  5126.8  420.19
  5169.3  420.60  5204.8  420.05  5211.7  420.42  5240.0  419.30  5267.0  419.33
#Mann=3,-1,0
  4666.1    0.05       0  5003.6    0.03       0  5009.6    0.05       0
Bank Sta=4965.1,5017
Exp/Cntr=0.3,0.1

Type RM Length L Ch R = 1,1919,373,373,373
BEGIN DESCRIPTION:
UNT 131 in Running Cr Watershed 5.0
END DESCRIPTION:
XS GIS Cut Line= 3
      2844842.61      7010901.29      2844740.61      7010597.46
      2844560.51      7010274.13
#Sta/Elev= 30
  4597.2  421.09  4633.5  420.25  4709.3  420.73  4772.6  420.13  4859.5  415.30
  4878.1  413.22  4891.1  410.30  4899.2  409.35  4916.4  408.21  4922.6  407.22
  4932.0  406.94  4938.6  407.80  4943.5  406.82  4954.6  407.44  4995.0  404.97
  4995.5  404.17  5000.5  404.17  5001.0  404.97  5012.1  406.20  5037.8  406.82
  5057.5  407.98  5069.3  411.56  5079.2  413.36  5084.9  413.49  5092.2  416.79
  5122.6  419.29  5172.3  420.62  5225.5  419.97  5263.2  420.31  5287.8  419.67
#Mann=3,-1,0
  4597.2    0.05       0  4995.0    0.03       0  5001.0    0.05       0
Bank Sta=4943.5,5037.8
Exp/Cntr=0.3,0.1

Type RM Length L Ch R = 1,1546,386,386,386
BEGIN DESCRIPTION:
UNT 131 in Running Cr Watershed 4.0
END DESCRIPTION:
XS GIS Cut Line= 3
      2845170.31      7010764.58      2845001.03      7010456.40
      2844762.29      7010102.63
#Sta/Elev= 30
  4590.1  419.91  4614.8  418.87  4652.7  418.94  4690.6  417.22  4815.7  408.70
  4821.4  407.61  4829.2  408.07  4843.2  406.46  4859.3  406.62  4865.0  404.84
  4881.0  405.58  4897.4  404.19  4915.9  403.28  4916.4  402.48  4921.4  402.48
  4921.9  403.28  4941.7  403.39  4946.5  404.65  4982.5  403.38  5025.1  404.19
  5148.5  408.83  5156.3  410.43  5184.7  410.23  5207.2  411.99  5213.3  411.29
  5228.2  413.69  5249.2  413.91  5264.2  416.16  5300.2  418.29  5368.5  418.28
#Mann=3,-1,0
  4590.1    0.05       0  4915.9    0.03       0  4921.9    0.05       0
Bank Sta=4897.4,5025.1
Exp/Cntr=0.3,0.1

Type RM Length L Ch R = 1,1160,0,0,0
BEGIN DESCRIPTION:
UNT 131 in Running Cr Watershed 3.0
END DESCRIPTION:
XS GIS Cut Line= 3
      2845662.94      7010363.09      2845126.62      7010158.60
      2844798.53      7010038.11
#Sta/Elev= 30
  4538.5  419.18  4654.0  419.52  4664.8  420.06  4769.1  417.14  4878.7  411.68
  4889.5  410.46  4921.6  408.70  4938.9  405.57  4953.7  404.11  4963.6  401.79
  4970.1  401.25  4975.1  400.28  5026.2  400.21  5026.7  399.41  5031.7  399.41
  5032.2  400.21  5048.3  401.25  5103.4  405.41  5133.8  408.62  5139.1  408.50
  5164.3  411.97  5169.6  411.78  5194.8  414.70  5200.1  414.53  5219.9  416.29
  5225.3  416.01  5231.4  416.86  5280.9  418.87  5391.2  418.96  5462.0  419.78
#Mann=3,-1,0
  4538.5    0.05       0  5026.2    0.03       0  5032.2    0.05       0
Bank Sta=4970.1,5048.3
Exp/Cntr=0.3,0.1

Chan Stop Cuts=-1