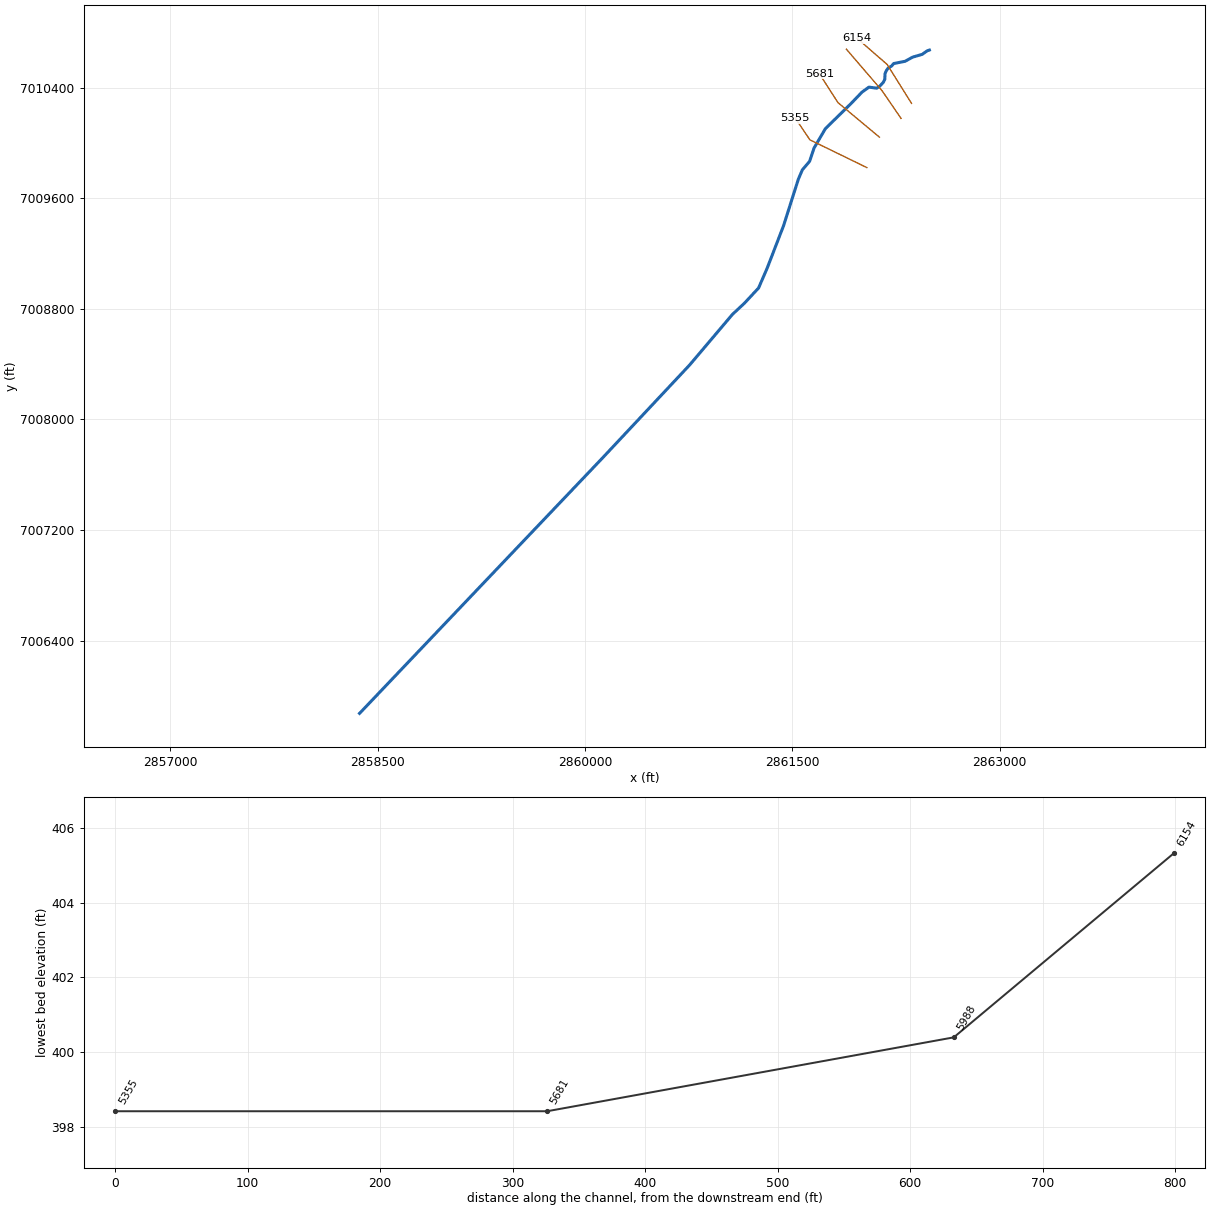
--- UNT 132 in Running Cr Watershed.prj (project) ---

Proj Title=UNT 132 in Running Cr Watershed Base Level Engineering
Current Plan=p01
Default Exp/Contr=0.3,0.1
English Units
Geom File=g01
Flow File=f01
Plan File=p01
BEGIN DESCRIPTION:
UNT 132 in Running Cr Watershed
END DESCRIPTION:

--- UNT 132 in Running Cr Watershed.p01 (plan) ---

Plan Title=Multiple Run
Short Identifier=Multiple
Geom File=g01
Flow File=f01
Subcritical Flow
K Sum by GR= 0
Std Step Tol= 0.01
Critical Tol= 0.01
Num of Std Step Trials= 20
Max Error Tol= 0.3
Flow Tol Ratio= 0.001
Split Flow NTrial= 30
Split Flow Tol= 0.02
Split Flow Ratio= 0.02
Log Output Level= 0
Friction Slope Method= 1
Unsteady Friction Slope Method= 2
Unsteady Bridges Friction Slope Method= 1
Parabolic Critical Depth
Global Vel Dist=  1 , 1 , 1
Global Log Level= 0
CheckData=True
Encroach Param= -1, 0, 0, 0
BEGIN DESCRIPTION:
Multiple Run
END DESCRIPTION:

--- UNT 132 in Running Cr Watershed.f01 (steady flow) ---

Flow Title=Multiple
Number of Profiles=7
Profile Names=10-year,25-year,50-year,1pct_min,100-year,1pct_plu,500-year
River Rch & RM= UNT 132 in Runni,Reach-1,6154
     243     307     356     206     410     818     545
Boundary for River Rch & Prof#=UNT 132 in Runni,Reach-1,1
Up Type=0
Dn Type=3
Dn Slope=0.005
Boundary for River Rch & Prof#=UNT 132 in Runni,Reach-1,2
Up Type=0
Dn Type=3
Dn Slope=0.005
Boundary for River Rch & Prof#=UNT 132 in Runni,Reach-1,3
Up Type=0
Dn Type=3
Dn Slope=0.005
Boundary for River Rch & Prof#=UNT 132 in Runni,Reach-1,4
Up Type=0
Dn Type=3
Dn Slope=0.005
Boundary for River Rch & Prof#=UNT 132 in Runni,Reach-1,5
Up Type=0
Dn Type=3
Dn Slope=0.005
Boundary for River Rch & Prof#=UNT 132 in Runni,Reach-1,6
Up Type=0
Dn Type=3
Dn Slope=0.005
Boundary for River Rch & Prof#=UNT 132 in Runni,Reach-1,7
Up Type=0
Dn Type=3
Dn Slope=0.005

--- UNT 132 in Running Cr Watershed.g01 (geometry) ---

Geom Title=Existing Conditions

River Reach=UNT 132 in Runni,Reach-1
Reach XY= 30
      2862492.20      7010671.95      2862475.01      7010665.70
      2862441.16      7010641.22      2862370.36      7010620.36
      2862316.68      7010590.70      2862234.11      7010574.41
      2862219.29      7010557.01      2862194.17      7010541.55
      2862181.28      7010524.16      2862170.98      7010500.33
      2862169.69      7010460.39      2862158.74      7010438.49
      2862132.97      7010410.79      2862111.71      7010395.97
      2862055.03      7010403.70      2862004.78      7010367.63
      2861922.97      7010282.59      2861740.02      7010103.51
      2861658.21      7009963.73      2861625.36      7009866.46
      2861573.18      7009805.26      2861544.19      7009737.62
      2861437.63      7009402.16      2861318.97      7009094.80
      2861256.72      7008950.85      2861153.61      7008839.96
      2861068.02      7008760.20      2860756.76      7008392.53
      2860128.29      7007721.89      2858370.01      7005873.33

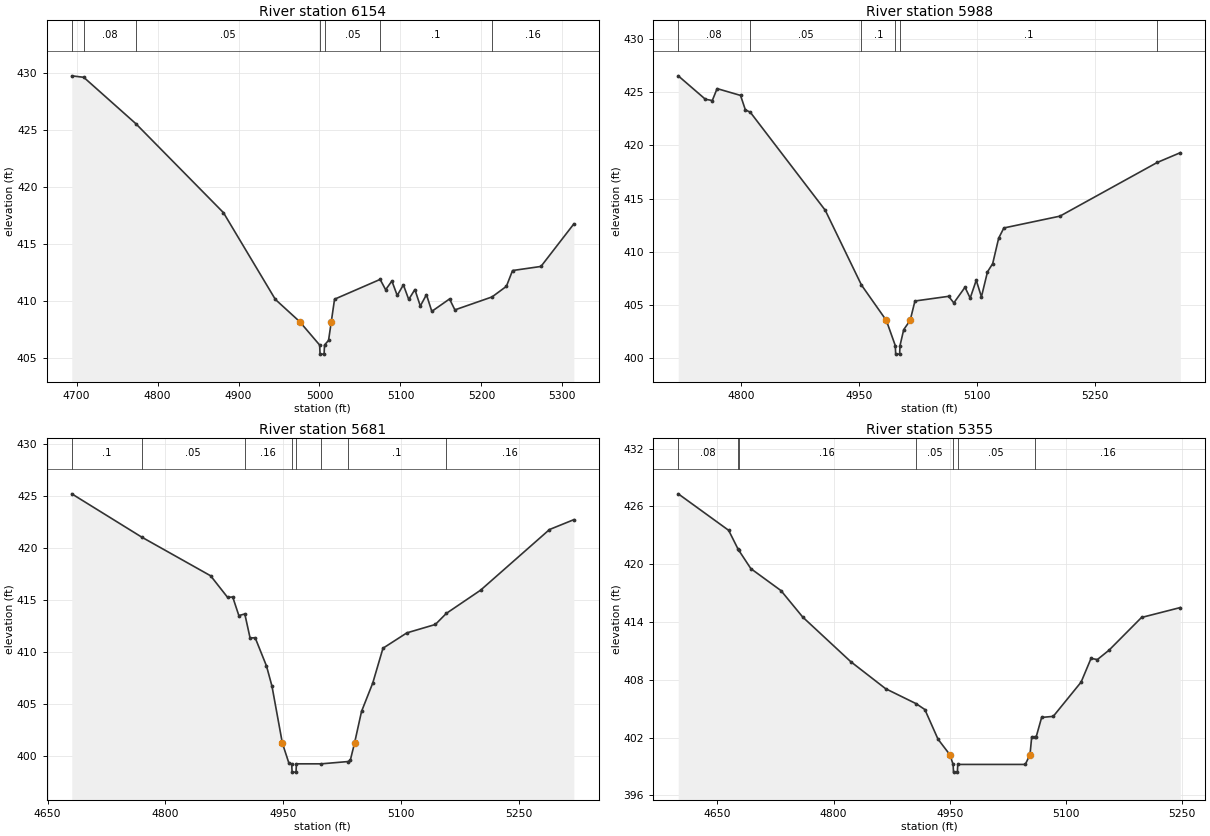
Type RM Length L Ch R = 1,6154,166,166,166
BEGIN DESCRIPTION:
UNT 132 in Running Cr Watershed 7.0
END DESCRIPTION:
XS GIS Cut Line= 3
      2862362.85      7010286.19      2862187.05      7010567.26
      2861969.48      7010756.68
#Sta/Elev= 30
  4694.1  429.79  4708.9  429.66  4773.1  425.59  4881.4  417.76  4945.5  410.13
  4975.5  408.18  5000.2  406.12  5000.7  405.32  5005.7  405.32  5006.2  406.12
  5011.2  406.53  5014.6  408.18  5018.6  410.15  5074.9  411.89  5081.7  410.98
  5089.4  411.75  5096.0  410.48  5103.6  411.41  5110.2  410.13  5117.8  411.00
  5124.5  409.55  5132.1  410.55  5138.7  409.08  5160.6  410.17  5167.2  409.21
  5213.1  410.35  5230.8  411.28  5238.4  412.67  5273.5  413.03  5314.1  416.77
#Mann=7,-1,0
  4694.1    0.05       0  4708.9    0.08       0  4773.1    0.05       0
  5000.2    0.03       0  5006.2    0.05       0  5074.9     0.1       0
  5213.1    0.16       0
Bank Sta=4975.5,5014.6
Exp/Cntr=0.3,0.1

Type RM Length L Ch R = 1,5988,307,307,307
BEGIN DESCRIPTION:
UNT 132 in Running Cr Watershed 6.0
END DESCRIPTION:
XS GIS Cut Line= 3
      2862286.87      7010177.72      2862150.15      7010377.37
      2861891.93      7010677.90
#Sta/Elev= 30
  4720.6  426.53  4755.1  424.33  4763.9  424.21  4770.0  425.33  4799.8  424.69
  4805.9  423.34  4812.2  423.11  4907.5  413.90  4953.5  406.88  4985.1  403.56
  4996.5  401.19  4997.0  400.39  5002.0  400.39  5002.5  401.19  5007.2  402.69
  5015.4  403.56  5021.5  405.38  5064.3  405.82  5070.9  405.20  5085.1  406.67
  5091.7  405.65  5099.4  407.33  5106.0  405.77  5113.7  408.12  5120.3  408.89
  5127.9  411.28  5134.5  412.24  5205.8  413.35  5329.4  418.39  5358.8  419.31
#Mann=6,-1,0
  4720.6    0.08       0  4812.2    0.05       0  4953.5     0.1       0
  4996.5    0.07       0  5002.5     0.1       0  5329.4    0.16       0
Bank Sta=4985.1,5015.4
Exp/Cntr=0.3,0.1

Type RM Length L Ch R = 1,5681,326,326,326
BEGIN DESCRIPTION:
UNT 132 in Running Cr Watershed 5.0
END DESCRIPTION:
XS GIS Cut Line= 3
      2862130.80      7010041.65      2861830.76      7010291.68
      2861696.30      7010500.83
#Sta/Elev= 30
  4680.8  425.23  4769.6  421.07  4857.6  417.33  4879.2  415.25  4885.7  415.29
  4893.5  413.50  4901.1  413.65  4907.8  411.34  4914.3  411.36  4928.7  408.64
  4935.7  406.69  4948.9  401.21  4957.3  399.26  4960.8  399.21  4961.3  398.41
  4966.3  398.41  4966.8  399.21  4998.6  399.21  5032.6  399.43  5035.4  399.55
  5040.8  401.21  5049.7  404.26  5064.0  407.00  5077.0  410.35  5107.4  411.83
  5143.7  412.64  5157.7  413.71  5201.2  415.94  5289.0  421.79  5320.0  422.74
#Mann=8,-1,0
  4680.8     0.1       0  4769.6    0.05       0  4901.1    0.16       0
  4960.8   0.033       0  4966.8    0.16       0  4998.6    0.05       0
  5032.6     0.1       0  5157.7    0.16       0
Bank Sta=4948.9,5040.8
Exp/Cntr=0.3,0.1

Type RM Length L Ch R = 1,5355,0,0,0
BEGIN DESCRIPTION:
UNT 132 in Running Cr Watershed 4.0
END DESCRIPTION:
XS GIS Cut Line= 3
      2862039.28      7009821.89      2861627.80      7010022.42
      2861521.45      7010180.66
#Sta/Elev= 30
  4599.3  427.31  4664.4  423.52  4676.5  421.58  4677.3  421.47  4693.1  419.54
  4732.0  417.26  4760.1  414.51  4822.1  409.88  4867.2  407.07  4906.5  405.52
  4917.8  404.91  4934.8  401.83  4950.0  400.23  4954.3  399.21  4954.8  398.41
  4959.8  398.41  4960.3  399.21  5047.5  399.21  5053.6  400.23  5055.8  402.08
  5059.6  402.08  5061.6  402.08  5068.6  404.09  5083.6  404.20  5119.6  407.76
  5132.4  410.22  5140.6  410.10  5155.6  411.07  5197.6  414.47  5247.7  415.50
#Mann=7,-1,0
  4599.3    0.08       0  4676.5     0.1       0  4677.3    0.16       0
  4906.5    0.05       0  4954.3   0.033       0  4960.3    0.05       0
  5059.6    0.16       0
Bank Sta=4950,5053.6
Exp/Cntr=0.3,0.1

Chan Stop Cuts=-1