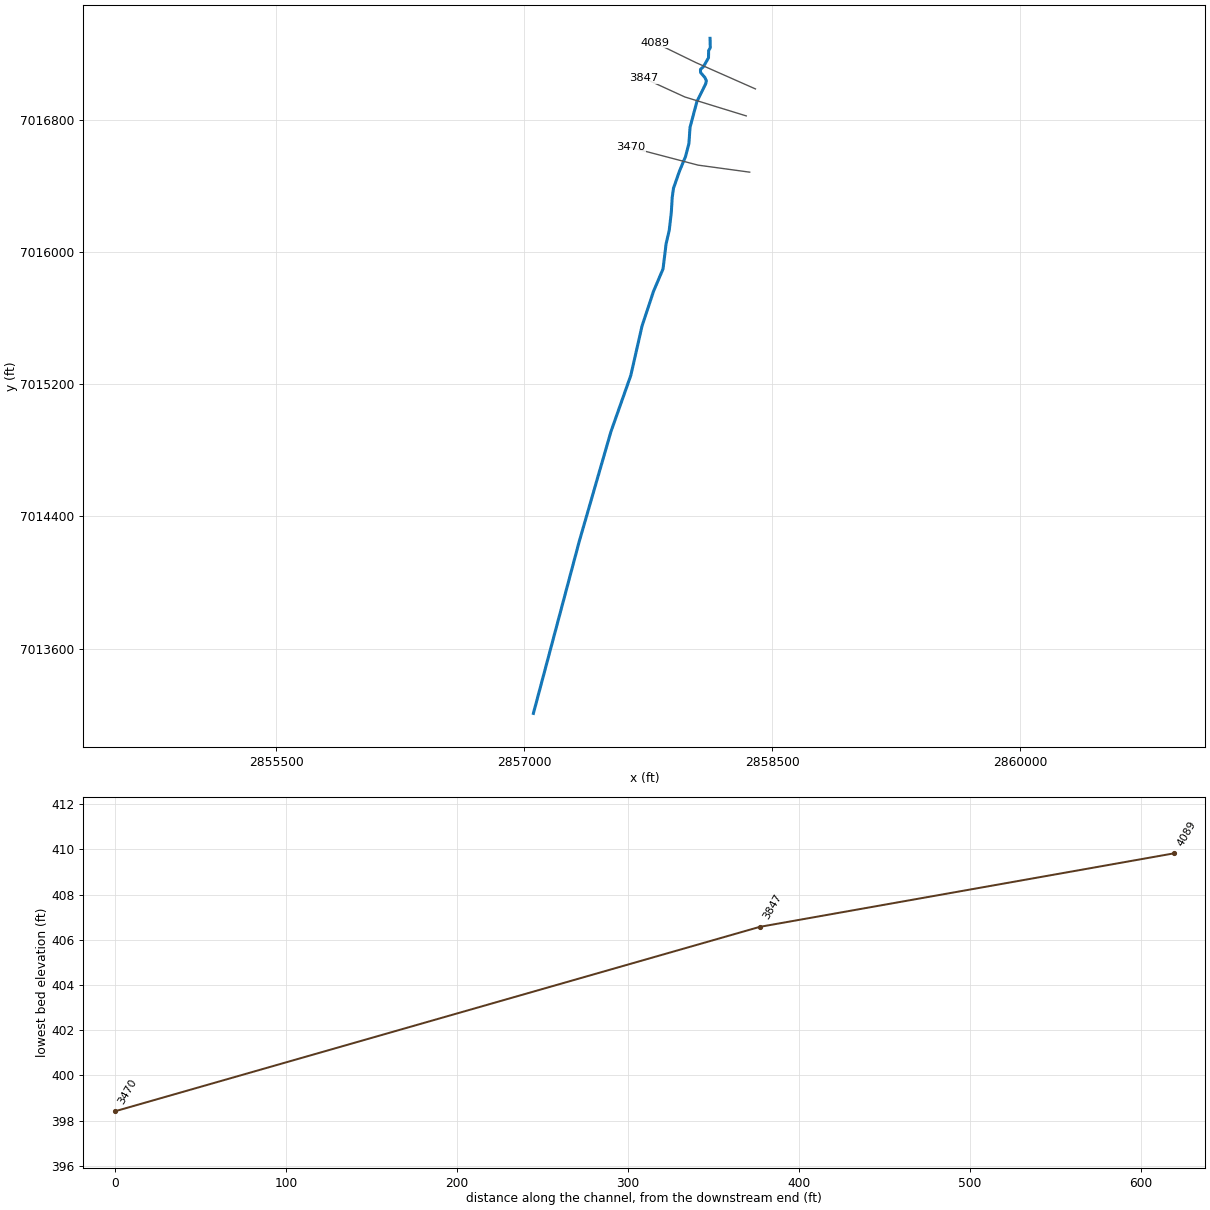
--- UNT 133 in Running Cr Watershed.prj (project) ---

Proj Title=UNT 133 in Running Cr Watershed Base Level Engineering
Current Plan=p01
Default Exp/Contr=0.3,0.1
English Units
Geom File=g01
Flow File=f01
Plan File=p01
BEGIN DESCRIPTION:
UNT 133 in Running Cr Watershed
END DESCRIPTION:

--- UNT 133 in Running Cr Watershed.p01 (plan) ---

Plan Title=Multiple Run
Short Identifier=Multiple
Geom File=g01
Flow File=f01
Subcritical Flow
K Sum by GR= 0
Std Step Tol= 0.01
Critical Tol= 0.01
Num of Std Step Trials= 20
Max Error Tol= 0.3
Flow Tol Ratio= 0.001
Split Flow NTrial= 30
Split Flow Tol= 0.02
Split Flow Ratio= 0.02
Log Output Level= 0
Friction Slope Method= 1
Unsteady Friction Slope Method= 2
Unsteady Bridges Friction Slope Method= 1
Parabolic Critical Depth
Global Vel Dist=  1 , 1 , 1
Global Log Level= 0
CheckData=True
Encroach Param= -1, 0, 0, 0
BEGIN DESCRIPTION:
Multiple Run
END DESCRIPTION:

--- UNT 133 in Running Cr Watershed.f01 (steady flow) ---

Flow Title=Multiple
Number of Profiles=7
Profile Names=10-year,25-year,50-year,1pct_min,100-year,1pct_plu,500-year
River Rch & RM= UNT 133 in Runni,Reach-1,4089
     168     207     236     135     268     536     346
Boundary for River Rch & Prof#=UNT 133 in Runni,Reach-1,1
Up Type=0
Dn Type=3
Dn Slope=0.005
Boundary for River Rch & Prof#=UNT 133 in Runni,Reach-1,2
Up Type=0
Dn Type=3
Dn Slope=0.005
Boundary for River Rch & Prof#=UNT 133 in Runni,Reach-1,3
Up Type=0
Dn Type=3
Dn Slope=0.005
Boundary for River Rch & Prof#=UNT 133 in Runni,Reach-1,4
Up Type=0
Dn Type=3
Dn Slope=0.005
Boundary for River Rch & Prof#=UNT 133 in Runni,Reach-1,5
Up Type=0
Dn Type=3
Dn Slope=0.005
Boundary for River Rch & Prof#=UNT 133 in Runni,Reach-1,6
Up Type=0
Dn Type=3
Dn Slope=0.005
Boundary for River Rch & Prof#=UNT 133 in Runni,Reach-1,7
Up Type=0
Dn Type=3
Dn Slope=0.005

--- UNT 133 in Running Cr Watershed.g01 (geometry) ---

Geom Title=Existing Conditions

River Reach=UNT 133 in Runni,Reach-1
Reach XY= 27
      2858124.08      7017291.88      2858125.38      7017235.02
      2858115.40      7017218.10      2858114.53      7017173.83
      2858083.28      7017119.57      2858065.92      7017103.95
      2858066.79      7017084.85      2858092.83      7017054.47
      2858101.94      7017035.37      2858097.17      7017015.41
      2858044.65      7016909.94      2858002.99      7016753.69
      2857996.04      7016654.73      2857975.00      7016575.00
      2857939.27      7016489.27      2857902.95      7016385.56
      2857895.06      7016329.08      2857889.59      7016237.39
      2857876.87      7016129.38      2857858.24      7016049.75
      2857839.60      7015897.27      2857782.00      7015761.73
      2857712.53      7015551.65      2857644.77      7015253.47
      2857524.47      7014912.93      2857332.99      7014249.57
      2857055.48      7013208.90

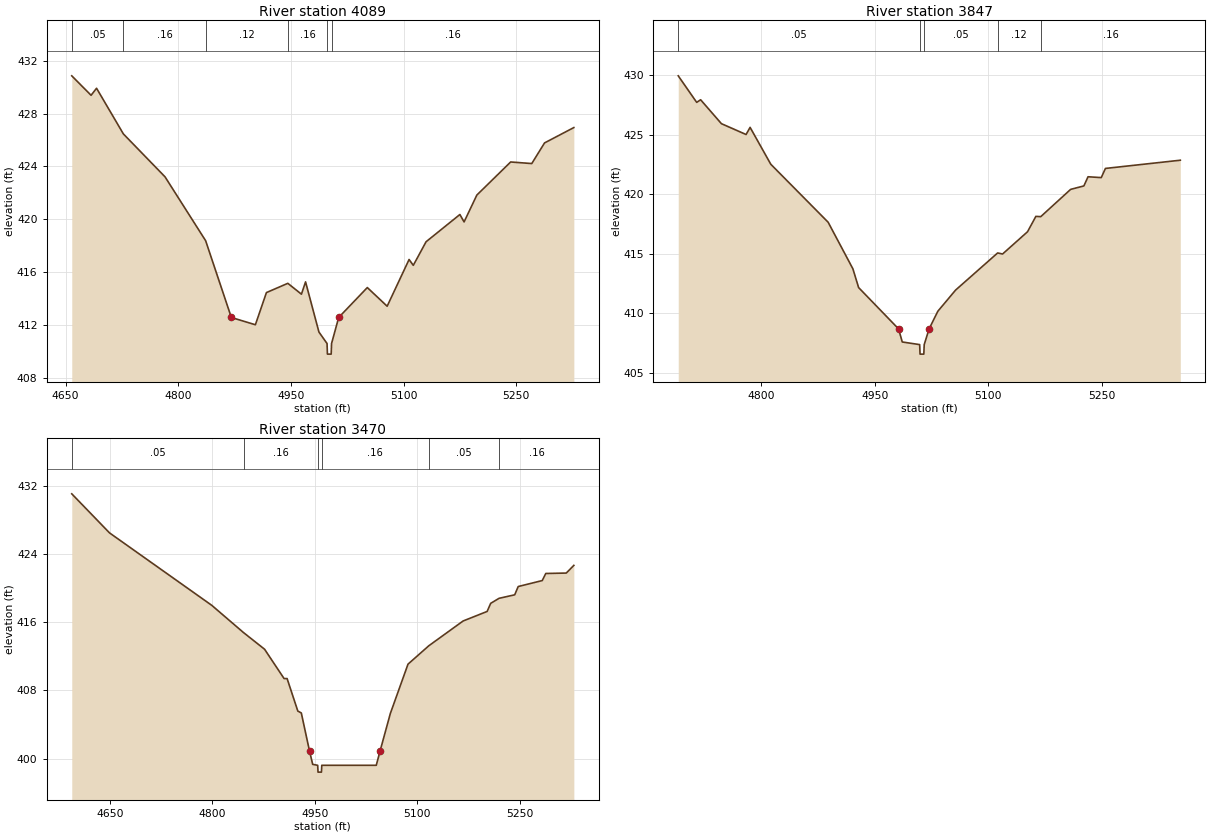
Type RM Length L Ch R = 1,4089,242,242,242
BEGIN DESCRIPTION:
UNT 133 in Running Cr Watershed 7.0
END DESCRIPTION:
XS GIS Cut Line= 3
      2858398.50      7016985.88      2858037.40      7017145.59
      2857791.63      7017265.48
#Sta/Elev= 30
  4658.2  430.85  4683.9  429.38  4691.2  429.91  4726.9  426.46  4782.3  423.22
  4836.4  418.39  4870.6  412.59  4902.6  412.04  4917.3  414.47  4945.8  415.17
  4963.9  414.35  4969.4  415.28  4987.2  411.49  4998.0  410.62  4998.5  409.82
  5003.5  409.82  5004.0  410.62  5013.5  412.59  5051.6  414.85  5078.0  413.44
  5107.2  416.97  5112.8  416.53  5129.8  418.31  5174.8  420.37  5180.4  419.81
  5197.4  421.84  5242.4  424.34  5270.5  424.22  5287.5  425.78  5326.5  426.94
#Mann=6,-1,0
  4658.2    0.05       0  4726.9    0.16       0  4836.4    0.12       0
  4945.8    0.16       0  4998.0    0.07       0  5004.0    0.16       0
Bank Sta=4870.6,5013.5
Exp/Cntr=0.3,0.1

Type RM Length L Ch R = 1,3847,377,377,377
BEGIN DESCRIPTION:
UNT 133 in Running Cr Watershed 6.0
END DESCRIPTION:
XS GIS Cut Line= 3
      2858342.93      7016822.68      2857971.43      7016937.26
      2857721.41      7017051.85
#Sta/Elev= 30
  4690.0  429.95  4714.4  427.72  4719.6  427.94  4747.1  425.93  4779.7  425.02
  4785.0  425.62  4812.4  422.52  4888.2  417.65  4920.9  413.74  4928.5  412.16
  4981.3  408.69  4986.2  407.59  5009.2  407.37  5009.7  406.57  5014.7  406.57
  5015.2  407.37  5021.7  408.69  5033.2  410.17  5056.7  411.95  5112.3  415.07
  5118.8  414.98  5151.8  416.85  5162.8  418.14  5169.3  418.12  5208.8  420.41
  5226.3  420.70  5231.8  421.47  5249.3  421.40  5254.8  422.17  5353.8  422.86
#Mann=5,-1,0
  4690.0    0.05       0  5009.2    0.03       0  5015.2    0.05       0
  5112.3    0.12       0  5169.3    0.16       0
Bank Sta=4981.3,5021.7
Exp/Cntr=0.3,0.1

Type RM Length L Ch R = 1,3470,0,0,0
BEGIN DESCRIPTION:
UNT 133 in Running Cr Watershed 5.0
END DESCRIPTION:
XS GIS Cut Line= 3
      2858363.79      7016482.40      2858051.29      7016525.00
      2857645.05      7016631.70
#Sta/Elev= 30
  4594.1  431.04  4649.4  426.46  4799.1  417.97  4845.7  414.77  4876.5  412.82
  4905.1  409.38  4909.5  409.38  4925.2  405.57  4930.3  405.35  4942.4  400.86
  4947.0  399.32  4954.3  399.21  4954.8  398.41  4959.8  398.41  4960.3  399.21
  5040.1  399.21  5045.6  400.86  5060.7  405.28  5086.6  411.07  5117.0  413.22
  5167.3  416.13  5202.5  417.25  5207.7  418.20  5220.0  418.79  5242.9  419.20
  5248.0  420.17  5283.2  420.87  5288.4  421.70  5318.4  421.75  5329.5  422.65
#Mann=6,-1,0
  4594.1    0.05       0  4845.7    0.16       0  4954.3    0.07       0
  4960.3    0.16       0  5117.0    0.05       0  5220.0    0.16       0
Bank Sta=4942.4,5045.6
Exp/Cntr=0.3,0.1

Chan Stop Cuts=-1