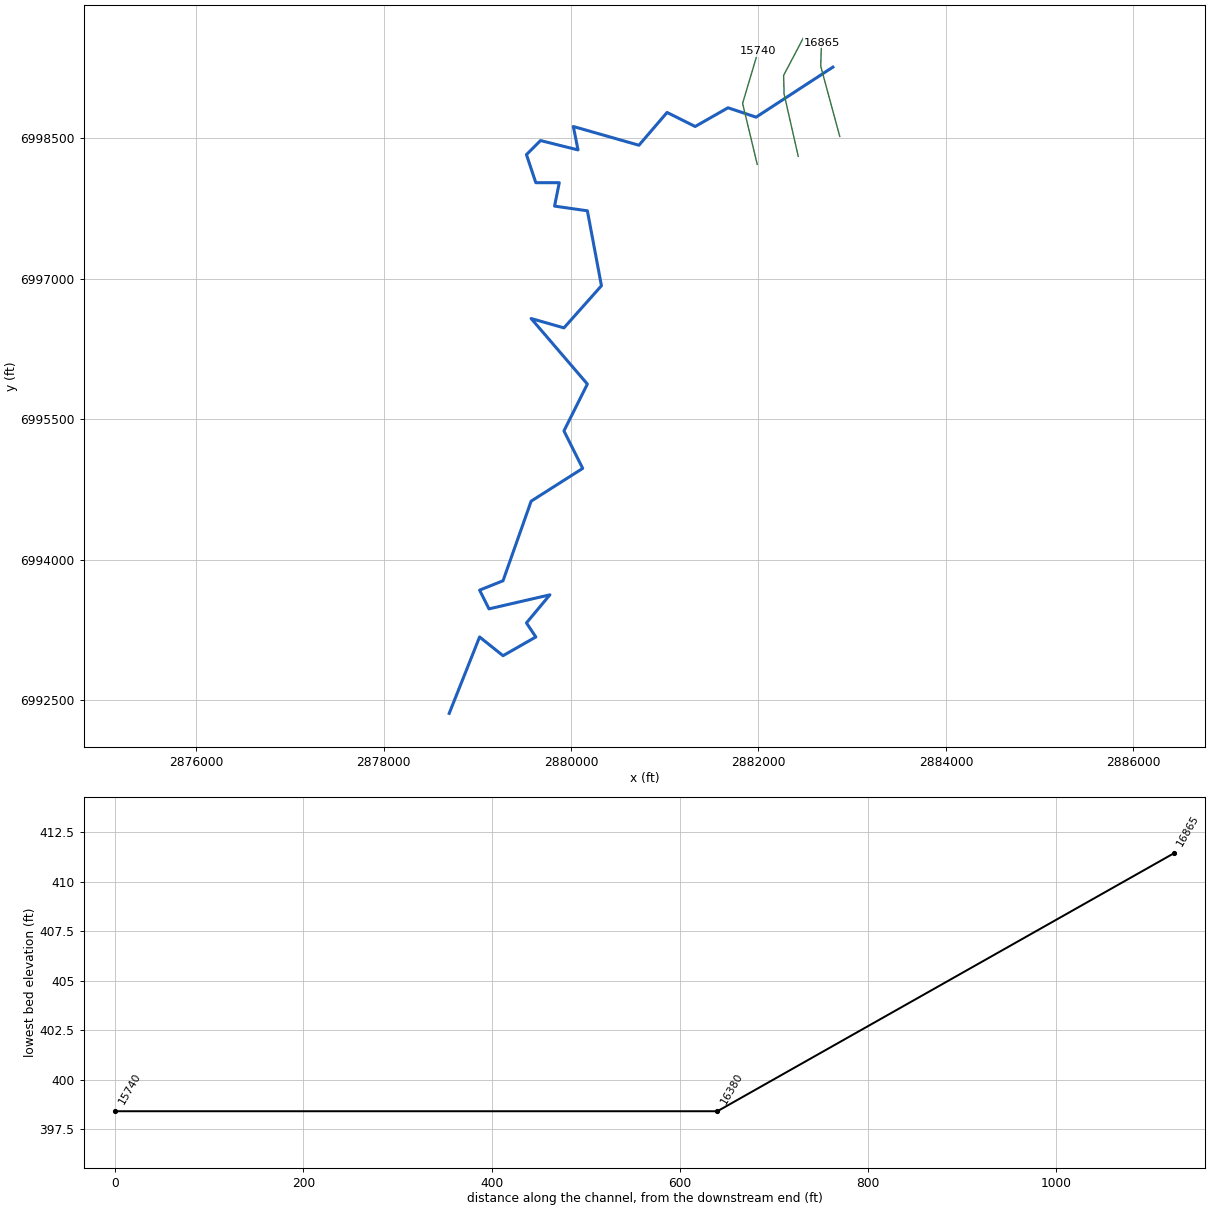
--- UNT 134 in Running Cr Watershed.prj (project) ---

Proj Title=UNT 134 in Running Cr Watershed Base Level Engineering
Current Plan=p01
Default Exp/Contr=0.3,0.1
English Units
Geom File=g01
Flow File=f01
Plan File=p01
BEGIN DESCRIPTION:
UNT 134 in Running Cr Watershed
END DESCRIPTION:

--- UNT 134 in Running Cr Watershed.p01 (plan) ---

Plan Title=Multiple Run
Short Identifier=Multiple
Geom File=g01
Flow File=f01
Subcritical Flow
K Sum by GR= 0
Std Step Tol= 0.01
Critical Tol= 0.01
Num of Std Step Trials= 20
Max Error Tol= 0.3
Flow Tol Ratio= 0.001
Split Flow NTrial= 30
Split Flow Tol= 0.02
Split Flow Ratio= 0.02
Log Output Level= 0
Friction Slope Method= 1
Unsteady Friction Slope Method= 2
Unsteady Bridges Friction Slope Method= 1
Parabolic Critical Depth
Global Vel Dist=  1 , 1 , 1
Global Log Level= 0
CheckData=True
Encroach Param= -1, 0, 0, 0
BEGIN DESCRIPTION:
Multiple Run
END DESCRIPTION:

--- UNT 134 in Running Cr Watershed.f01 (steady flow) ---

Flow Title=Multiple
Number of Profiles=7
Profile Names=10-year,25-year,50-year,1pct_min,100-year,1pct_plu,500-year
River Rch & RM= UNT 134 in Runni,Reach-1,16865
     327     417     486     282     562    1121     752
Boundary for River Rch & Prof#=UNT 134 in Runni,Reach-1,1
Up Type=0
Dn Type=3
Dn Slope=0.005
Boundary for River Rch & Prof#=UNT 134 in Runni,Reach-1,2
Up Type=0
Dn Type=3
Dn Slope=0.005
Boundary for River Rch & Prof#=UNT 134 in Runni,Reach-1,3
Up Type=0
Dn Type=3
Dn Slope=0.005
Boundary for River Rch & Prof#=UNT 134 in Runni,Reach-1,4
Up Type=0
Dn Type=3
Dn Slope=0.005
Boundary for River Rch & Prof#=UNT 134 in Runni,Reach-1,5
Up Type=0
Dn Type=3
Dn Slope=0.005
Boundary for River Rch & Prof#=UNT 134 in Runni,Reach-1,6
Up Type=0
Dn Type=3
Dn Slope=0.005
Boundary for River Rch & Prof#=UNT 134 in Runni,Reach-1,7
Up Type=0
Dn Type=3
Dn Slope=0.005

--- UNT 134 in Running Cr Watershed.g01 (geometry) ---

Geom Title=Existing Conditions

River Reach=UNT 134 in Runni,Reach-1
Reach XY= 30
      2882793.95      6999258.97      2881975.00      6998725.00
      2881675.00      6998825.00      2881325.00      6998625.00
      2881025.00      6998775.00      2880725.00      6998425.00
      2880025.00      6998625.00      2880075.00      6998375.00
      2879675.00      6998475.00      2879525.00      6998325.00
      2879625.00      6998025.00      2879875.00      6998025.00
      2879825.00      6997775.00      2880175.00      6997725.00
      2880325.00      6996925.00      2879925.00      6996475.00
      2879575.00      6996575.00      2880175.00      6995875.00
      2879925.00      6995375.00      2880125.00      6994975.00
      2879575.00      6994625.00      2879275.00      6993775.00
      2879025.00      6993675.00      2879125.00      6993475.00
      2879775.00      6993625.00      2879525.00      6993325.00
      2879625.00      6993175.00      2879275.00      6992975.00
      2879025.00      6993175.00      2878700.88      6992359.24

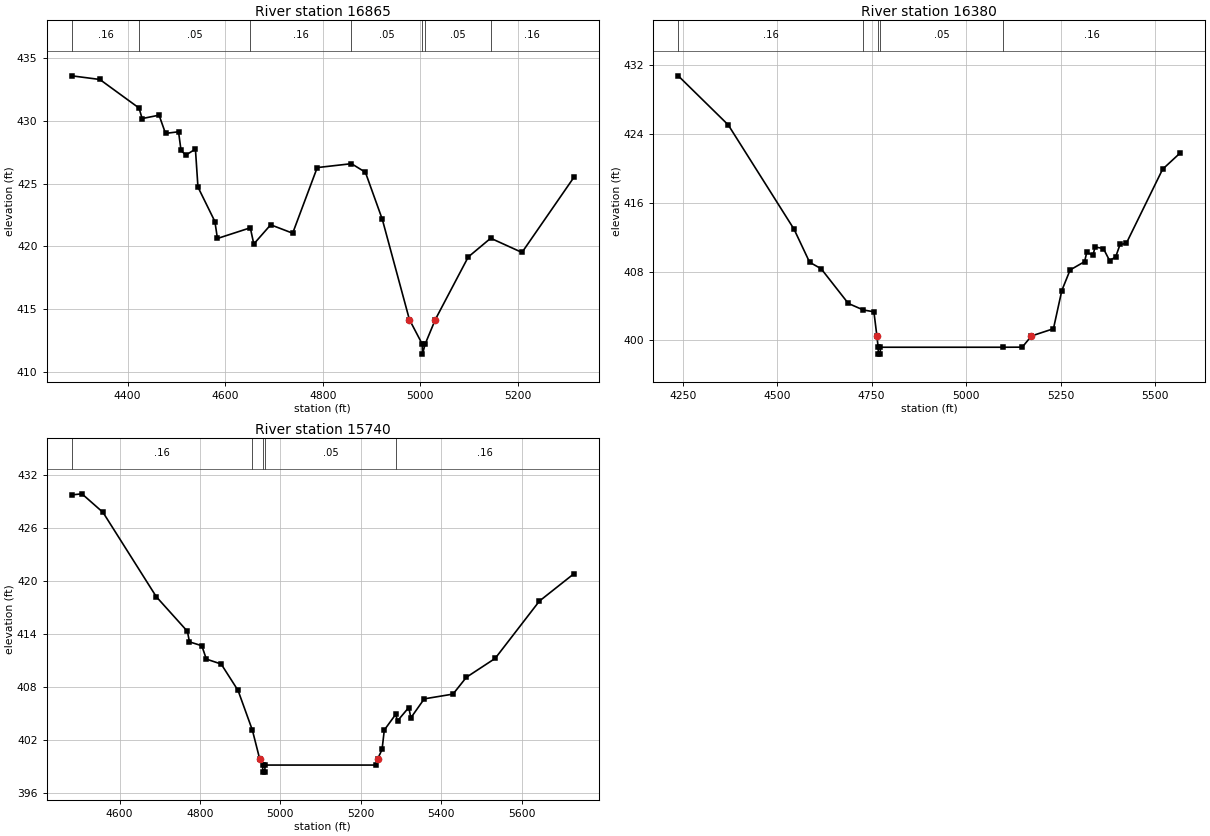
Type RM Length L Ch R = 1,16865,485,485,485
BEGIN DESCRIPTION:
UNT 134 in Running Cr Watershed 2.0
END DESCRIPTION:
XS GIS Cut Line= 3
      2882867.38      6998519.54      2882664.26      6999269.50
      2882673.10      6999521.26
#Sta/Elev= 30
  4285.7  433.57  4343.2  433.28  4423.5  431.01  4429.9  430.17  4464.6  430.44
  4477.8  428.99  4504.5  429.12  4509.6  427.64  4519.3  427.26  4539.1  427.74
  4544.3  424.72  4579.0  421.98  4584.2  420.63  4651.6  421.48  4658.7  420.19
  4693.3  421.72  4738.4  421.05  4788.7  426.27  4858.9  426.58  4887.4  425.90
  4922.1  422.15  4977.6  414.18  5003.9  412.23  5004.4  411.43  5009.9  412.23
  5030.7  414.18  5098.2  419.16  5144.2  420.65  5208.3  419.52  5314.6  425.49
#Mann=7,-1,0
  4285.7    0.16       0  4423.5    0.05       0  4651.6    0.16       0
  4858.9    0.05       0  5003.9   0.035       0  5009.9    0.05       0
  5144.2    0.16       0
Bank Sta=4977.6,5030.7
Exp/Cntr=0.3,0.1

Type RM Length L Ch R = 1,16380,640,640,640
BEGIN DESCRIPTION:
Mapping XS 53959cc1
END DESCRIPTION:
XS GIS Cut Line= 4
      2882424.68      6998305.94      2882273.63      6998972.63
      2882268.43      6999170.54      2882476.77      6999566.39
#Sta/Elev= 30
  4238.0  430.75  4370.3  425.05  4544.6  412.92  4585.7  409.09  4616.3  408.33
  4688.2  404.30  4727.9  403.54  4755.9  403.33  4763.8  400.52  4767.2  399.21
  4767.7  398.41  4772.7  398.41  4773.2  399.21  5098.4  399.21  5148.6  399.22
  5172.9  400.52  5231.1  401.36  5253.2  405.79  5275.2  408.19  5313.6  409.16
  5319.3  410.25  5335.7  409.90  5341.3  410.86  5363.3  410.68  5379.7  409.28
  5395.8  409.70  5407.4  411.16  5423.8  411.27  5520.1  419.90  5566.9  421.80
#Mann=5,-1,0
  4238.0    0.16       0  4727.9    0.05       0  4767.2   0.033       0
  4773.2    0.05       0  5098.4    0.16       0
Bank Sta=4763.8,5172.9
Exp/Cntr=0.3,0.1

Type RM Length L Ch R = 1,15740,0,0,0
BEGIN DESCRIPTION:
UNT 134 in Running Cr Watershed 1.0
END DESCRIPTION:
XS GIS Cut Line= 3
      2881987.18      6998220.43      2881830.93      6998871.50
      2881995.86      6999427.07
#Sta/Elev= 30
  4481.1  429.78  4506.4  429.90  4558.8  427.80  4691.5  418.25  4768.8  414.34
  4773.9  413.15  4804.6  412.71  4815.9  411.20  4852.8  410.64  4894.8  407.65
  4930.5  403.15  4948.8  399.87  4955.9  399.21  4956.4  398.41  4961.4  398.41
  4961.9  399.21  5237.8  399.21  5241.8  399.87  5253.1  400.98  5258.6  403.17
  5286.9  404.94  5291.5  404.21  5319.5  405.72  5324.8  404.56  5358.0  406.70
  5429.6  407.24  5462.8  409.14  5534.5  411.28  5644.6  417.77  5730.2  420.85
#Mann=5,-1,0
  4481.1    0.16       0  4930.5    0.05       0  4955.9   0.033       0
  4961.9    0.05       0  5286.9    0.16       0
Bank Sta=4948.8,5241.8
Exp/Cntr=0.3,0.1

Chan Stop Cuts=-1