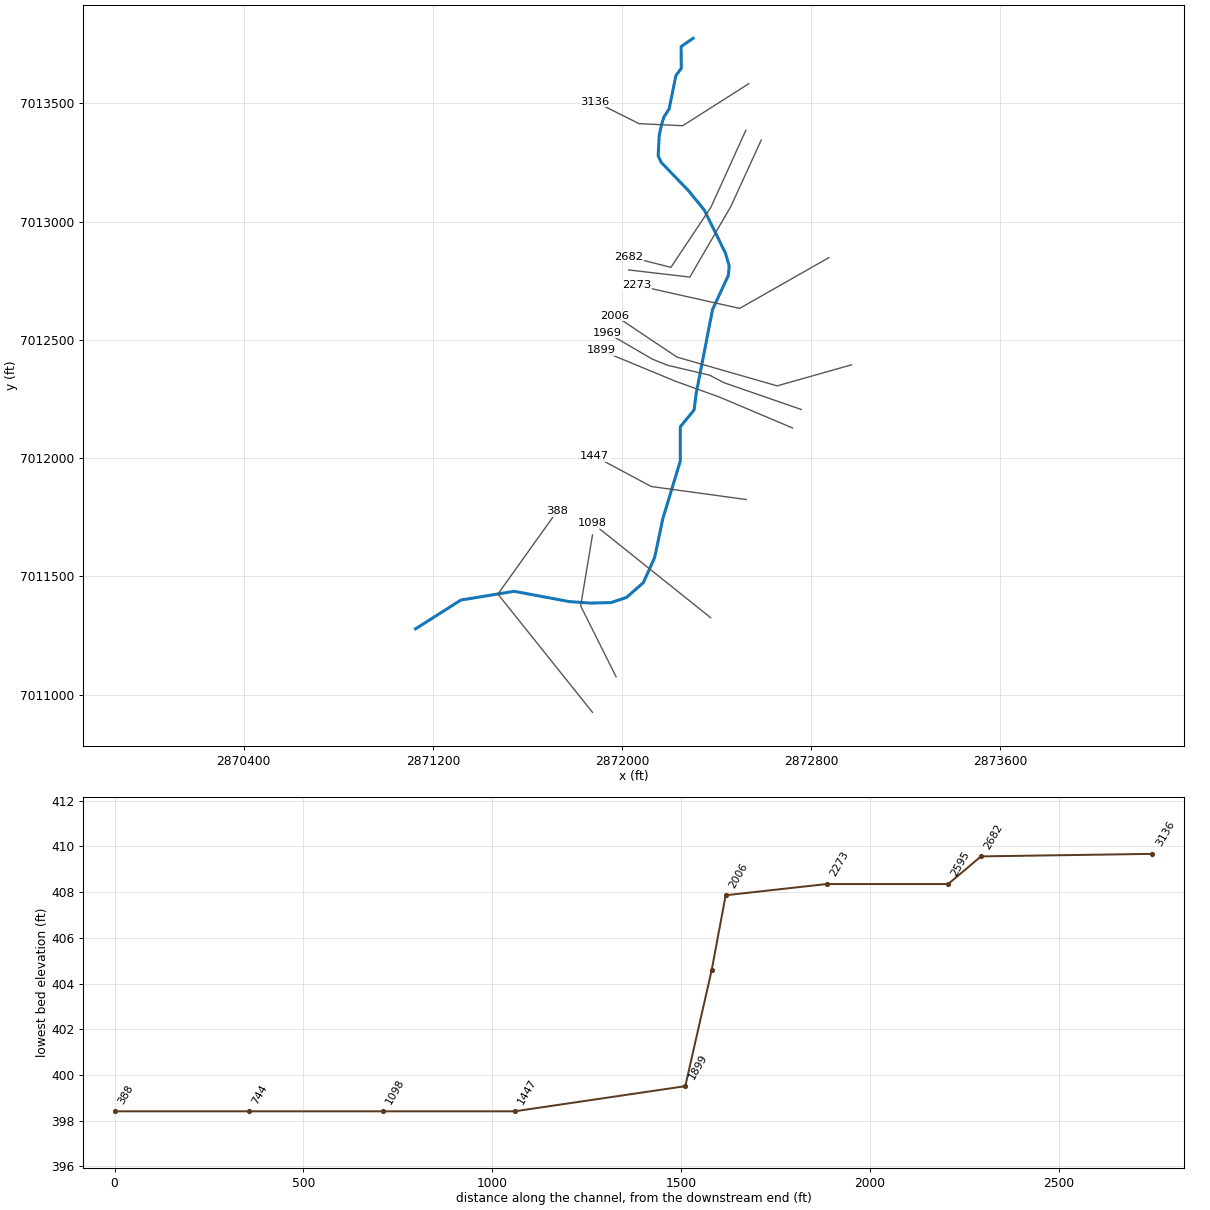
--- UNT 135 in Running Cr Watershed.prj (project) ---

Proj Title=UNT 135 in Running Cr Watershed Base Level Engineering
Current Plan=p01
Default Exp/Contr=0.3,0.1
English Units
Geom File=g01
Flow File=f01
Plan File=p01
BEGIN DESCRIPTION:
UNT 135 in Running Cr Watershed
END DESCRIPTION:

--- UNT 135 in Running Cr Watershed.p01 (plan) ---

Plan Title=Multiple Run
Short Identifier=Multiple
Geom File=g01
Flow File=f01
Subcritical Flow
K Sum by GR= 0
Std Step Tol= 0.01
Critical Tol= 0.01
Num of Std Step Trials= 20
Max Error Tol= 0.3
Flow Tol Ratio= 0.001
Split Flow NTrial= 30
Split Flow Tol= 0.02
Split Flow Ratio= 0.02
Log Output Level= 0
Friction Slope Method= 1
Unsteady Friction Slope Method= 2
Unsteady Bridges Friction Slope Method= 1
Parabolic Critical Depth
Global Vel Dist=  1 , 1 , 1
Global Log Level= 0
CheckData=True
Encroach Param= -1, 0, 0, 0
BEGIN DESCRIPTION:
Multiple Run
END DESCRIPTION:

--- UNT 135 in Running Cr Watershed.f01 (steady flow) ---

Flow Title=Multiple
Number of Profiles=7
Profile Names=10-year,25-year,50-year,1pct_min,100-year,1pct_plu,500-year
River Rch & RM= UNT 135 in Runni,Reach-1,3136
     204     254     291     166     332     663     432
Boundary for River Rch & Prof#=UNT 135 in Runni,Reach-1,1
Up Type=0
Dn Type=3
Dn Slope=0.005
Boundary for River Rch & Prof#=UNT 135 in Runni,Reach-1,2
Up Type=0
Dn Type=3
Dn Slope=0.005
Boundary for River Rch & Prof#=UNT 135 in Runni,Reach-1,3
Up Type=0
Dn Type=3
Dn Slope=0.005
Boundary for River Rch & Prof#=UNT 135 in Runni,Reach-1,4
Up Type=0
Dn Type=3
Dn Slope=0.005
Boundary for River Rch & Prof#=UNT 135 in Runni,Reach-1,5
Up Type=0
Dn Type=3
Dn Slope=0.005
Boundary for River Rch & Prof#=UNT 135 in Runni,Reach-1,6
Up Type=0
Dn Type=3
Dn Slope=0.005
Boundary for River Rch & Prof#=UNT 135 in Runni,Reach-1,7
Up Type=0
Dn Type=3
Dn Slope=0.005

--- UNT 135 in Running Cr Watershed.g01 (geometry) ---

Geom Title=Existing Conditions

River Reach=UNT 135 in Runni,Reach-1
Reach XY= 30
      2872300.59      7013775.71      2872249.71      7013740.33
      2872250.59      7013648.72      2872227.69      7013617.89
      2872199.50      7013477.82      2872177.48      7013443.47
      2872167.79      7013413.52      2872157.22      7013365.95
      2872152.82      7013278.74      2872165.15      7013251.43
      2872281.43      7013130.75      2872347.49      7013049.71
      2872437.34      7012867.36      2872453.20      7012812.75
      2872449.68      7012773.11      2872382.73      7012628.64
      2872313.47      7012273.53      2872304.80      7012204.17
      2872246.27      7012132.64      2872246.27      7011987.41
      2872172.58      7011744.64      2872137.89      7011579.90
      2872090.21      7011473.69      2872018.68      7011410.83
      2871953.65      7011389.16      2871866.95      7011386.99
      2871775.91      7011393.49      2871543.98      7011436.84
      2871318.55      7011400.00      2871126.58      7011278.04

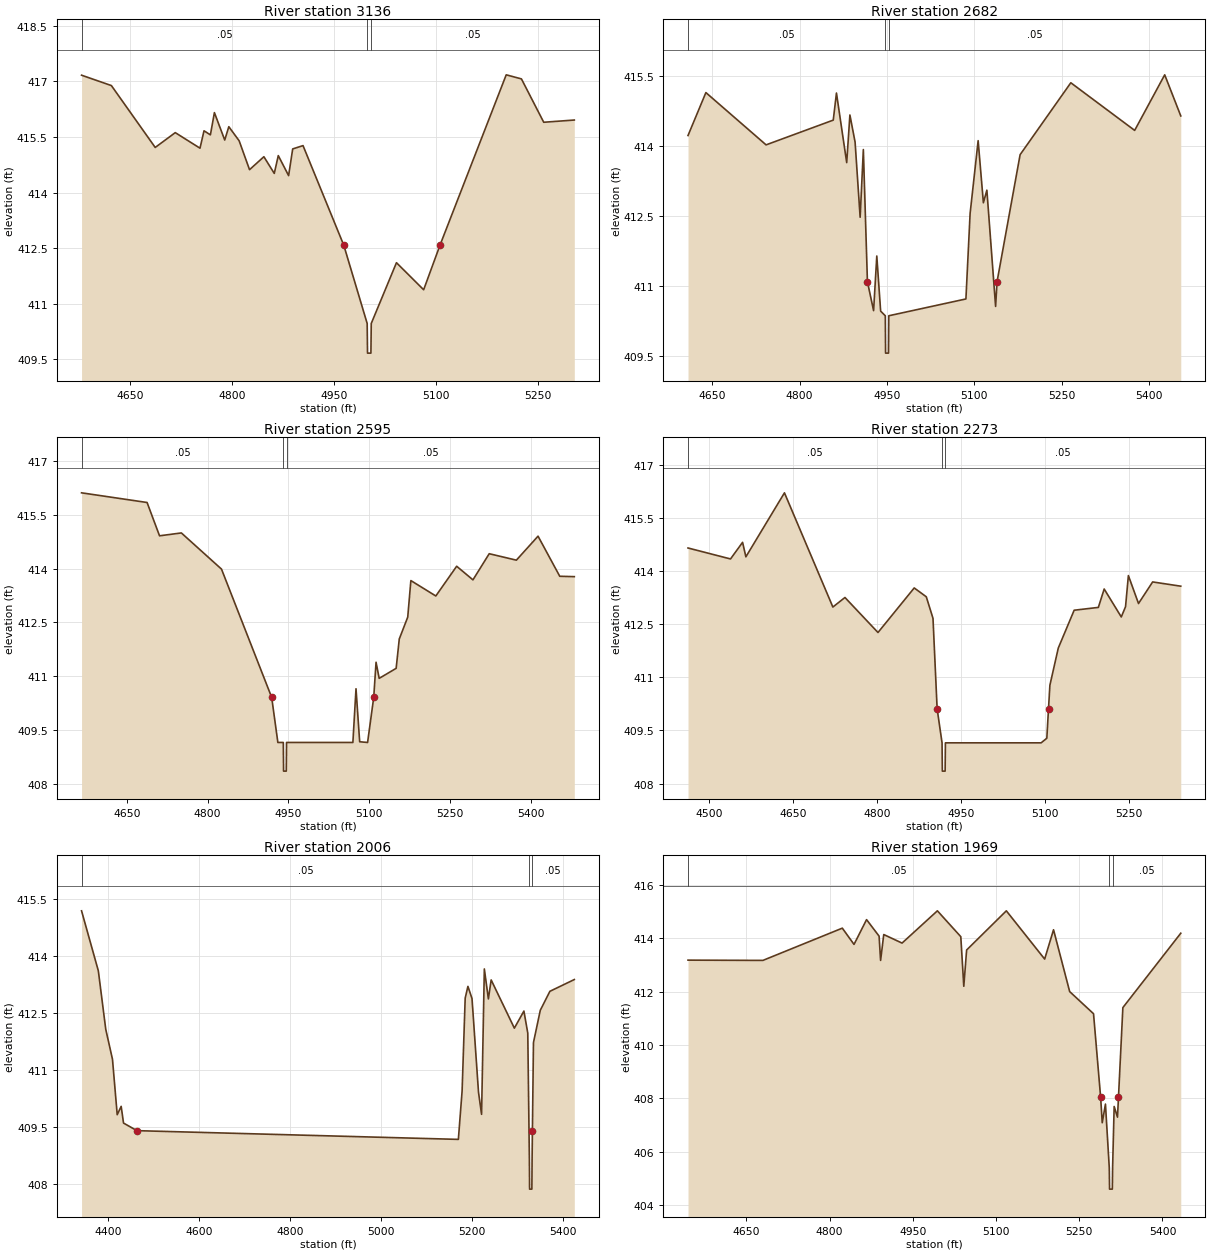
Type RM Length L Ch R = 1,3136,454,454,454
BEGIN DESCRIPTION:
UNT 135 in Running Cr Watershed 5.0
END DESCRIPTION:
XS GIS Cut Line= 4
      2872536.47      7013583.92      2872256.51      7013405.96
      2872072.04      7013414.64      2871885.38      7013507.97
#Sta/Elev= 30
  4578.7  417.17  4622.6  416.89  4687.1  415.22  4716.6  415.62  4753.0  415.20
  4758.9  415.67  4768.3  415.56  4774.2  416.16  4789.4  415.42  4795.4  415.78
  4810.6  415.40  4825.9  414.62  4847.0  414.97  4862.3  414.52  4868.2  415.00
  4883.4  414.46  4889.4  415.18  4904.6  415.27  4964.6  412.58  4999.0  410.47
  4999.5  409.67  5004.5  409.67  5005.0  410.47  5042.1  412.11  5082.1  411.38
  5106.1  412.58  5203.6  417.18  5226.0  417.07  5258.8  415.90  5303.8  415.96
#Mann=3,-1,0
  4578.7    0.05       0  4999.0    0.03       0  5005.0    0.05       0
Bank Sta=4964.6,5106.1
Exp/Cntr=0.3,0.1

Type RM Length L Ch R = 1,2682,87,87,87
BEGIN DESCRIPTION:
Mapping XS b2bbff50
END DESCRIPTION:
XS GIS Cut Line= 4
      2872523.41      7013386.38      2872375.86      7013060.91
      2872206.59      7012807.00      2872028.23      7012852.13
#Sta/Elev= 30
  4608.2  414.22  4638.9  415.14  4742.3  414.02  4857.7  414.55  4863.2  415.13
  4880.8  413.64  4886.3  414.66  4895.2  414.08  4903.9  412.47  4909.4  413.92
  4916.4  411.09  4927.0  410.47  4932.5  411.64  4939.1  410.46  4947.1  410.36
  4947.6  409.56  4952.6  409.56  4953.1  410.36  5085.6  410.72  5092.8  412.55
  5106.6  414.11  5115.6  412.78  5121.6  413.05  5136.6  410.56  5139.1  411.09
  5178.7  413.81  5265.8  415.35  5375.5  414.33  5427.1  415.52  5454.7  414.64
#Mann=3,-1,0
  4608.2    0.05       0  4947.1    0.03       0  4953.1    0.05       0
Bank Sta=4916.4,5139.1
Exp/Cntr=0.3,0.1

Type RM Length L Ch R = 1,2595,322,322,322
BEGIN DESCRIPTION:
Mapping XS 1d21b565
END DESCRIPTION:
XS GIS Cut Line= 4
      2872588.52      7013345.15      2872460.50      7013065.25
      2872286.89      7012765.77      2872028.19      7012795.95
#Sta/Elev= 30
  4566.0  416.12  4687.6  415.85  4710.7  414.92  4751.2  415.00  4825.7  413.99
  4918.8  410.41  4930.3  409.15  4940.4  409.15  4940.9  408.35  4945.9  408.35
  4946.4  409.15  5069.5  409.15  5075.3  410.65  5082.1  409.17  5096.8  409.15
  5108.2  410.41  5112.5  411.39  5118.3  410.94  5149.8  411.22  5155.6  412.04
  5171.3  412.65  5177.1  413.67  5223.4  413.24  5262.1  414.07  5292.3  413.69
  5322.5  414.42  5372.9  414.24  5413.1  414.91  5453.4  413.79  5480.4  413.78
#Mann=3,-1,0
  4566.0    0.05       0  4940.4    0.03       0  4946.4    0.05       0
Bank Sta=4918.8,5108.2
Exp/Cntr=0.3,0.1

Type RM Length L Ch R = 1,2273,267,267,267
BEGIN DESCRIPTION:
Mapping XS e808470a
END DESCRIPTION:
XS GIS Cut Line= 3
      2872874.97      7012848.22      2872497.39      7012633.39
      2872061.20      7012731.04
#Sta/Elev= 30
  4462.0  414.66  4538.0  414.35  4559.6  414.82  4565.5  414.41  4634.5  416.22
  4721.1  412.99  4742.7  413.26  4801.8  412.27  4866.6  413.53  4888.2  413.28
  4900.2  412.67  4907.6  410.11  4916.4  409.15  4916.9  408.35  4921.9  408.35
  4922.4  409.15  5093.6  409.15  5103.8  409.28  5106.8  410.11  5109.3  410.78
  5124.3  411.83  5152.7  412.90  5196.0  412.98  5206.4  413.50  5237.0  412.71
  5244.6  413.00  5249.7  413.88  5267.8  413.09  5293.1  413.70  5343.4  413.58
#Mann=3,-1,0
  4462.0    0.05       0  4916.4   0.033       0  4922.4    0.05       0
Bank Sta=4907.6,5106.8
Exp/Cntr=0.3,0.1

Type RM Length L Ch R = 1,2006,37,37,37
BEGIN DESCRIPTION:
Mapping XS 13c6cf75
END DESCRIPTION:
XS GIS Cut Line= 4
      2872970.47      7012394.67      2872655.81      7012305.70
      2872232.63      7012427.23      2871970.02      7012603.03
#Sta/Elev= 30
  4341.9  415.19  4378.8  413.61  4395.1  412.07  4409.9  411.28  4420.3  409.82
  4429.0  410.04  4434.2  409.60  4463.7  409.40  5170.3  409.17  5178.5  410.44
  5185.3  412.89  5191.3  413.20  5200.3  412.88  5214.6  410.41  5221.3  409.83
  5227.4  413.66  5236.3  412.87  5242.4  413.37  5293.4  412.10  5314.4  412.55
  5322.9  411.97  5326.4  408.66  5326.9  407.86  5331.9  407.86  5332.4  408.66
  5333.1  409.40  5335.4  411.72  5350.4  412.57  5371.5  413.07  5425.2  413.38
#Mann=3,-1,0
  4341.9    0.05       0  5326.4   0.033       0  5332.4    0.05       0
Bank Sta=4463.7,5333.1
Exp/Cntr=0.3,0.1

Type RM Length L Ch R = 1,1969,70,70,70
BEGIN DESCRIPTION:
Mapping XS d50cb19c
END DESCRIPTION:
XS GIS Cut Line= 6
      2872757.83      7012205.87      2872432.29      7012318.72
      2872369.35      7012351.27      2872193.57      7012392.50
      2872128.47      7012418.55      2871936.51      7012530.70
#Sta/Elev= 30
  4544.6  413.18  4679.6  413.17  4822.8  414.38  4843.9  413.77  4866.5  414.70
  4889.1  414.08  4891.8  413.17  4897.5  414.14  4930.5  413.82  4994.2  415.03
  5036.4  414.06  5041.8  412.20  5046.9  413.56  5118.5  415.03  5187.6  413.22
  5203.6  414.32  5232.7  412.00  5275.7  411.17  5288.5  408.04  5291.4  407.08
  5297.2  407.78  5304.1  405.39  5304.6  404.59  5309.6  404.59  5310.1  405.39
  5312.9  407.69  5318.9  407.29  5320.7  408.04  5328.6  411.40  5433.0  414.19
#Mann=3,-1,0
  4544.6    0.05       0  5304.1   0.033       0  5310.1    0.05       0
Bank Sta=5288.5,5320.7
Exp/Cntr=0.3,0.1

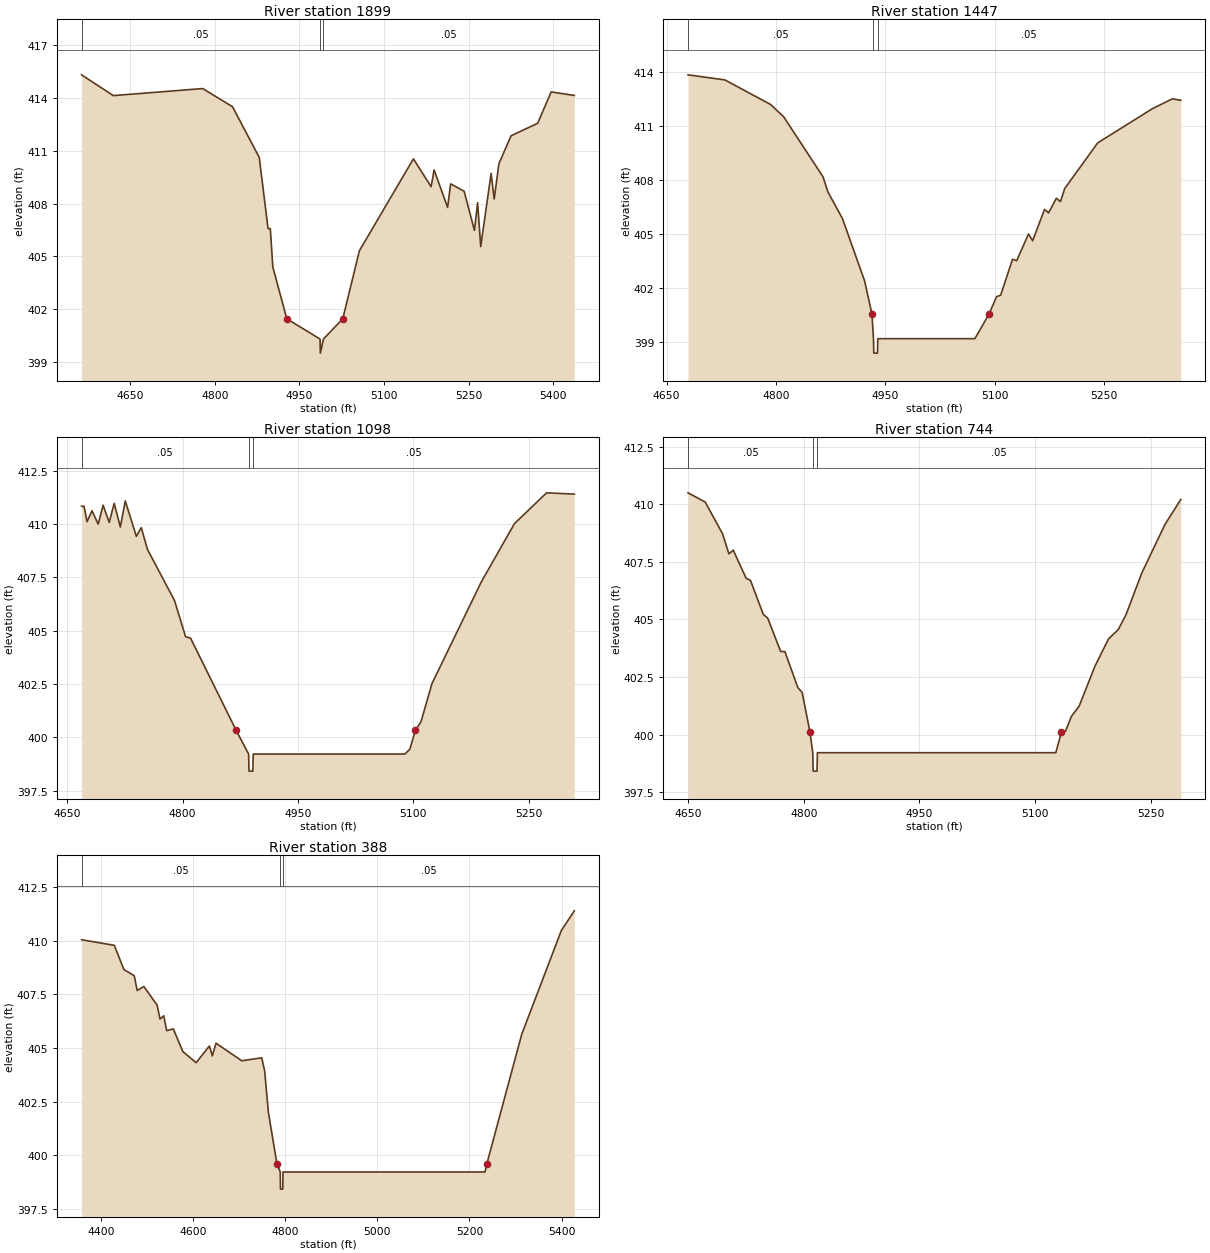
Type RM Length L Ch R = 1,1899,452,452,452
BEGIN DESCRIPTION:
Mapping XS 5092b4ae
END DESCRIPTION:
XS GIS Cut Line= 4
      2872720.95      7012127.73      2872412.76      7012257.96
      2872226.12      7012325.23      2871911.46      7012455.44
#Sta/Elev= 30
  4563.8  415.31  4620.1  414.13  4778.6  414.53  4831.4  413.50  4878.8  410.62
  4894.4  406.58  4898.4  406.58  4902.9  404.40  4927.6  401.46  4986.6  400.31
  4987.1  399.51  4992.6  400.31  5026.9  401.46  5056.3  405.32  5152.1  410.54
  5183.4  408.96  5188.8  409.91  5212.7  407.78  5218.1  409.12  5242.0  408.70
  5260.3  406.48  5265.9  408.05  5271.4  405.56  5289.8  409.71  5295.3  408.26
  5303.6  410.26  5325.2  411.85  5372.4  412.56  5396.3  414.34  5437.3  414.14
#Mann=3,-1,0
  4563.8    0.05       0  4986.6    0.03       0  4992.6    0.05       0
Bank Sta=4927.6,5026.9
Exp/Cntr=0.3,0.1

Type RM Length L Ch R = 1,1447,349,349,349
BEGIN DESCRIPTION:
UNT 135 in Running Cr Watershed 4.0
END DESCRIPTION:
XS GIS Cut Line= 3
      2872525.00      7011825.00      2872123.41      7011880.09
      2871884.54      7012007.96
#Sta/Elev= 30
  4679.3  413.83  4729.8  413.55  4792.5  412.19  4810.5  411.51  4864.6  408.18
  4871.1  407.36  4891.3  405.86  4921.6  402.42  4931.8  400.56  4933.8  399.21
  4934.3  398.41  4939.3  398.41  4939.8  399.21  5073.0  399.21  5092.2  400.56
  5102.8  401.54  5108.4  401.62  5124.7  403.61  5130.4  403.53  5146.6  405.01
  5152.3  404.64  5168.6  406.37  5174.2  406.18  5184.8  406.99  5190.5  406.81
  5196.3  407.53  5241.6  410.06  5316.5  411.95  5344.1  412.50  5355.6  412.42
#Mann=3,-1,0
  4679.3    0.05       0  4933.8   0.033       0  4939.8    0.05       0
Bank Sta=4931.8,5092.2
Exp/Cntr=0.3,0.1

Type RM Length L Ch R = 1,1098,354,354,354
BEGIN DESCRIPTION:
UNT 135 in Running Cr Watershed 3.0
END DESCRIPTION:
XS GIS Cut Line= 3
      2872374.97      7011325.02      2872125.00      7011525.00
      2871874.98      7011725.01
#Sta/Elev= 30
  4668.8  410.83  4672.0  410.83  4676.0  410.11  4682.4  410.62  4690.4  409.99
  4696.8  410.88  4704.8  410.07  4711.2  410.97  4719.2  409.86  4725.6  411.08
  4740.0  409.42  4746.4  409.83  4754.4  408.81  4789.6  406.41  4804.0  404.71
  4810.4  404.65  4869.7  400.32  4885.9  399.21  4886.4  398.41  4891.4  398.41
  4891.9  399.21  5089.0  399.21  5095.4  399.44  5102.6  400.32  5109.8  400.72
  5124.2  402.52  5188.2  407.28  5231.4  410.02  5273.1  411.46  5309.1  411.40
#Mann=3,-1,0
  4668.8    0.05       0  4885.9   0.033       0  4891.9    0.05       0
Bank Sta=4869.7,5102.6
Exp/Cntr=0.3,0.1

Type RM Length L Ch R = 1,744,356,356,356
BEGIN DESCRIPTION:
UNT 135 in Running Cr Watershed 2.0
END DESCRIPTION:
XS GIS Cut Line= 3
      2871974.99      7011075.02      2871825.00      7011375.00
      2871875.00      7011674.98
#Sta/Elev= 30
  4649.6  410.50  4671.9  410.10  4694.3  408.73  4702.7  407.85  4708.3  408.01
  4725.0  406.79  4730.6  406.70  4747.4  405.21  4753.0  405.06  4769.8  403.61
  4775.4  403.60  4792.1  402.04  4797.7  401.83  4807.9  400.10  4811.5  399.21
  4812.0  398.41  4817.0  398.41  4817.5  399.21  5126.9  399.21  5134.2  400.10
  5139.6  400.15  5147.2  400.79  5157.3  401.24  5177.6  402.96  5195.3  404.15
  5208.0  404.56  5218.2  405.22  5238.4  407.01  5268.8  409.14  5289.1  410.21
#Mann=3,-1,0
  4649.6    0.05       0  4811.5   0.033       0  4817.5    0.05       0
Bank Sta=4807.9,5134.2
Exp/Cntr=0.3,0.1

Type RM Length L Ch R = 1,388,0,0,0
BEGIN DESCRIPTION:
UNT 135 in Running Cr Watershed 1.0
END DESCRIPTION:
XS GIS Cut Line= 3
      2871875.00      7010925.00      2871475.00      7011425.00
      2871724.98      7011774.98
#Sta/Elev= 30
  4357.4  410.05  4428.6  409.79  4449.4  408.66  4471.9  408.37  4478.3  407.68
  4492.7  407.87  4521.5  407.00  4527.9  406.35  4535.9  406.50  4542.3  405.81
  4556.7  405.89  4577.5  404.83  4606.3  404.31  4635.1  405.09  4641.5  404.63
  4649.5  405.22  4705.6  404.40  4748.8  404.54  4755.2  403.92  4763.2  402.00
  4781.9  399.59  4789.0  399.21  4789.5  398.41  4794.5  398.41  4795.0  399.21
  5233.7  399.21  5237.8  399.59  5313.5  405.63  5399.6  410.48  5427.8  411.40
#Mann=3,-1,0
  4357.4    0.05       0  4789.0   0.033       0  4795.0    0.05       0
Bank Sta=4781.9,5237.8
Exp/Cntr=0.3,0.1

Chan Stop Cuts=-1