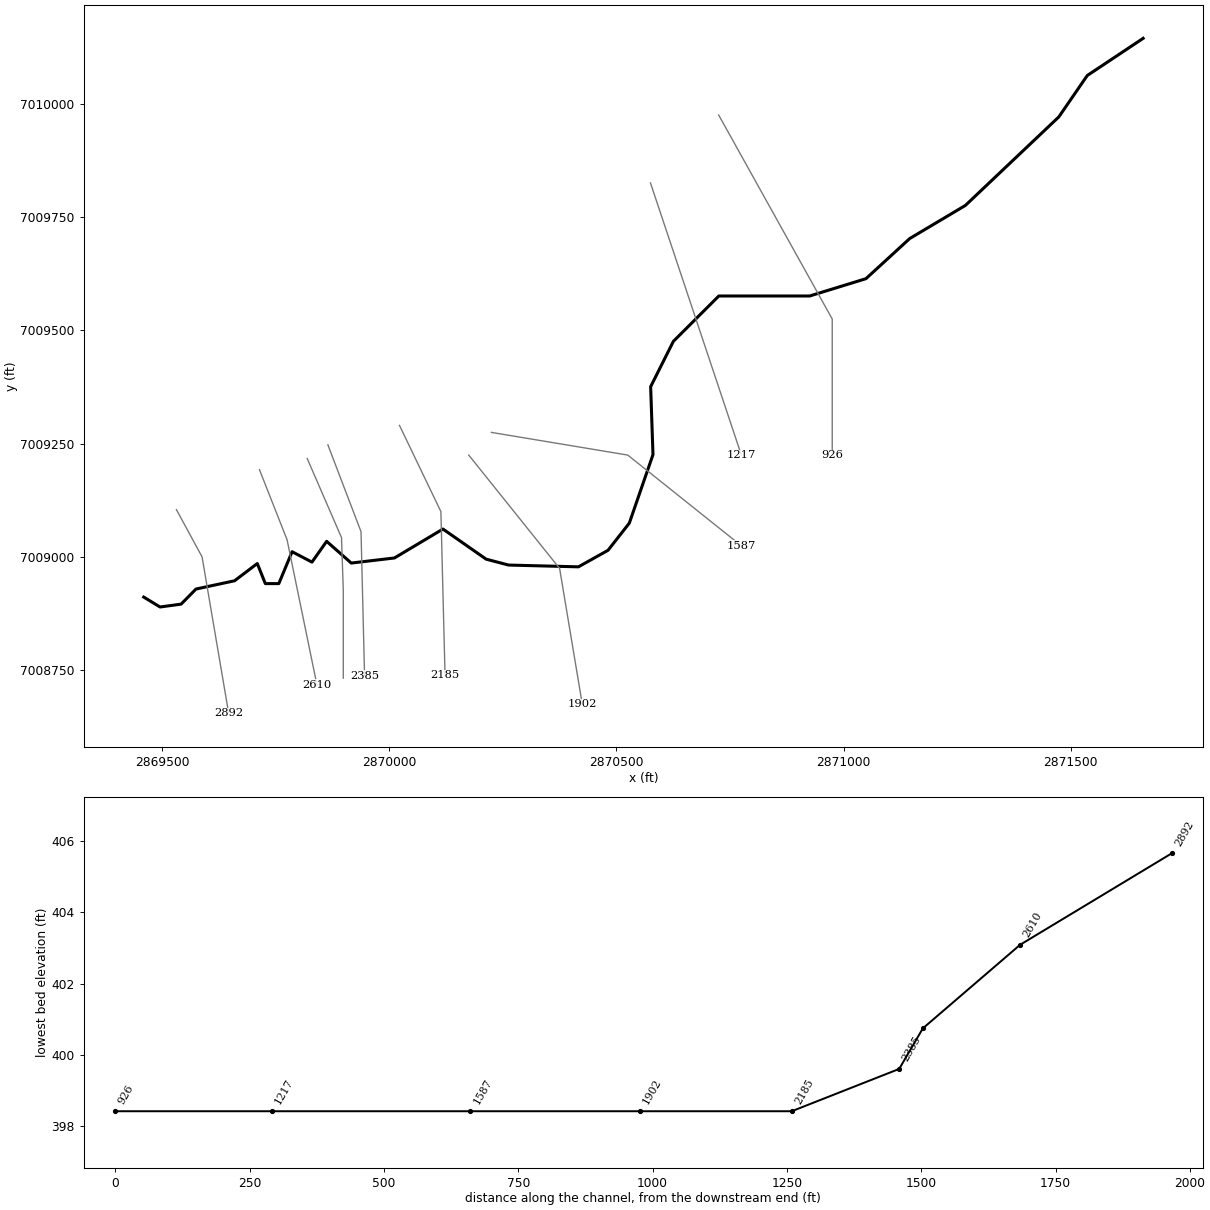
--- UNT 136 in Running Cr Watershed.prj (project) ---

Proj Title=UNT 136 in Running Cr Watershed Base Level Engineering
Current Plan=p01
Default Exp/Contr=0.3,0.1
English Units
Geom File=g01
Flow File=f01
Plan File=p01
BEGIN DESCRIPTION:
UNT 136 in Running Cr Watershed
END DESCRIPTION:

--- UNT 136 in Running Cr Watershed.p01 (plan) ---

Plan Title=Multiple Run
Short Identifier=Multiple
Geom File=g01
Flow File=f01
Subcritical Flow
K Sum by GR= 0
Std Step Tol= 0.01
Critical Tol= 0.01
Num of Std Step Trials= 20
Max Error Tol= 0.3
Flow Tol Ratio= 0.001
Split Flow NTrial= 30
Split Flow Tol= 0.02
Split Flow Ratio= 0.02
Log Output Level= 0
Friction Slope Method= 1
Unsteady Friction Slope Method= 2
Unsteady Bridges Friction Slope Method= 1
Parabolic Critical Depth
Global Vel Dist=  1 , 1 , 1
Global Log Level= 0
CheckData=True
Encroach Param= -1, 0, 0, 0
BEGIN DESCRIPTION:
Multiple Run
END DESCRIPTION:

--- UNT 136 in Running Cr Watershed.f01 (steady flow) ---

Flow Title=Multiple
Number of Profiles=7
Profile Names=10-year,25-year,50-year,1pct_min,100-year,1pct_plu,500-year
River Rch & RM= UNT 136 in Runni,Reach-1,2892
     176     216     246     139     278     555     356
Boundary for River Rch & Prof#=UNT 136 in Runni,Reach-1,1
Up Type=0
Dn Type=3
Dn Slope=0.005
Boundary for River Rch & Prof#=UNT 136 in Runni,Reach-1,2
Up Type=0
Dn Type=3
Dn Slope=0.005
Boundary for River Rch & Prof#=UNT 136 in Runni,Reach-1,3
Up Type=0
Dn Type=3
Dn Slope=0.005
Boundary for River Rch & Prof#=UNT 136 in Runni,Reach-1,4
Up Type=0
Dn Type=3
Dn Slope=0.005
Boundary for River Rch & Prof#=UNT 136 in Runni,Reach-1,5
Up Type=0
Dn Type=3
Dn Slope=0.005
Boundary for River Rch & Prof#=UNT 136 in Runni,Reach-1,6
Up Type=0
Dn Type=3
Dn Slope=0.005
Boundary for River Rch & Prof#=UNT 136 in Runni,Reach-1,7
Up Type=0
Dn Type=3
Dn Slope=0.005

--- UNT 136 in Running Cr Watershed.g01 (geometry) ---

Geom Title=Existing Conditions

River Reach=UNT 136 in Runni,Reach-1
Reach XY= 30
      2869459.65      7008911.92      2869495.59      7008890.04
      2869541.95      7008896.29      2869574.76      7008929.62
      2869659.65      7008947.85      2869709.65      7008985.87
      2869727.36      7008941.60      2869757.05      7008941.60
      2869786.22      7009011.92      2869829.97      7008989.00
      2869862.26      7009034.83      2869916.43      7008986.92
      2870011.48      7008998.11      2870118.25      7009061.92
      2870213.30      7008995.51      2870262.78      7008982.49
      2870416.43      7008978.58      2870481.53      7009015.04
      2870528.40      7009074.94      2870580.49      7009225.98
      2870575.36      7009375.80      2870625.36      7009475.80
      2870725.36      7009575.80      2870925.36      7009575.80
      2871049.24      7009614.00      2871145.59      7009702.54
      2871267.99      7009775.46      2871473.72      7009970.77
      2871536.22      7010061.92      2871659.28      7010143.95

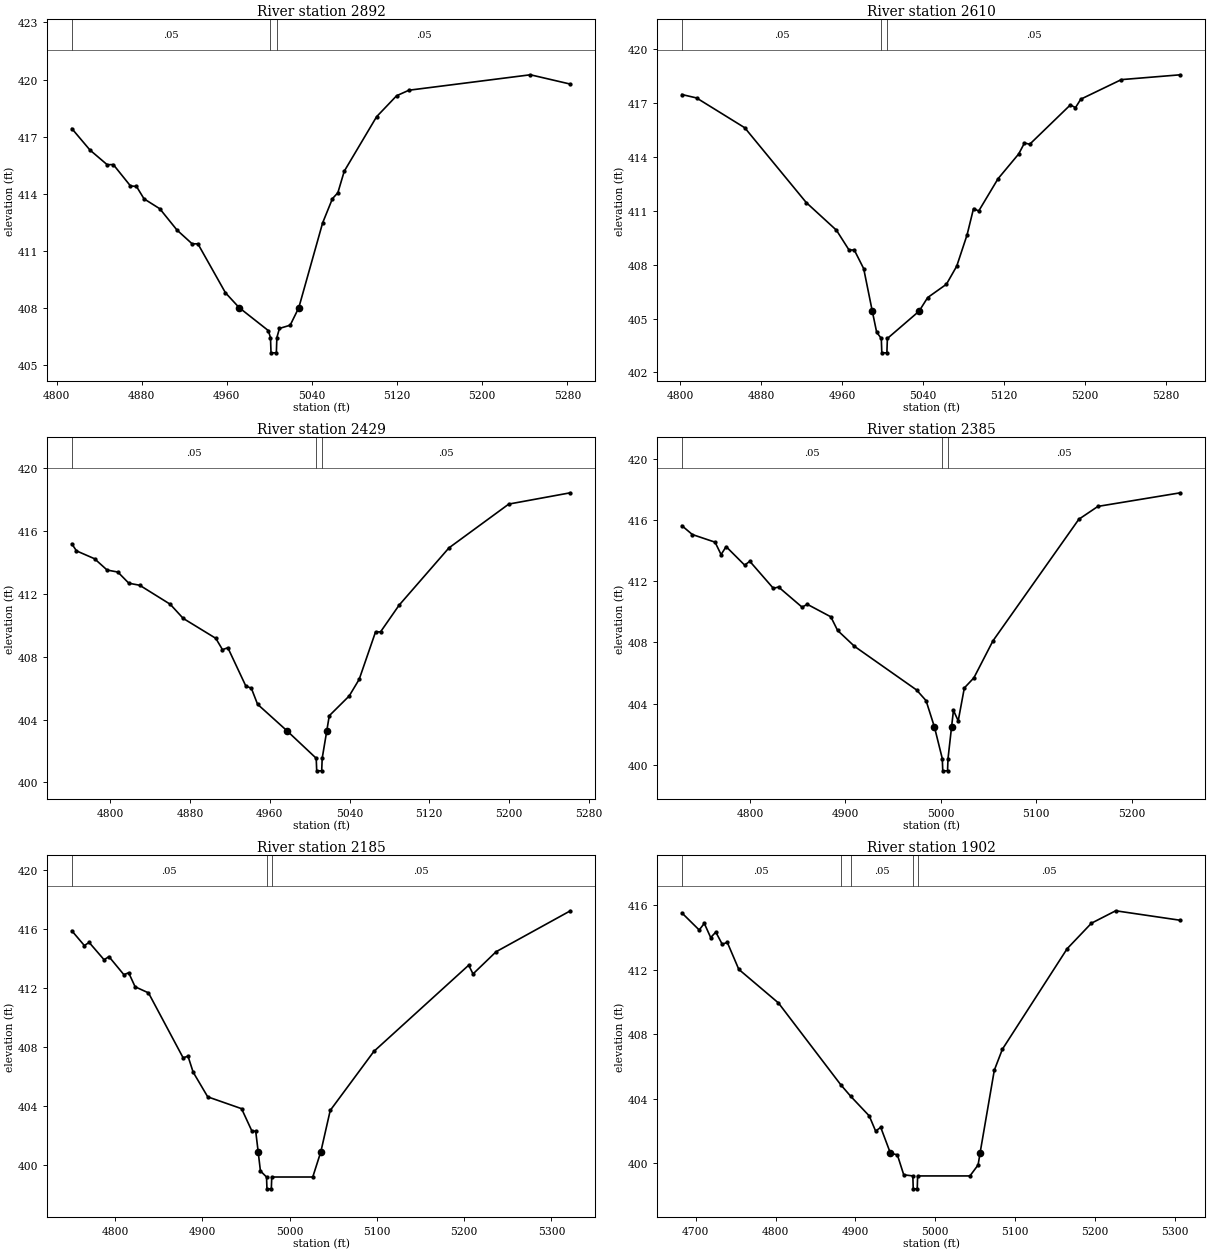
Type RM Length L Ch R = 1,2892,282,282,282
BEGIN DESCRIPTION:
UNT 136 in Running Cr Watershed 5.0
END DESCRIPTION:
XS GIS Cut Line= 3
      2869531.69      7009104.71      2869588.13      7009000.51
      2869646.72      7008655.45
#Sta/Elev= 30
  4814.3  417.43  4831.4  416.30  4847.6  415.53  4853.3  415.54  4869.4  414.42
  4875.1  414.39  4882.2  413.74  4897.0  413.22  4913.2  412.10  4927.4  411.38
  4932.8  411.38  4958.7  408.81  4971.6  408.03  4998.9  406.83  5001.0  406.46
  5001.5  405.66  5006.5  405.66  5007.0  406.46  5009.4  406.94  5019.5  407.11
  5027.6  408.03  5050.0  412.48  5059.2  413.75  5064.3  414.06  5070.3  415.19
  5100.7  418.05  5119.5  419.15  5131.1  419.44  5245.2  420.25  5282.8  419.76
#Mann=3,-1,0
  4814.3    0.05       0  5001.0    0.03       0  5007.0    0.05       0
Bank Sta=4971.6,5027.6
Exp/Cntr=0.3,0.1

Type RM Length L Ch R = 1,2610,181,181,181
BEGIN DESCRIPTION:
Mapping XS 78518415
END DESCRIPTION:
XS GIS Cut Line= 3
      2869714.42      7009192.82      2869775.20      7009038.27
      2869840.88      7008718.52
#Sta/Elev= 30
  4801.7  417.48  4816.2  417.29  4863.8  415.63  4924.6  411.46  4954.4  409.92
  4966.8  408.82  4972.0  408.82  4981.3  407.78  4989.8  405.41  4994.1  404.24
  4998.7  403.89  4999.2  403.09  5004.2  403.09  5004.7  403.89  5036.0  405.41
  5044.5  406.17  5063.0  406.91  5073.2  407.92  5083.4  409.66  5089.8  411.13
  5094.9  410.99  5114.0  412.79  5134.4  414.17  5140.1  414.78  5145.3  414.71
  5185.4  416.90  5190.5  416.75  5195.7  417.22  5235.8  418.31  5294.2  418.58
#Mann=3,-1,0
  4801.7    0.05       0  4998.7    0.03       0  5004.7    0.05       0
Bank Sta=4989.8,5036
Exp/Cntr=0.3,0.1

Type RM Length L Ch R = 1,2429,44,44,44
BEGIN DESCRIPTION:
Mapping XS a0334b13
END DESCRIPTION:
XS GIS Cut Line= 4
      2869819.49      7009217.48      2869894.99      7009043.04
      2869898.90      7008927.15      2869898.90      7008733.18
#Sta/Elev= 30
  4761.5  415.20  4766.2  414.75  4784.3  414.25  4796.9  413.53  4807.7  413.40
  4818.7  412.69  4829.6  412.56  4860.2  411.35  4873.2  410.45  4905.9  409.18
  4912.6  408.46  4918.0  408.58  4936.1  406.13  4941.5  406.01  4947.8  404.98
  4977.3  403.29  5006.6  401.54  5007.1  400.74  5012.1  400.74  5012.6  401.54
  5017.2  403.29  5019.7  404.25  5039.7  405.51  5049.7  406.57  5066.1  409.59
  5071.1  409.59  5089.7  411.29  5139.7  414.94  5199.7  417.73  5261.5  418.45
#Mann=3,-1,0
  4761.5    0.05       0  5006.6    0.03       0  5012.6    0.05       0
Bank Sta=4977.3,5017.2
Exp/Cntr=0.3,0.1

Type RM Length L Ch R = 1,2385,200,200,200
BEGIN DESCRIPTION:
Mapping XS 1c6ec73c
END DESCRIPTION:
XS GIS Cut Line= 3
      2869865.03      7009247.50      2869937.96      7009056.06
      2869945.73      7008738.52
#Sta/Elev= 30
  4728.7  415.63  4739.7  415.05  4763.5  414.55  4769.8  413.74  4775.1  414.26
  4794.5  413.05  4799.9  413.30  4824.6  411.53  4830.0  411.62  4854.7  410.30
  4860.1  410.49  4884.8  409.67  4891.9  408.78  4909.6  407.74  4974.6  404.89
  4984.6  404.19  4993.4  402.46  5001.6  400.40  5002.1  399.60  5007.1  399.60
  5007.6  400.40  5011.3  402.46  5013.3  403.55  5018.3  402.87  5024.7  405.02
  5034.7  405.68  5054.7  408.10  5144.7  416.05  5164.7  416.89  5251.2  417.78
#Mann=3,-1,0
  4728.7    0.05       0  5001.6    0.03       0  5007.6    0.05       0
Bank Sta=4993.4,5011.3
Exp/Cntr=0.3,0.1

Type RM Length L Ch R = 1,2185,283,283,283
BEGIN DESCRIPTION:
Mapping XS 724b14ce
END DESCRIPTION:
XS GIS Cut Line= 3
      2870022.59      7009290.44      2870113.74      7009100.33
      2870122.85      7008739.78
#Sta/Elev= 30
  4750.3  415.86  4764.7  414.86  4770.2  415.07  4787.3  413.90  4792.9  414.11
  4810.0  412.89  4815.5  413.02  4822.9  412.07  4838.2  411.66  4877.9  407.27
  4883.5  407.38  4889.4  406.30  4906.1  404.63  4944.9  403.83  4956.8  402.31
  4961.1  402.31  4963.9  400.93  4966.5  399.62  4973.5  399.21  4974.0  398.41
  4979.0  398.41  4979.5  399.21  5026.5  399.21  5035.8  400.93  5046.5  403.71
  5096.5  407.70  5205.2  413.53  5210.2  412.94  5236.6  414.44  5321.8  417.21
#Mann=3,-1,0
  4750.3    0.05       0  4973.5    0.03       0  4979.5    0.05       0
Bank Sta=4963.9,5035.8
Exp/Cntr=0.3,0.1

Type RM Length L Ch R = 1,1902,315,315,315
BEGIN DESCRIPTION:
UNT 136 in Running Cr Watershed 4.0
END DESCRIPTION:
XS GIS Cut Line= 3
      2870174.97      7009225.03      2870375.00      7008975.00
      2870424.99      7008675.03
#Sta/Elev= 30
  4682.7  415.51  4704.4  414.45  4710.8  414.86  4718.8  413.98  4725.2  414.32
  4733.2  413.57  4739.6  413.68  4754.0  412.01  4803.6  409.93  4881.8  404.85
  4894.2  404.14  4917.3  402.93  4925.3  401.99  4931.7  402.22  4943.9  400.61
  4952.5  400.52  4960.5  399.28  4971.9  399.21  4972.4  398.41  4977.4  398.41
  4977.9  399.21  5043.4  399.21  5053.6  399.89  5056.0  400.61  5073.9  405.76
  5084.0  407.06  5165.1  413.29  5195.5  414.87  5225.9  415.64  5307.0  415.05
#Mann=5,-1,0
  4682.7    0.05       0  4881.8    0.16       0  4894.2    0.05       0
  4971.9   0.035       0  4977.9    0.05       0
Bank Sta=4943.9,5056
Exp/Cntr=0.3,0.1

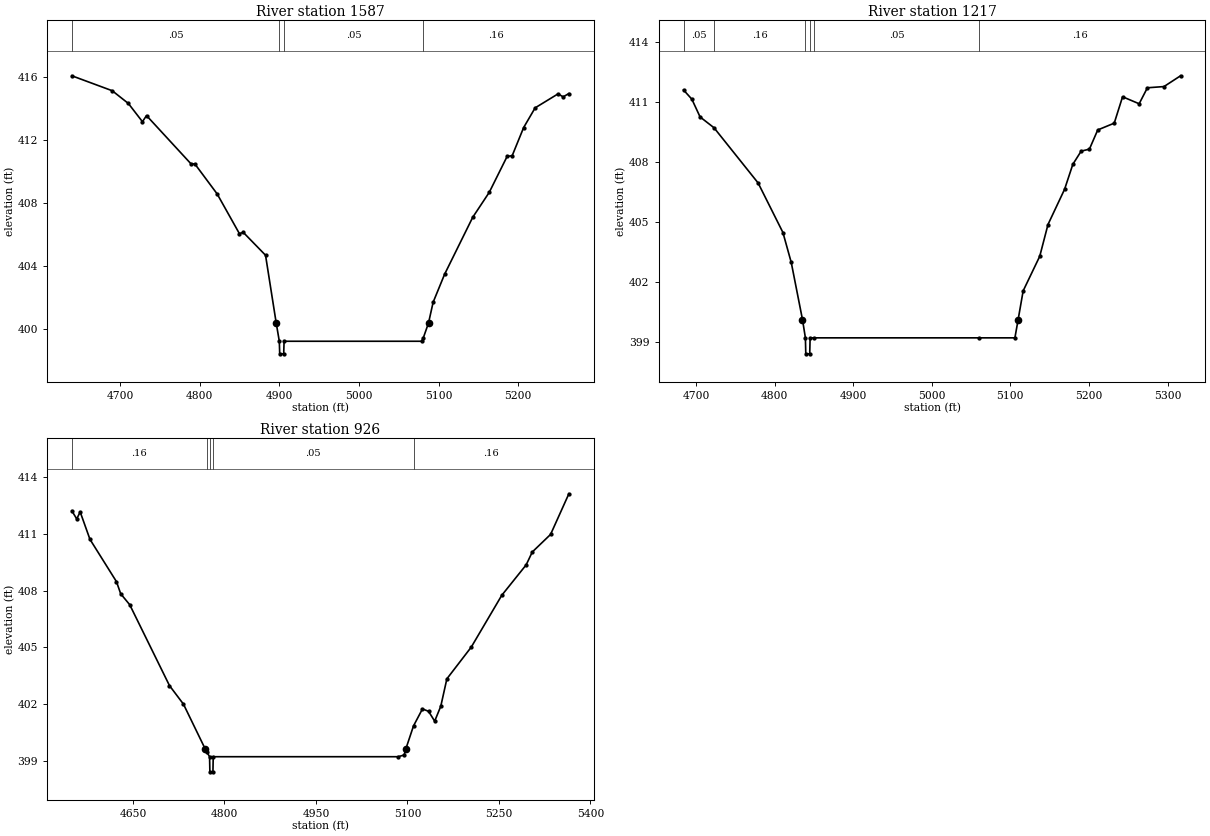
Type RM Length L Ch R = 1,1587,370,370,370
BEGIN DESCRIPTION:
UNT 136 in Running Cr Watershed 3.0
END DESCRIPTION:
XS GIS Cut Line= 3
      2870224.99      7009275.00      2870525.00      7009225.00
      2870774.99      7009025.01
#Sta/Elev= 30
  4639.3  416.09  4690.0  415.14  4710.3  414.33  4728.0  413.17  4733.1  413.56
  4788.8  410.50  4793.9  410.48  4821.8  408.58  4849.7  406.06  4854.7  406.13
  4882.6  404.68  4896.0  400.37  4899.9  399.21  4900.4  398.41  4905.4  398.41
  4905.9  399.21  5078.7  399.21  5080.8  399.43  5087.3  400.37  5093.1  401.69
  5107.5  403.47  5142.8  407.09  5163.6  408.68  5186.0  410.96  5192.4  411.01
  5206.8  412.80  5221.2  414.05  5250.0  414.94  5256.4  414.75  5263.6  414.96
#Mann=4,-1,0
  4639.3    0.05       0  4899.9   0.033       0  4905.9    0.05       0
  5080.8    0.16       0
Bank Sta=4896,5087.3
Exp/Cntr=0.3,0.1

Type RM Length L Ch R = 1,1217,291,291,291
BEGIN DESCRIPTION:
UNT 136 in Running Cr Watershed 2.0
END DESCRIPTION:
XS GIS Cut Line= 3
      2870574.99      7009825.02      2870675.00      7009525.00
      2870775.01      7009224.98
#Sta/Elev= 30
  4684.1  411.61  4694.7  411.15  4705.2  410.26  4722.9  409.72  4779.0  406.96
  4810.6  404.48  4821.2  402.98  4835.5  400.12  4839.2  399.21  4839.7  398.41
  4844.7  398.41  4845.2  399.21  4850.5  399.21  5059.6  399.21  5105.8  399.21
  5109.9  400.12  5116.3  401.56  5137.4  403.29  5147.9  404.88  5169.0  406.64
  5179.5  407.89  5190.1  408.55  5200.6  408.65  5211.2  409.61  5232.2  409.95
  5242.8  411.27  5263.9  410.92  5274.4  411.72  5295.5  411.78  5316.6  412.32
#Mann=6,-1,0
  4684.1    0.05       0  4722.9    0.16       0  4839.2   0.033       0
  4845.2    0.16       0  4850.5    0.05       0  5059.6    0.16       0
Bank Sta=4835.5,5109.9
Exp/Cntr=0.3,0.1

Type RM Length L Ch R = 1,926,0,0,0
BEGIN DESCRIPTION:
UNT 136 in Running Cr Watershed 1.0
END DESCRIPTION:
XS GIS Cut Line= 3
      2870725.01      7009974.98      2870975.00      7009525.00
      2870975.00      7009224.96
#Sta/Elev= 30
  4549.8  412.22  4557.8  411.79  4563.5  412.16  4579.5  410.71  4623.0  408.47
  4629.9  407.83  4644.7  407.25  4709.9  402.97  4732.8  401.99  4768.3  399.63
  4770.9  399.47  4775.6  399.21  4776.1  398.41  4781.1  398.41  4781.6  399.21
  5084.6  399.21  5094.6  399.30  5097.4  399.63  5109.9  400.84  5124.6  401.74
  5134.6  401.61  5144.6  401.09  5154.6  401.88  5164.6  403.33  5204.6  405.01
  5254.6  407.75  5294.6  409.36  5304.6  410.04  5334.6  410.97  5364.6  413.12
#Mann=5,-1,0
  4549.8    0.16       0  4770.9    0.05       0  4775.6   0.033       0
  4781.6    0.05       0  5109.9    0.16       0
Bank Sta=4768.3,5097.4
Exp/Cntr=0.3,0.1

Chan Stop Cuts=-1