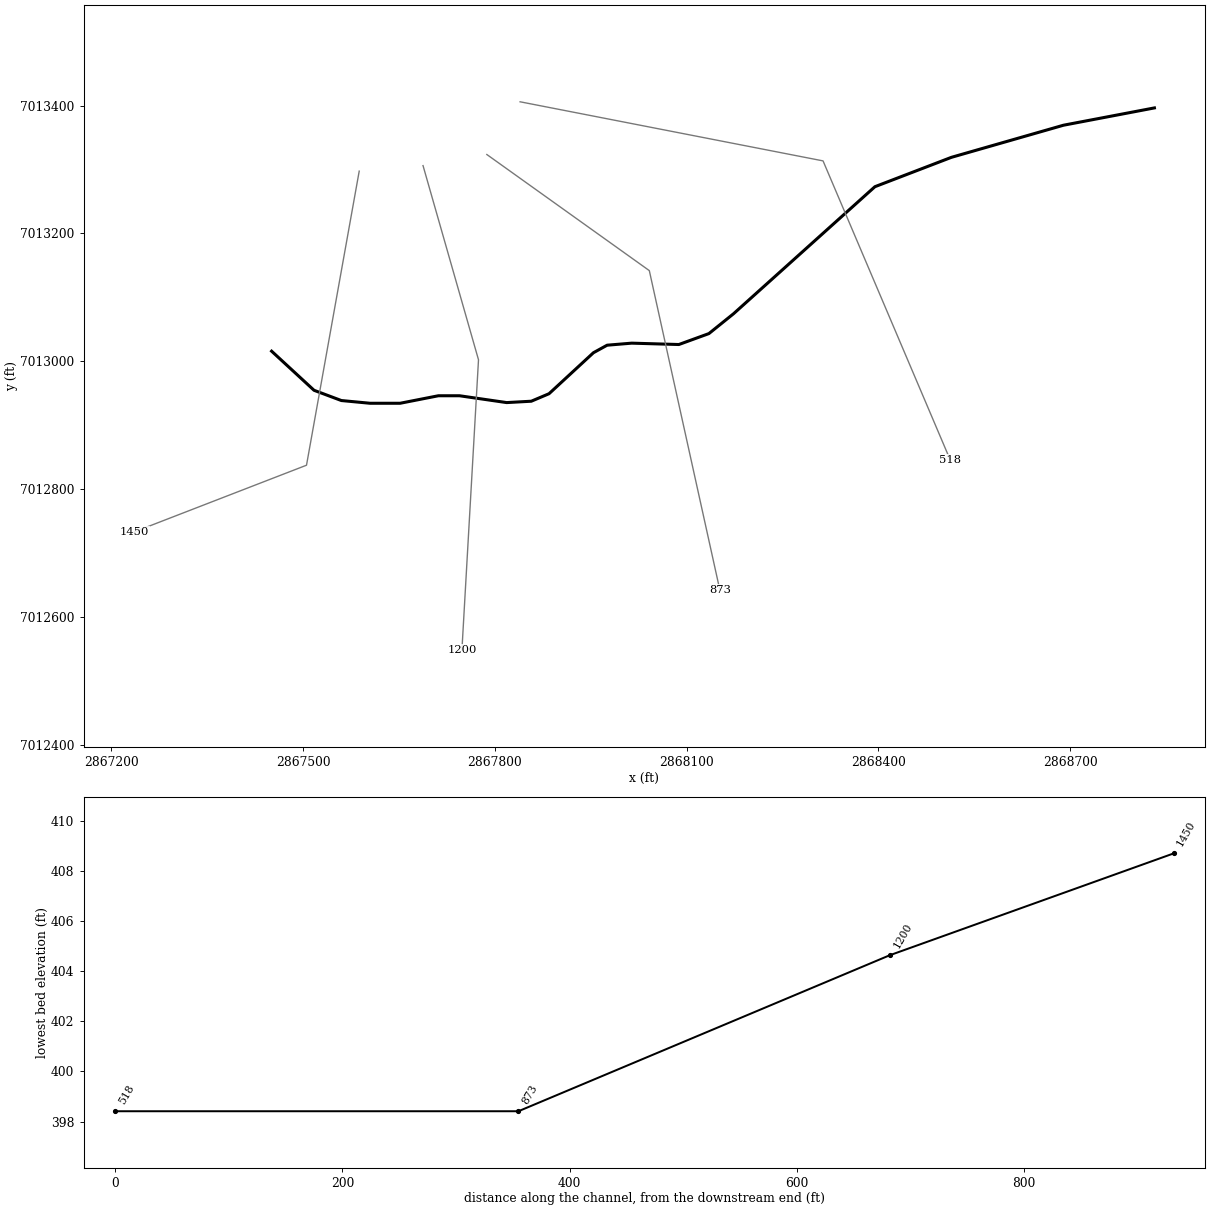
--- UNT 137 in Running Cr Watershed.prj (project) ---

Proj Title=UNT 137 in Running Cr Watershed Base Level Engineering
Current Plan=p01
Default Exp/Contr=0.3,0.1
English Units
Geom File=g01
Flow File=f01
Plan File=p01
BEGIN DESCRIPTION:
UNT 137 in Running Cr Watershed
END DESCRIPTION:

--- UNT 137 in Running Cr Watershed.p01 (plan) ---

Plan Title=Multiple Run
Short Identifier=Multiple
Geom File=g01
Flow File=f01
Subcritical Flow
K Sum by GR= 0
Std Step Tol= 0.01
Critical Tol= 0.01
Num of Std Step Trials= 20
Max Error Tol= 0.3
Flow Tol Ratio= 0.001
Split Flow NTrial= 30
Split Flow Tol= 0.02
Split Flow Ratio= 0.02
Log Output Level= 0
Friction Slope Method= 1
Unsteady Friction Slope Method= 2
Unsteady Bridges Friction Slope Method= 1
Parabolic Critical Depth
Global Vel Dist=  1 , 1 , 1
Global Log Level= 0
CheckData=True
Encroach Param= -1, 0, 0, 0
BEGIN DESCRIPTION:
Multiple Run
END DESCRIPTION:

--- UNT 137 in Running Cr Watershed.f01 (steady flow) ---

Flow Title=Multiple
Number of Profiles=7
Profile Names=10-year,25-year,50-year,1pct_min,100-year,1pct_plu,500-year
River Rch & RM= UNT 137 in Runni,Reach-1,1450
     174     216     247     142     282     563     367
Boundary for River Rch & Prof#=UNT 137 in Runni,Reach-1,1
Up Type=0
Dn Type=3
Dn Slope=0.005
Boundary for River Rch & Prof#=UNT 137 in Runni,Reach-1,2
Up Type=0
Dn Type=3
Dn Slope=0.005
Boundary for River Rch & Prof#=UNT 137 in Runni,Reach-1,3
Up Type=0
Dn Type=3
Dn Slope=0.005
Boundary for River Rch & Prof#=UNT 137 in Runni,Reach-1,4
Up Type=0
Dn Type=3
Dn Slope=0.005
Boundary for River Rch & Prof#=UNT 137 in Runni,Reach-1,5
Up Type=0
Dn Type=3
Dn Slope=0.005
Boundary for River Rch & Prof#=UNT 137 in Runni,Reach-1,6
Up Type=0
Dn Type=3
Dn Slope=0.005
Boundary for River Rch & Prof#=UNT 137 in Runni,Reach-1,7
Up Type=0
Dn Type=3
Dn Slope=0.005

--- UNT 137 in Running Cr Watershed.g01 (geometry) ---

Geom Title=Existing Conditions

River Reach=UNT 137 in Runni,Reach-1
Reach XY= 20
      2867450.59      7013015.71      2867516.99      7012954.49
      2867559.74      7012938.46      2867604.64      7012934.19
      2867651.66      7012934.19      2867711.52      7012945.94
      2867744.65      7012945.94      2867818.40      7012935.25
      2867856.88      7012937.39      2867884.67      7012949.15
      2867954.14      7013013.28      2867975.52      7013025.04
      2868014.00      7013028.24      2868087.75      7013026.10
      2868134.78      7013043.21      2868173.25      7013074.20
      2868394.50      7013273.01      2868514.21      7013318.97
      2868689.50      7013369.20      2868831.80      7013396.28

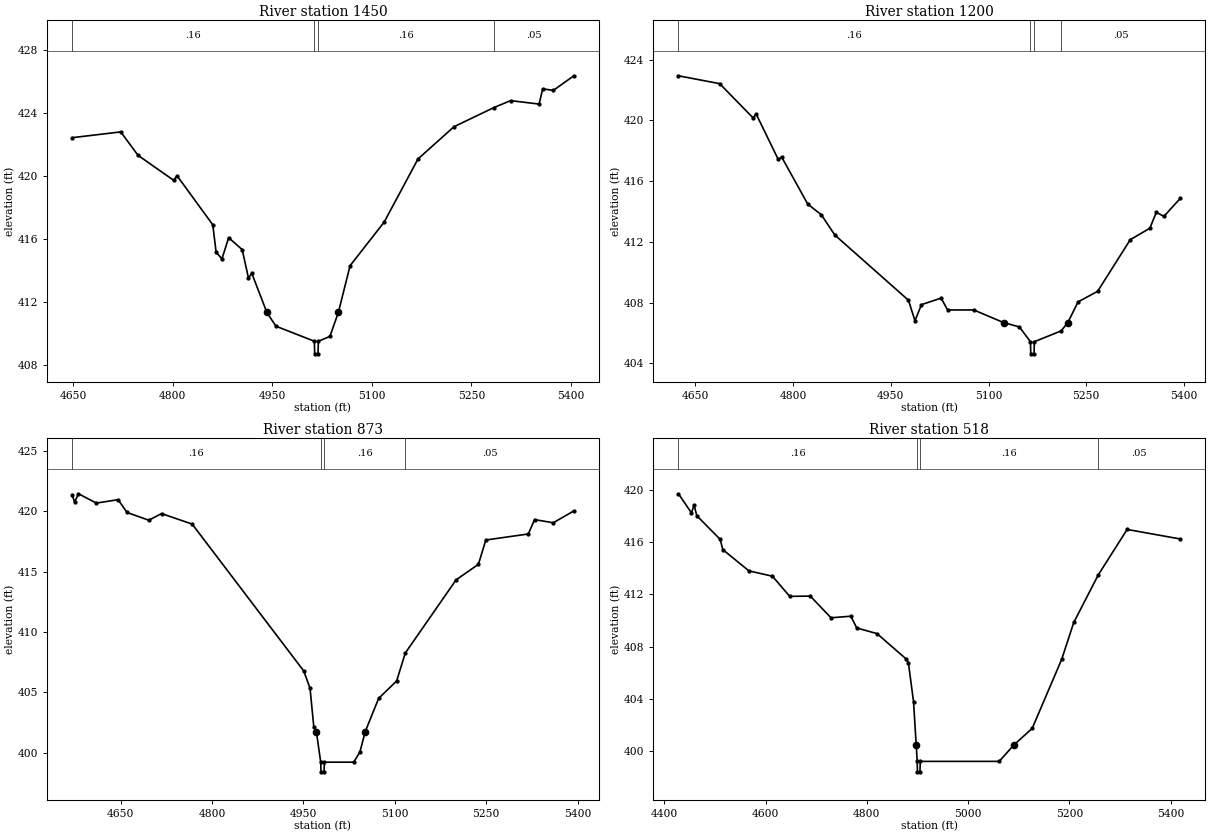
Type RM Length L Ch R = 1,1450,250,250,250
BEGIN DESCRIPTION:
UNT 137 in Running Cr Watershed 4.0
END DESCRIPTION:
XS GIS Cut Line= 3
      2867587.67      7013297.34      2867505.20      7012837.27
      2867236.15      7012733.13
#Sta/Elev= 30
  4648.4  422.44  4721.9  422.81  4747.9  421.32  4801.6  419.73  4806.7  420.02
  4860.5  416.90  4865.5  415.16  4874.3  414.73  4884.4  416.08  4904.8  415.32
  4914.2  413.52  4919.3  413.81  4942.0  411.32  4955.6  410.45  5013.5  409.49
  5014.0  408.69  5019.0  408.69  5019.5  409.49  5036.9  409.80  5049.6  411.32
  5067.3  414.30  5118.6  417.07  5169.6  421.09  5223.8  423.14  5284.0  424.36
  5309.0  424.80  5351.9  424.58  5357.4  425.55  5373.4  425.45  5404.3  426.38
#Mann=4,-1,0
  4648.4    0.16       0  5013.5    0.07       0  5019.5    0.16       0
  5284.0    0.05       0
Bank Sta=4942,5049.6
Exp/Cntr=0.3,0.1

Type RM Length L Ch R = 1,1200,327,327,327
BEGIN DESCRIPTION:
UNT 137 in Running Cr Watershed 3.0
END DESCRIPTION:
XS GIS Cut Line= 3
      2867687.51      7013305.99      2867774.30      7013002.21
      2867748.36      7012548.29
#Sta/Elev= 30
  4623.9  422.94  4687.3  422.42  4738.2  420.18  4743.4  420.41  4777.2  417.43
  4782.4  417.59  4822.5  414.49  4843.3  413.79  4864.1  412.45  4977.1  408.16
  4987.1  406.81  4997.1  407.87  5027.2  408.30  5037.2  407.52  5077.3  407.52
  5123.1  406.69  5147.4  406.40  5164.4  405.43  5164.9  404.63  5169.9  404.63
  5170.4  405.43  5211.5  406.14  5221.8  406.69  5237.5  408.05  5267.6  408.75
  5317.7  412.15  5347.7  412.90  5357.7  413.95  5369.3  413.68  5394.5  414.87
#Mann=4,-1,0
  4623.9    0.16       0  5164.4    0.07       0  5170.4    0.16       0
  5211.5    0.05       0
Bank Sta=5123.1,5221.8
Exp/Cntr=0.3,0.1

Type RM Length L Ch R = 1,873,355,355,355
BEGIN DESCRIPTION:
UNT 137 in Running Cr Watershed 2.0
END DESCRIPTION:
XS GIS Cut Line= 3
      2867787.36      7013323.36      2868041.54      7013141.73
      2868151.90      7012641.98
#Sta/Elev= 30
  4569.8  421.36  4574.3  420.76  4580.5  421.44  4609.9  420.67  4645.6  420.95
  4660.3  419.89  4696.0  419.25  4716.9  419.80  4767.2  418.93  4950.5  406.76
  4960.8  405.32  4966.9  402.16  4971.2  401.73  4978.3  399.21  4978.8  398.41
  4983.8  398.41  4984.3  399.21  5032.5  399.21  5042.7  400.05  5051.3  401.73
  5073.4  404.49  5103.0  405.94  5117.2  408.25  5200.6  414.31  5237.3  415.60
  5249.4  417.61  5319.2  418.11  5329.5  419.30  5360.2  419.04  5394.0  420.02
#Mann=4,-1,0
  4569.8    0.16       0  4978.3    0.07       0  4984.3    0.16       0
  5117.2    0.05       0
Bank Sta=4971.2,5051.3
Exp/Cntr=0.3,0.1

Type RM Length L Ch R = 1,518,0,0,0
BEGIN DESCRIPTION:
UNT 137 in Running Cr Watershed 1.0
END DESCRIPTION:
XS GIS Cut Line= 3
      2867839.38      7013405.86      2868313.35      7013313.40
      2868512.16      7012845.93
#Sta/Elev= 30
  4428.0  419.69  4453.8  418.23  4458.9  418.83  4464.3  418.01  4510.5  416.20
  4515.6  415.42  4567.2  413.79  4613.7  413.38  4647.7  411.84  4688.4  411.86
  4729.2  410.20  4768.4  410.32  4780.1  409.42  4820.0  408.99  4876.7  407.08
  4882.0  406.77  4892.2  403.78  4897.5  400.44  4899.4  399.21  4899.9  398.41
  4904.9  398.41  4905.4  399.21  5061.3  399.21  5089.6  400.44  5126.5  401.74
  5184.8  407.03  5208.5  409.84  5256.9  413.48  5313.9  416.96  5418.9  416.23
#Mann=4,-1,0
  4428.0    0.16       0  4899.4    0.07       0  4905.4    0.16       0
  5256.9    0.05       0
Bank Sta=4897.5,5089.6
Exp/Cntr=0.3,0.1

Chan Stop Cuts=-1