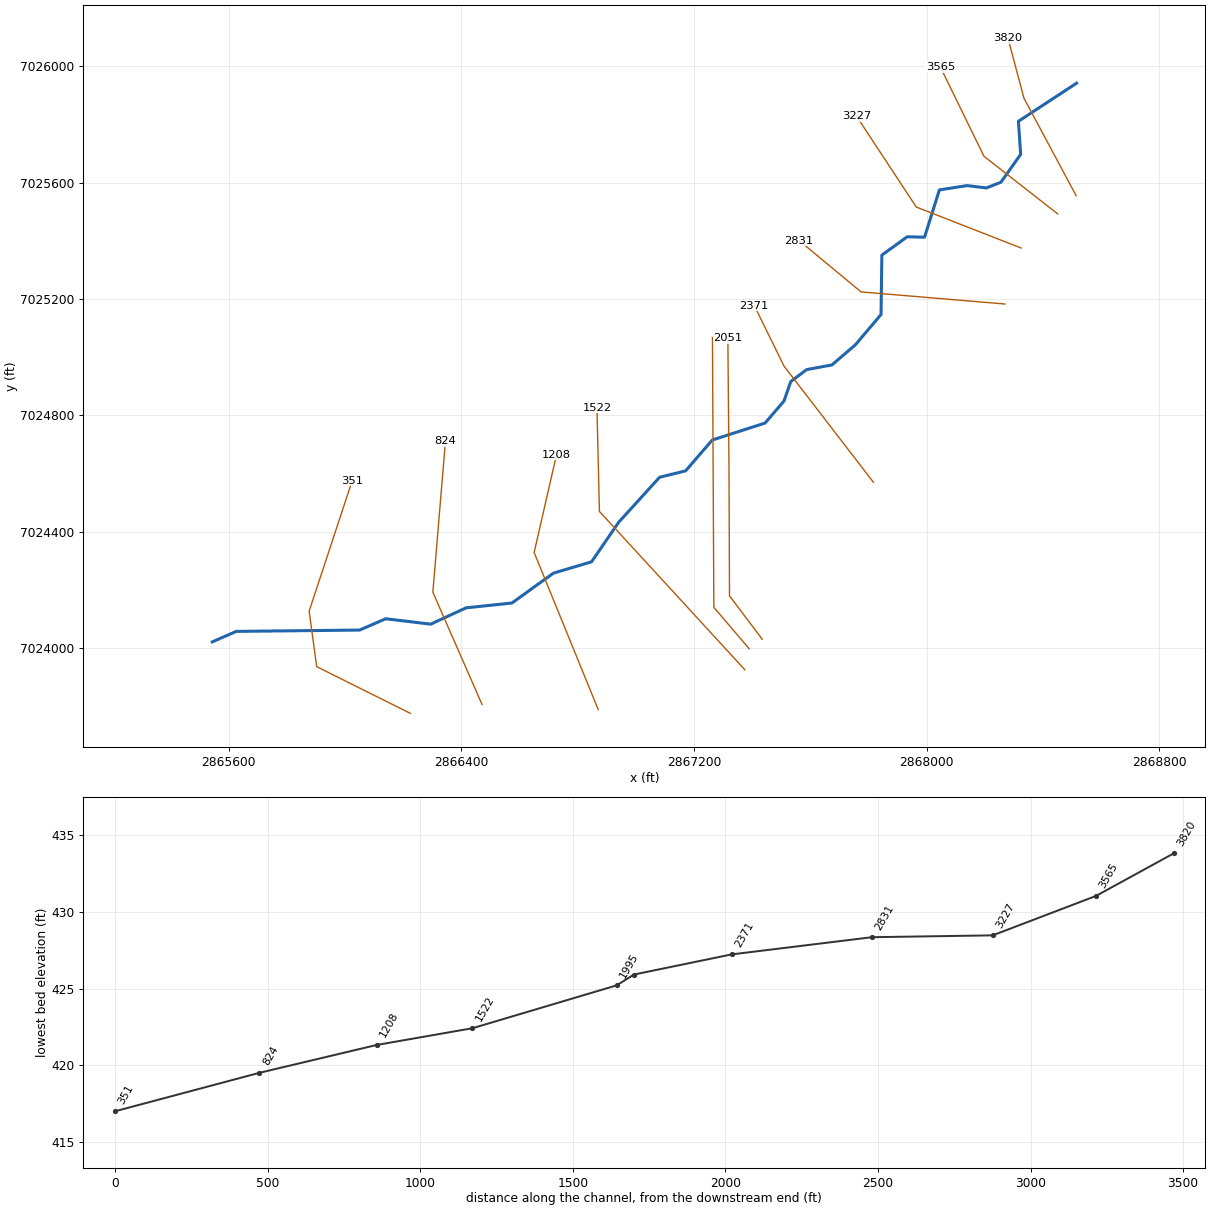
--- UNT 138 in Running Cr Watershed.prj (project) ---

Proj Title=UNT 138 in Running Cr Watershed Base Level Engineering
Current Plan=p01
Default Exp/Contr=0.3,0.1
English Units
Geom File=g01
Flow File=f01
Plan File=p01
BEGIN DESCRIPTION:
UNT 138 in Running Cr Watershed
END DESCRIPTION:

--- UNT 138 in Running Cr Watershed.p01 (plan) ---

Plan Title=Multiple Run
Short Identifier=Multiple
Geom File=g01
Flow File=f01
Subcritical Flow
K Sum by GR= 0
Std Step Tol= 0.01
Critical Tol= 0.01
Num of Std Step Trials= 20
Max Error Tol= 0.3
Flow Tol Ratio= 0.001
Split Flow NTrial= 30
Split Flow Tol= 0.02
Split Flow Ratio= 0.02
Log Output Level= 0
Friction Slope Method= 1
Unsteady Friction Slope Method= 2
Unsteady Bridges Friction Slope Method= 1
Parabolic Critical Depth
Global Vel Dist=  1 , 1 , 1
Global Log Level= 0
CheckData=True
Encroach Param= -1, 0, 0, 0
BEGIN DESCRIPTION:
Multiple Run
END DESCRIPTION:

--- UNT 138 in Running Cr Watershed.f01 (steady flow) ---

Flow Title=Multiple
Number of Profiles=7
Profile Names=10-year,25-year,50-year,1pct_min,100-year,1pct_plu,500-year
River Rch & RM= UNT 138 in Runni,Reach-1,3820
     349     451     531     312     622    1241     853
Boundary for River Rch & Prof#=UNT 138 in Runni,Reach-1,1
Up Type=0
Dn Type=3
Dn Slope=0.005
Boundary for River Rch & Prof#=UNT 138 in Runni,Reach-1,2
Up Type=0
Dn Type=3
Dn Slope=0.005
Boundary for River Rch & Prof#=UNT 138 in Runni,Reach-1,3
Up Type=0
Dn Type=3
Dn Slope=0.005
Boundary for River Rch & Prof#=UNT 138 in Runni,Reach-1,4
Up Type=0
Dn Type=3
Dn Slope=0.005
Boundary for River Rch & Prof#=UNT 138 in Runni,Reach-1,5
Up Type=0
Dn Type=3
Dn Slope=0.005
Boundary for River Rch & Prof#=UNT 138 in Runni,Reach-1,6
Up Type=0
Dn Type=3
Dn Slope=0.005
Boundary for River Rch & Prof#=UNT 138 in Runni,Reach-1,7
Up Type=0
Dn Type=3
Dn Slope=0.005

--- UNT 138 in Running Cr Watershed.g01 (geometry) ---

Geom Title=Existing Conditions

River Reach=UNT 138 in Runni,Reach-1
Reach XY= 30
      2868515.38      7025941.67      2868315.59      7025810.71
      2868323.37      7025697.03      2868255.41      7025601.17
      2868205.34      7025581.62      2868139.24      7025589.60
      2868043.95      7025574.85      2867992.81      7025412.24
      2867933.33      7025413.67      2867846.09      7025350.56
      2867843.31      7025146.48      2867754.58      7025041.71
      2867674.62      7024973.08      2867587.09      7024956.91
      2867532.85      7024915.88      2867509.46      7024848.76
      2867444.59      7024773.18      2867263.02      7024714.87
      2867171.34      7024608.86      2867081.85      7024586.80
      2866941.17      7024432.11      2866848.00      7024296.12
      2866717.03      7024257.22      2866574.06      7024154.40
      2866416.76      7024137.89      2866294.94      7024081.76
      2866140.13      7024100.28      2866050.74      7024061.44
      2865626.26      7024056.88      2865544.01      7024020.82

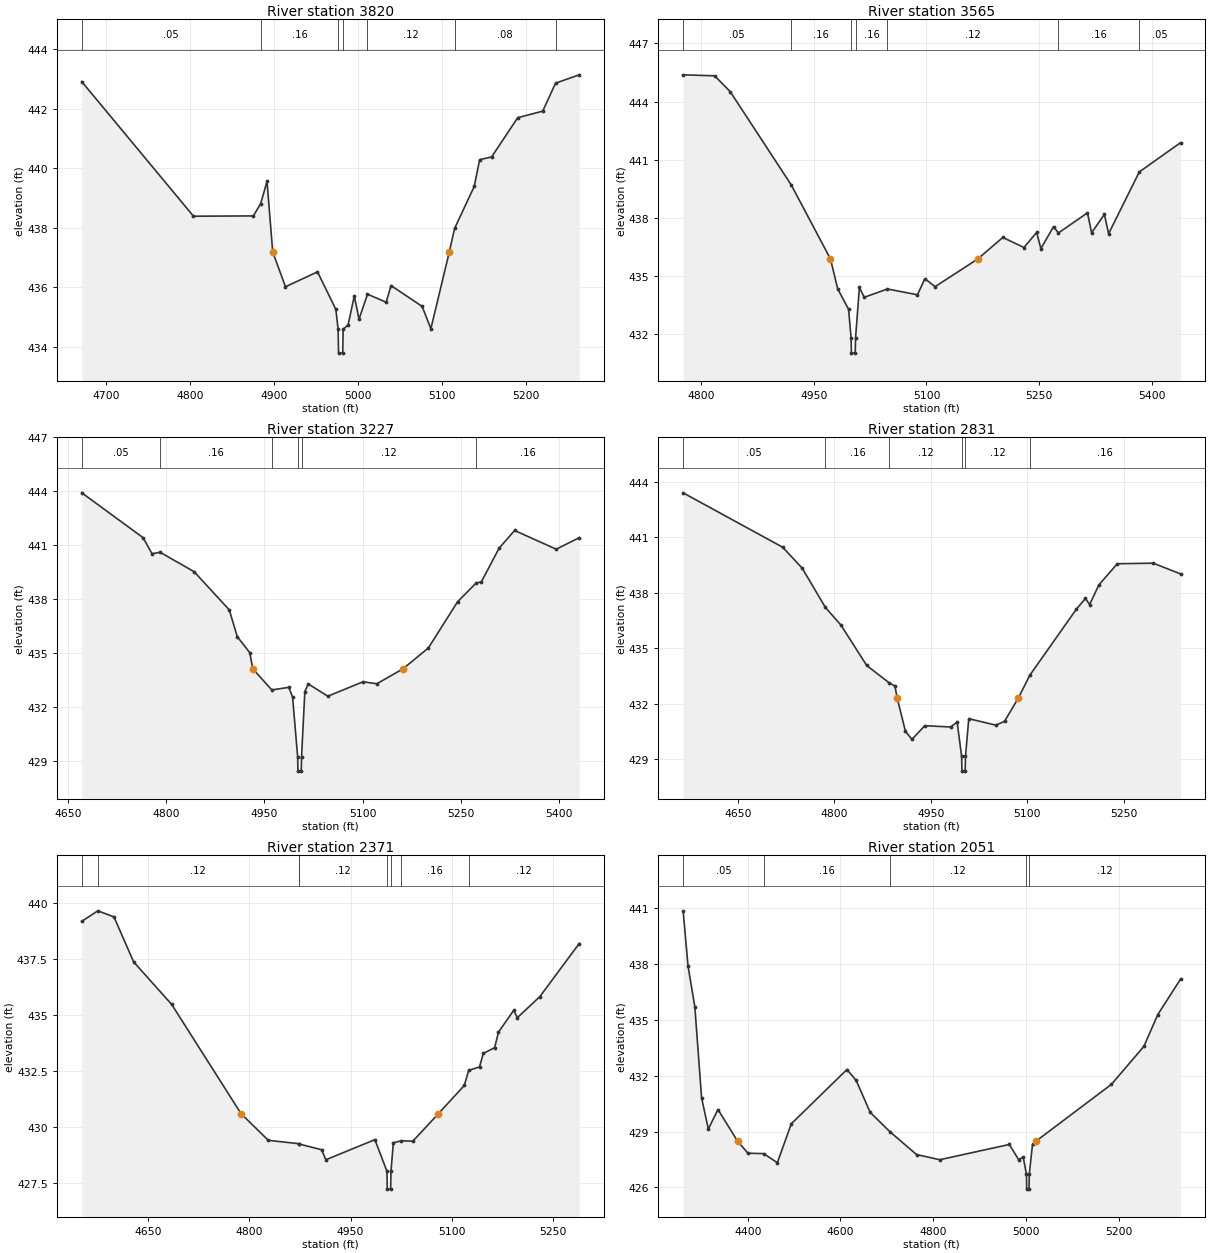
Type RM Length L Ch R = 1,3820,255,255,255
BEGIN DESCRIPTION:
UNT 138 in Running Cr Watershed 10.0
END DESCRIPTION:
XS GIS Cut Line= 3
      2868514.06      7025554.93      2868334.39      7025890.83
      2868279.86      7026095.97
#Sta/Elev= 30
  4670.8  442.91  4804.0  438.39  4875.4  438.40  4884.1  438.81  4891.7  439.56
  4898.5  437.19  4913.7  436.02  4951.9  436.52  4973.8  435.26  4976.5  434.59
  4977.0  433.79  4982.0  433.79  4982.5  434.59  4988.4  434.74  4995.8  435.71
  5001.4  434.93  5011.5  435.77  5033.8  435.50  5039.6  436.06  5076.7  435.36
  5087.1  434.61  5109.1  437.19  5115.4  437.98  5138.8  439.39  5145.3  440.29
  5159.5  440.38  5190.7  441.70  5220.5  441.92  5235.8  442.86  5264.0  443.14
#Mann=7,-1,0
  4670.8    0.05       0  4884.1    0.16       0  4976.5    0.07       0
  4982.5    0.16       0  5011.5    0.12       0  5115.4    0.08       0
  5235.8    0.05       0
Bank Sta=4898.5,5109.1
Exp/Cntr=0.3,0.1

Type RM Length L Ch R = 1,3565,338,338,338
BEGIN DESCRIPTION:
Mapping XS 3c606411
END DESCRIPTION:
XS GIS Cut Line= 3
      2868450.69      7025492.40      2868197.23      7025690.31
      2868047.91      7025995.91
#Sta/Elev= 30
  4776.3  445.38  4818.2  445.33  4839.0  444.51  4920.1  439.70  4972.3  435.88
  4981.9  434.34  4996.4  433.28  4999.7  431.82  5000.2  431.02  5005.2  431.02
  5005.7  431.82  5010.8  434.41  5017.2  433.90  5048.1  434.33  5088.0  434.03
  5097.9  434.86  5111.5  434.45  5168.3  435.88  5201.6  436.99  5229.7  436.47
  5246.6  437.25  5252.2  436.41  5269.1  437.55  5275.5  437.22  5314.2  438.26
  5319.7  437.23  5336.7  438.18  5342.3  437.18  5383.1  440.37  5438.0  441.88
#Mann=7,-1,0
  4776.3    0.05       0  4920.1    0.16       0  4999.7    0.07       0
  5005.7    0.16       0  5048.1    0.12       0  5275.5    0.16       0
  5383.1    0.05       0
Bank Sta=4972.3,5168.3
Exp/Cntr=0.3,0.1

Type RM Length L Ch R = 1,3227,396,396,396
BEGIN DESCRIPTION:
UNT 138 in Running Cr Watershed 9.0
END DESCRIPTION:
XS GIS Cut Line= 3
      2868324.96      7025375.01      2867964.60      7025515.83
      2867759.44      7025827.46
#Sta/Elev= 30
  4671.1  443.91  4764.8  441.42  4778.4  440.53  4790.8  440.61  4842.8  439.53
  4896.5  437.41  4908.6  435.93  4927.7  435.04  4932.4  434.14  4961.4  432.97
  4987.4  433.11  4993.2  432.57  5000.9  429.26  5001.4  428.46  5006.4  428.46
  5006.9  429.26  5011.9  432.88  5017.2  433.30  5047.1  432.62  5100.8  433.42
  5121.9  433.31  5161.9  434.14  5200.7  435.30  5245.4  437.87  5273.9  438.91
  5281.5  438.96  5308.6  440.83  5332.4  441.82  5396.0  440.78  5431.1  441.42
#Mann=6,-1,0
  4671.1    0.05       0  4790.8    0.16       0  4961.4    0.12       0
  5000.9    0.07       0  5006.9    0.12       0  5273.9    0.16       0
Bank Sta=4932.4,5161.9
Exp/Cntr=0.3,0.1

Type RM Length L Ch R = 1,2831,460,460,460
BEGIN DESCRIPTION:
UNT 138 in Running Cr Watershed 8.0
END DESCRIPTION:
XS GIS Cut Line= 3
      2868269.31      7025182.50      2867774.49      7025224.17
      2867561.71      7025400.62
#Sta/Elev= 30
  4565.1  443.41  4720.0  440.46  4750.1  439.33  4786.1  437.21  4810.3  436.25
  4850.4  434.06  4885.7  433.11  4894.2  432.95  4897.7  432.31  4910.6  430.49
  4920.7  430.06  4940.7  430.80  4980.9  430.73  4990.9  431.00  4997.9  429.14
  4998.4  428.34  5003.4  428.34  5003.9  429.14  5009.0  431.18  5051.1  430.83
  5064.6  431.04  5086.2  432.31  5104.0  433.54  5176.0  437.10  5190.3  437.69
  5196.8  437.36  5211.1  438.42  5239.8  439.57  5295.7  439.60  5338.1  439.02
#Mann=6,-1,0
  4565.1    0.05       0  4786.1    0.16       0  4885.7    0.12       0
  4997.9    0.07       0  5003.9    0.12       0  5104.0    0.16       0
Bank Sta=4897.7,5086.2
Exp/Cntr=0.3,0.1

Type RM Length L Ch R = 1,2371,320,320,320
BEGIN DESCRIPTION:
UNT 138 in Running Cr Watershed 7.0
END DESCRIPTION:
XS GIS Cut Line= 3
      2867817.04      7024569.63      2867509.73      7024968.96
      2867407.32      7025177.26
#Sta/Elev= 30
  4552.4  439.18  4576.1  439.65  4600.0  439.38  4629.1  437.37  4685.4  435.47
  4788.1  430.59  4828.4  429.40  4873.2  429.25  4873.4  429.24  4907.2  428.98
  4913.5  428.53  4986.1  429.43  5003.9  428.02  5004.4  427.22  5009.4  427.22
  5009.9  428.02  5013.4  429.29  5025.0  429.38  5042.2  429.36  5080.1  430.59
  5118.4  431.85  5124.8  432.52  5140.9  432.68  5146.5  433.28  5163.3  433.54
  5168.9  434.23  5191.4  435.20  5197.0  434.88  5230.2  435.82  5288.4  438.19
#Mann=8,-1,0
  4552.4    0.16       0  4576.1    0.12       0  4873.2    0.16       0
  4873.4    0.12       0  5003.9    0.07       0  5009.9    0.12       0
  5025.0    0.16       0  5124.8    0.12       0
Bank Sta=4788.1,5080.1
Exp/Cntr=0.3,0.1

Type RM Length L Ch R = 1,2051,56,56,56
BEGIN DESCRIPTION:
UNT 138 in Running Cr Watershed 6.0
END DESCRIPTION:
XS GIS Cut Line= 4
      2867435.07      7024029.74      2867322.23      7024179.03
      2867320.50      7024620.00      2867316.60      7025064.07
#Sta/Elev= 30
  4260.8  440.87  4271.4  437.90  4286.0  435.72  4300.6  430.82  4315.1  429.14
  4335.9  430.19  4378.1  428.49  4400.5  427.84  4434.3  427.82  4463.9  427.33
  4493.9  429.42  4613.9  432.34  4633.9  431.75  4663.9  430.04  4706.8  428.99
  4763.9  427.77  4813.9  427.49  4963.9  428.31  4983.9  427.50  4993.9  427.63
  5000.9  426.71  5001.4  425.91  5006.4  425.91  5006.9  426.71  5013.9  428.31
  5021.5  428.49  5183.9  431.54  5253.9  433.58  5283.9  435.29  5333.0  437.20
#Mann=5,-1,0
  4260.8    0.05       0  4434.3    0.16       0  4706.8    0.12       0
  5000.9    0.07       0  5006.9    0.12       0
Bank Sta=4378.1,5021.5
Exp/Cntr=0.3,0.1

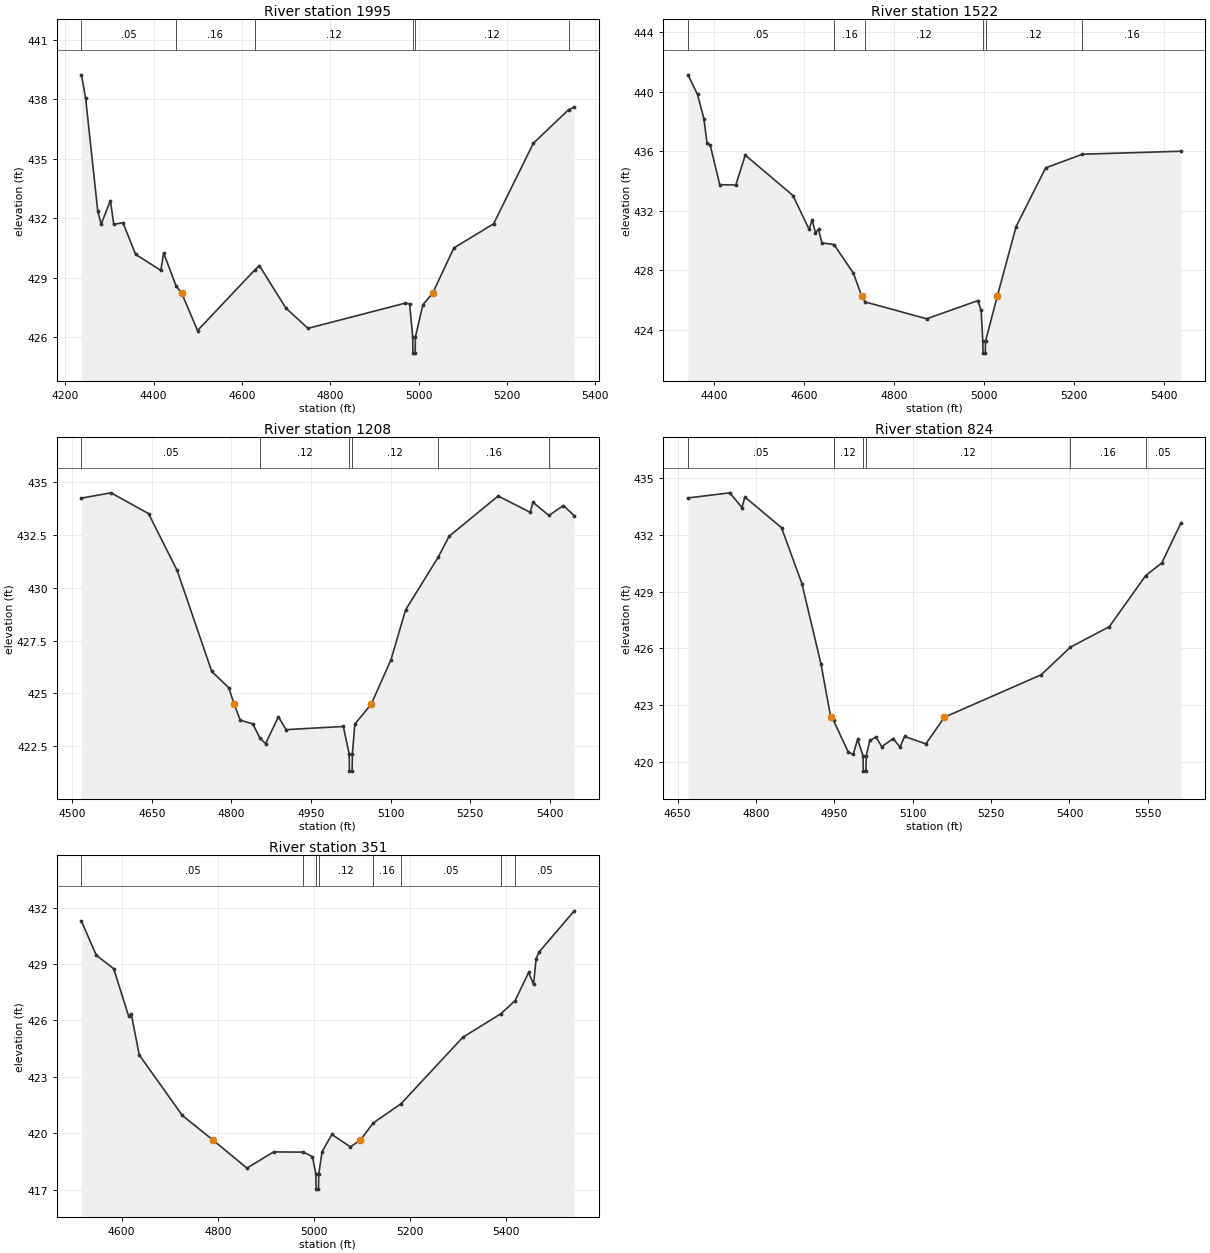
Type RM Length L Ch R = 1,1995,473,473,473
BEGIN DESCRIPTION:
UNT 138 in Running Cr Watershed 5.0
END DESCRIPTION:
XS GIS Cut Line= 3
      2867389.95      7023997.16      2867268.41      7024139.53
      2867263.64      7025067.52
#Sta/Elev= 30
  4236.9  439.24  4246.4  438.06  4273.9  432.36  4281.6  431.71  4302.4  432.90
  4310.1  431.71  4331.0  431.78  4359.5  430.19  4416.6  429.38  4422.9  430.26
  4451.3  428.59  4463.8  428.23  4499.6  426.35  4628.7  429.39  4639.6  429.62
  4699.6  427.48  4749.6  426.46  4969.6  427.73  4979.6  427.69  4986.6  426.01
  4987.1  425.21  4992.1  425.21  4992.6  426.01  5009.6  427.65  5031.7  428.23
  5079.6  430.51  5169.6  431.73  5259.6  435.79  5339.2  437.48  5352.1  437.61
#Mann=6,-1,0
  4236.9    0.05       0  4451.3    0.16       0  4628.7    0.12       0
  4986.6    0.07       0  4992.6    0.12       0  5339.2    0.16       0
Bank Sta=4463.8,5031.7
Exp/Cntr=0.3,0.1

Type RM Length L Ch R = 1,1522,314,314,314
BEGIN DESCRIPTION:
UNT 138 in Running Cr Watershed 4.0
END DESCRIPTION:
XS GIS Cut Line= 3
      2867374.98      7023925.02      2866875.00      7024469.39
      2866866.51      7024825.25
#Sta/Elev= 30
  4342.1  441.14  4363.3  439.82  4377.5  438.18  4384.3  436.58  4391.7  436.39
  4412.7  433.75  4448.4  433.73  4469.4  435.74  4575.5  433.02  4611.2  430.75
  4618.0  431.38  4625.4  430.52  4632.2  430.75  4639.6  429.84  4666.7  429.72
  4709.9  427.79  4728.3  426.24  4736.2  425.86  4872.6  424.73  4986.1  425.95
  4993.5  425.31  4997.3  423.22  4997.8  422.42  5002.8  422.42  5003.3  423.22
  5029.4  426.24  5071.2  430.93  5136.9  434.88  5218.5  435.80  5437.2  436.00
#Mann=6,-1,0
  4342.1    0.05       0  4666.7    0.16       0  4736.2    0.12       0
  4997.3    0.07       0  5003.3    0.12       0  5218.5    0.16       0
Bank Sta=4728.3,5029.4
Exp/Cntr=0.3,0.1

Type RM Length L Ch R = 1,1208,384,384,384
BEGIN DESCRIPTION:
UNT 138 in Running Cr Watershed 3.0
END DESCRIPTION:
XS GIS Cut Line= 3
      2866870.85      7023787.96      2866650.53      7024328.16
      2866727.62      7024664.74
#Sta/Elev= 30
  4517.2  434.23  4572.9  434.48  4643.6  433.50  4697.6  430.81  4762.8  426.04
  4794.8  425.27  4804.9  424.50  4816.4  423.74  4840.3  423.56  4853.3  422.90
  4864.3  422.63  4888.4  423.90  4902.8  423.29  5010.8  423.44  5021.8  422.13
  5022.3  421.33  5027.3  421.33  5027.8  422.13  5032.4  423.55  5063.5  424.50
  5100.6  426.60  5128.1  428.95  5189.3  431.43  5210.2  432.43  5302.5  434.33
  5363.0  433.56  5368.1  434.03  5398.3  433.41  5425.6  433.88  5445.9  433.40
#Mann=6,-1,0
  4517.2    0.05       0  4853.3    0.12       0  5021.8    0.07       0
  5027.8    0.12       0  5189.3    0.16       0  5398.3    0.05       0
Bank Sta=4804.9,5063.5
Exp/Cntr=0.3,0.1

Type RM Length L Ch R = 1,824,473,473,473
BEGIN DESCRIPTION:
UNT 138 in Running Cr Watershed 2.0
END DESCRIPTION:
XS GIS Cut Line= 3
      2866471.53      7023805.34      2866302.27      7024191.61
      2866345.57      7024711.18
#Sta/Elev= 30
  4669.9  433.95  4749.9  434.22  4773.3  433.44  4778.8  434.00  4848.9  432.38
  4887.9  429.43  4924.5  425.17  4943.1  422.37  4948.4  422.20  4976.7  420.52
  4986.1  420.41  4994.6  421.20  5005.0  420.32  5005.5  419.52  5010.5  419.52
  5011.0  420.32  5018.0  421.14  5029.8  421.32  5040.7  420.81  5062.6  421.24
  5075.7  420.79  5084.4  421.35  5125.1  420.96  5160.8  422.37  5345.9  424.61
  5401.9  426.07  5476.3  427.15  5545.6  429.84  5576.7  430.52  5613.0  432.61
#Mann=6,-1,0
  4669.9    0.05       0  4948.4    0.12       0  5005.0    0.07       0
  5011.0    0.12       0  5401.9    0.16       0  5545.6    0.05       0
Bank Sta=4943.1,5160.8
Exp/Cntr=0.3,0.1

Type RM Length L Ch R = 1,351,0,0,0
BEGIN DESCRIPTION:
UNT 138 in Running Cr Watershed 1.0
END DESCRIPTION:
XS GIS Cut Line= 4
      2866225.04      7023774.98      2865902.96      7023935.54
      2865876.92      7024126.51      2866024.99      7024574.98
#Sta/Elev= 30
  4516.5  431.28  4547.3  429.47  4583.6  428.75  4614.5  426.24  4620.1  426.34
  4636.8  424.16  4726.4  420.94  4790.1  419.63  4860.7  418.14  4916.2  419.00
  4978.3  418.99  4996.9  418.75  5004.0  417.82  5004.5  417.02  5009.5  417.02
  5010.0  417.82  5017.1  419.02  5037.3  419.93  5075.9  419.27  5096.6  419.63
  5123.3  420.54  5181.0  421.56  5309.7  425.10  5388.7  426.35  5418.4  427.05
  5446.6  428.55  5456.8  427.91  5462.1  429.28  5467.7  429.62  5541.4  431.83
#Mann=8,-1,0
  4516.5    0.05       0  4978.3    0.12       0  5004.0    0.07       0
  5010.0    0.12       0  5123.3    0.16       0  5181.0    0.05       0
  5388.7    0.16       0  5418.4    0.05       0
Bank Sta=4790.1,5096.6
Exp/Cntr=0.3,0.1

Chan Stop Cuts=-1