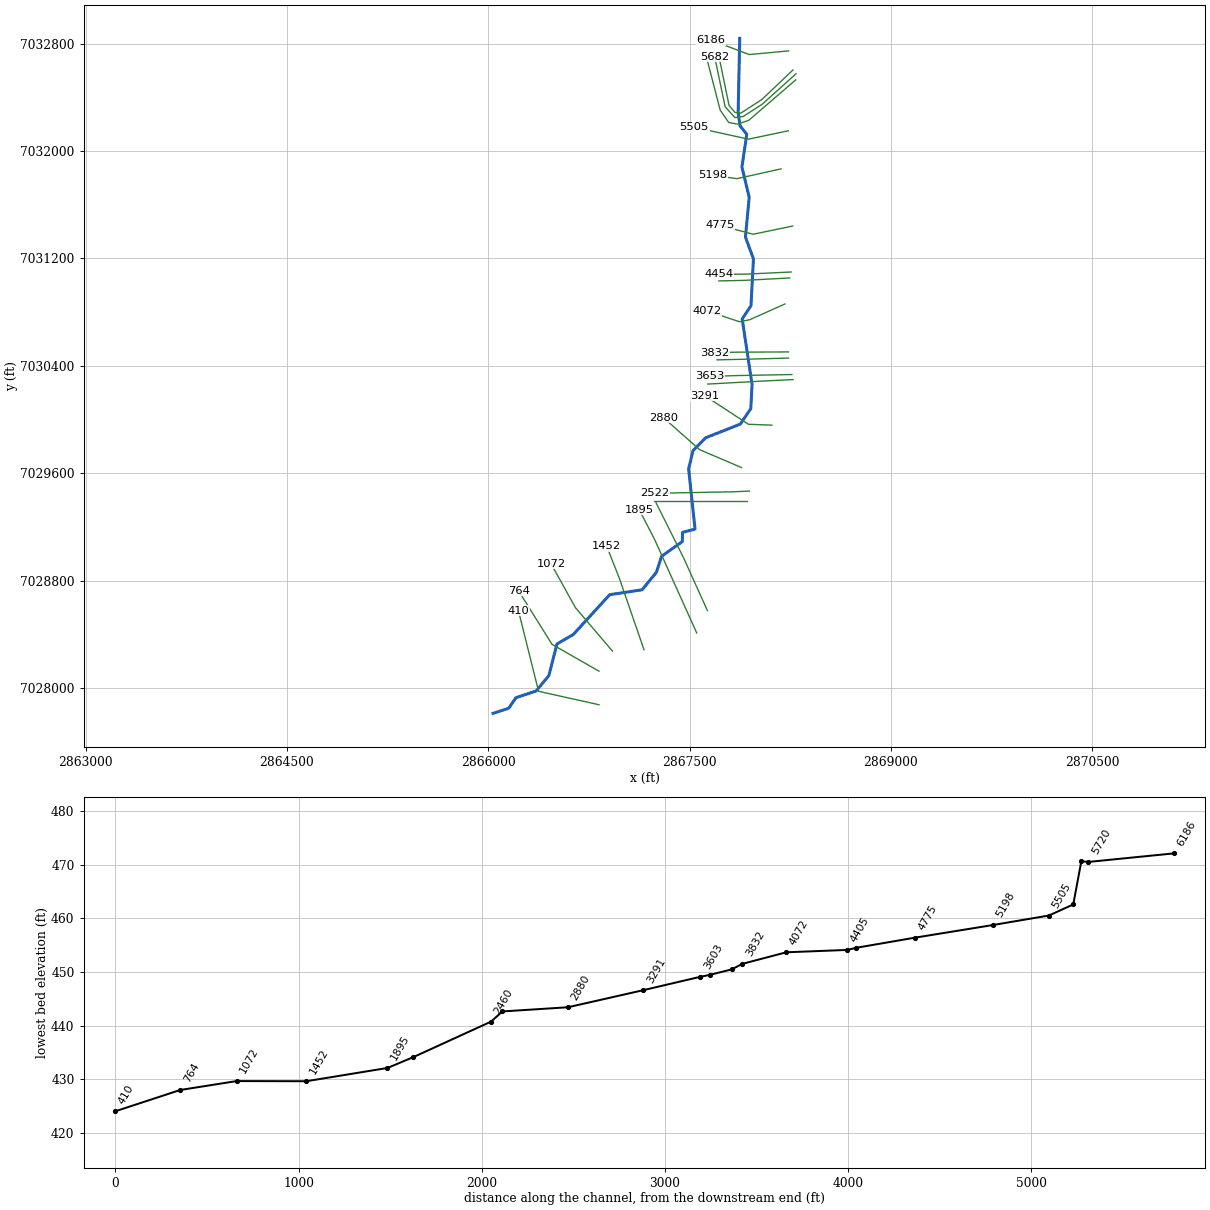
--- UNT 139 in Running Cr Watershed.prj (project) ---

Proj Title=UNT 139 in Running Cr Watershed Base Level Engineering
Current Plan=p01
Default Exp/Contr=0.3,0.1
English Units
Geom File=g01
Flow File=f01
Plan File=p01
BEGIN DESCRIPTION:
UNT 139 in Running Cr Watershed
END DESCRIPTION:

--- UNT 139 in Running Cr Watershed.p01 (plan) ---

Plan Title=Multiple Run
Short Identifier=Multiple
Geom File=g01
Flow File=f01
Subcritical Flow
K Sum by GR= 0
Std Step Tol= 0.01
Critical Tol= 0.01
Num of Std Step Trials= 20
Max Error Tol= 0.3
Flow Tol Ratio= 0.001
Split Flow NTrial= 30
Split Flow Tol= 0.02
Split Flow Ratio= 0.02
Log Output Level= 0
Friction Slope Method= 1
Unsteady Friction Slope Method= 2
Unsteady Bridges Friction Slope Method= 1
Parabolic Critical Depth
Global Vel Dist=  1 , 1 , 1
Global Log Level= 0
CheckData=True
Encroach Param= -1, 0, 0, 0
BEGIN DESCRIPTION:
Multiple Run
END DESCRIPTION:

--- UNT 139 in Running Cr Watershed.f01 (steady flow) ---

Flow Title=Multiple
Number of Profiles=7
Profile Names=10-year,25-year,50-year,1pct_min,100-year,1pct_plu,500-year
River Rch & RM= UNT 139 in Runni,Reach-1,6186
     356     463     547     323     644    1284     890
River Rch & RM= UNT 139 in Runni,Reach-1,1452
     374     487     577     340     678    1354     940
Boundary for River Rch & Prof#=UNT 139 in Runni,Reach-1,1
Up Type=0
Dn Type=3
Dn Slope=0.005
Boundary for River Rch & Prof#=UNT 139 in Runni,Reach-1,2
Up Type=0
Dn Type=3
Dn Slope=0.005
Boundary for River Rch & Prof#=UNT 139 in Runni,Reach-1,3
Up Type=0
Dn Type=3
Dn Slope=0.005
Boundary for River Rch & Prof#=UNT 139 in Runni,Reach-1,4
Up Type=0
Dn Type=3
Dn Slope=0.005
Boundary for River Rch & Prof#=UNT 139 in Runni,Reach-1,5
Up Type=0
Dn Type=3
Dn Slope=0.005
Boundary for River Rch & Prof#=UNT 139 in Runni,Reach-1,6
Up Type=0
Dn Type=3
Dn Slope=0.005
Boundary for River Rch & Prof#=UNT 139 in Runni,Reach-1,7
Up Type=0
Dn Type=3
Dn Slope=0.005

--- UNT 139 in Running Cr Watershed.g01 (geometry) ---

Geom Title=Existing Conditions

River Reach=UNT 139 in Runni,Reach-1
Reach XY= 30
      2867873.35      7032839.63      2867861.54      7032286.86
      2867875.43      7032188.24      2867925.88      7032124.67
      2867889.72      7031881.48      2867943.95      7031655.68
      2867915.92      7031359.09      2867975.57      7031196.45
      2867957.36      7030847.74      2867891.67      7030749.38
      2867965.22      7030261.63      2867955.59      7030080.71
      2867878.03      7029966.07      2867619.67      7029863.76
      2867525.34      7029768.28      2867492.74      7029632.03
      2867540.48      7029183.71      2867447.32      7029159.26
      2867445.77      7029090.64      2867291.28      7028981.09
      2867252.85      7028862.10      2867145.87      7028731.43
      2866904.48      7028694.65      2866633.07      7028398.02
      2866511.80      7028327.71      2866451.31      7028092.13
      2866356.30      7027977.16      2866206.80      7027927.62
      2866151.85      7027848.75      2866035.59      7027810.71

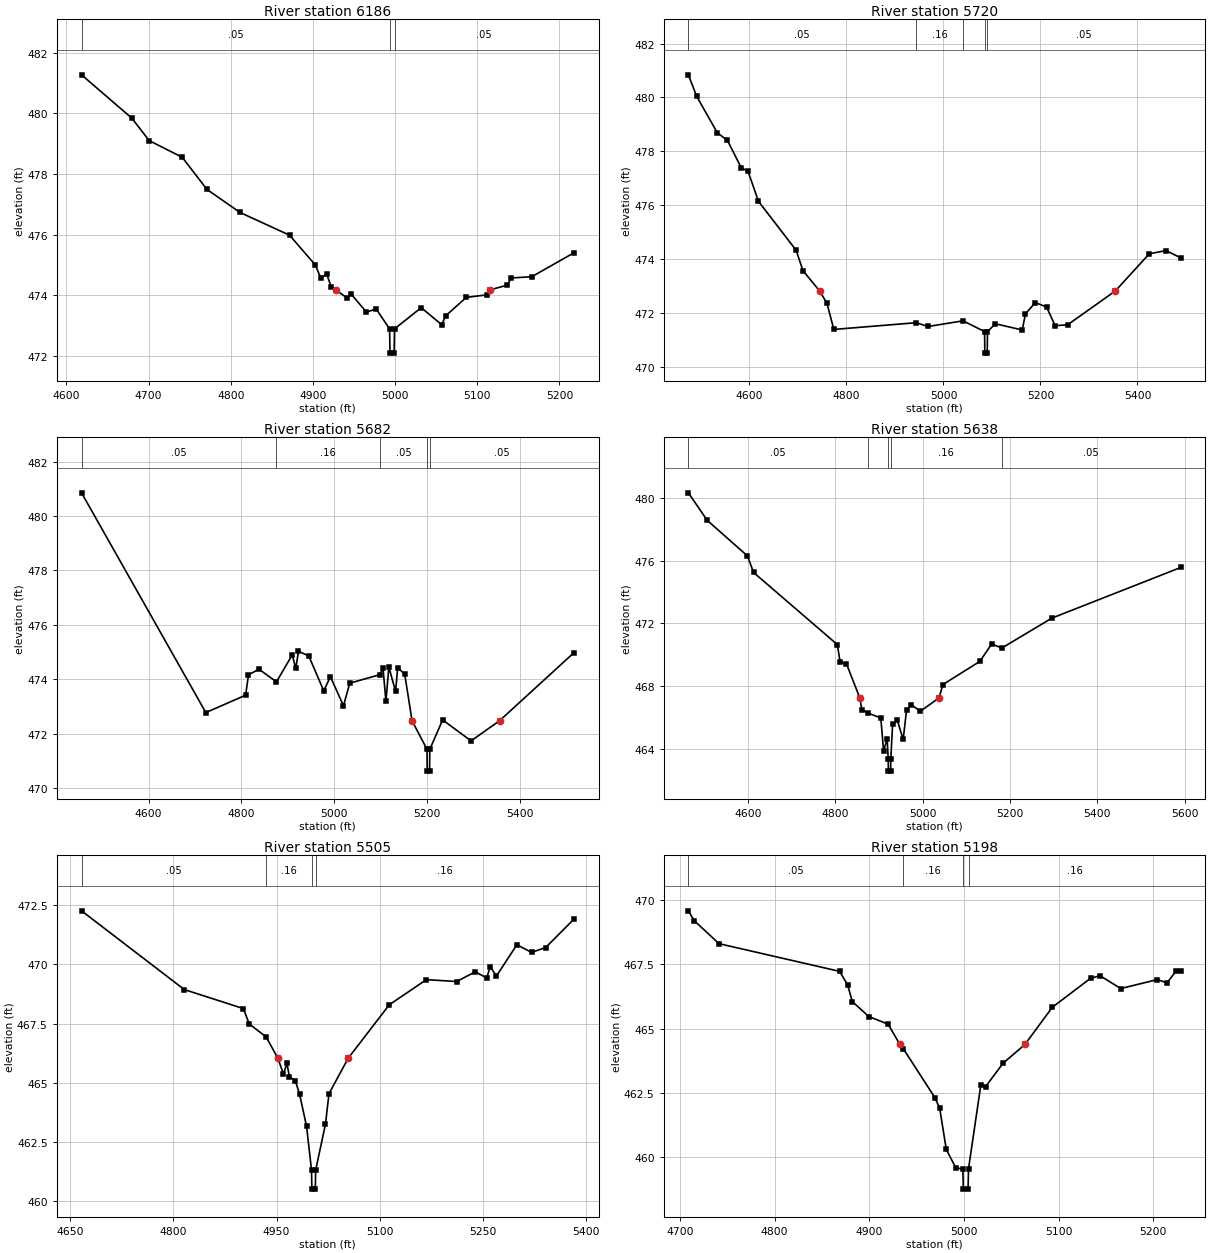
Type RM Length L Ch R = 1,6186,466,466,466
BEGIN DESCRIPTION:
UNT 139 in Running Cr Watershed 16.0
END DESCRIPTION:
XS GIS Cut Line= 3
      2868236.98      7032746.07      2867943.99      7032718.72
      2867659.07      7032827.11
#Sta/Elev= 30
  4618.5  481.27  4679.7  479.84  4700.8  479.10  4741.0  478.55  4771.1  477.49
  4811.3  476.73  4871.6  475.98  4902.9  475.00  4909.7  474.56  4916.7  474.71
  4922.4  474.26  4927.7  474.18  4941.5  473.91  4946.8  474.03  4965.2  473.44
  4976.9  473.55  4993.3  472.89  4993.8  472.09  4998.8  472.09  4999.3  472.89
  5031.8  473.59  5056.6  473.03  5061.9  473.33  5086.7  473.93  5111.4  474.01
  5115.9  474.18  5136.2  474.33  5141.5  474.57  5166.3  474.61  5217.6  475.40
#Mann=3,-1,0
  4618.5    0.05       0  4993.3    0.03       0  4999.3    0.05       0
Bank Sta=4927.7,5115.9
Exp/Cntr=0.3,0.1

Type RM Length L Ch R = 1,5720,38,38,38
BEGIN DESCRIPTION:
Mapping XS 9dd80d28
END DESCRIPTION:
XS GIS Cut Line= 6
      2868270.15      7032603.91      2868037.96      7032383.65
      2867883.88      7032283.82      2867838.30      7032287.08
      2867793.82      7032340.25      2867713.52      7032728.69
#Sta/Elev= 30
  4474.1  480.84  4491.2  480.04  4533.7  478.69  4554.7  478.40  4583.0  477.39
  4597.2  477.25  4618.6  476.14  4696.3  474.32  4710.4  473.56  4744.8  472.81
  4759.8  472.35  4774.0  471.38  4943.6  471.63  4968.4  471.49  5040.5  471.70
  5084.8  471.30  5085.3  470.50  5090.3  470.50  5090.8  471.30  5107.2  471.59
  5162.5  471.36  5169.1  471.96  5189.5  472.38  5212.7  472.21  5230.3  471.52
  5255.9  471.55  5354.4  472.81  5424.4  474.19  5458.8  474.31  5489.4  474.04
#Mann=5,-1,0
  4474.1    0.05       0  4943.6    0.16       0  5040.5    0.05       0
  5084.8    0.07       0  5090.8    0.05       0
Bank Sta=4744.8,5354.4
Exp/Cntr=0.3,0.1

Type RM Length L Ch R = 1,5682,44,44,44
BEGIN DESCRIPTION:
Mapping XS 2b5ffbaf
END DESCRIPTION:
XS GIS Cut Line= 6
      2868292.93      7032575.69      2868042.30      7032350.01
      2867900.15      7032257.78      2867837.22      7032249.10
      2867764.52      7032330.48      2867686.79      7032701.87
#Sta/Elev= 30
  4455.7  480.85  4723.5  472.78  4809.3  473.42  4815.4  474.17  4838.0  474.37
  4875.7  473.91  4909.7  474.90  4917.3  474.40  4923.1  475.03  4945.3  474.86
  4977.5  473.58  4991.9  474.10  5020.0  473.03  5033.6  473.86  5098.0  474.17
  5105.2  474.41  5111.5  473.20  5117.8  474.45  5132.3  473.56  5136.9  474.43
  5152.0  474.19  5167.8  472.48  5200.0  471.43  5200.5  470.63  5205.5  470.63
  5206.0  471.43  5233.7  472.51  5295.0  471.74  5356.3  472.48  5516.6  474.98
#Mann=5,-1,0
  4455.7    0.05       0  4875.7    0.16       0  5098.0    0.05       0
  5200.0    0.07       0  5206.0    0.05       0
Bank Sta=5167.8,5356.3
Exp/Cntr=0.3,0.1

Type RM Length L Ch R = 1,5638,133,133,133
BEGIN DESCRIPTION:
Mapping XS 248a5e68
END DESCRIPTION:
XS GIS Cut Line= 6
      2868290.80      7032530.16      2867941.39      7032229.57
      2867858.92      7032200.27      2867791.65      7032212.21
      2867727.63      7032305.53      2867628.04      7032690.89
#Sta/Elev= 30
  4463.0  480.33  4506.3  478.57  4598.2  476.31  4612.4  475.25  4804.3  470.65
  4810.6  469.54  4825.1  469.43  4855.8  467.25  4860.4  466.50  4874.8  466.28
  4903.9  465.97  4910.2  463.88  4918.4  464.63  4920.8  463.38  4921.3  462.58
  4926.3  462.58  4926.8  463.38  4930.9  465.56  4941.6  465.83  4955.1  464.60
  4962.8  466.46  4973.4  466.82  4994.6  466.40  5037.3  467.25  5046.1  468.10
  5130.9  469.58  5157.9  470.69  5181.1  470.43  5295.9  472.34  5591.2  475.57
#Mann=5,-1,0
  4463.0    0.05       0  4874.8    0.16       0  4920.8    0.07       0
  4926.8    0.16       0  5181.1    0.05       0
Bank Sta=4855.8,5037.3
Exp/Cntr=0.3,0.1

Type RM Length L Ch R = 1,5505,307,307,307
BEGIN DESCRIPTION:
UNT 139 in Running Cr Watershed 15.0
END DESCRIPTION:
XS GIS Cut Line= 3
      2868235.63      7032151.01      2867938.78      7032088.51
      2867534.68      7032176.84
#Sta/Elev= 30
  4666.1  472.25  4815.8  468.93  4901.8  468.13  4910.3  467.48  4934.8  466.94
  4952.1  466.03  4960.1  465.37  4965.2  465.82  4968.8  465.25  4977.4  465.09
  4983.6  464.52  4993.8  463.16  5001.0  461.32  5001.5  460.52  5006.5  460.52
  5007.0  461.32  5021.3  463.26  5026.4  464.54  5054.2  466.03  5114.2  468.29
  5168.3  469.35  5212.2  469.27  5239.5  469.68  5256.1  469.42  5261.2  469.90
  5270.2  469.50  5300.0  470.82  5321.4  470.50  5341.8  470.70  5383.1  471.90
#Mann=4,-1,0
  4666.1    0.05       0  4934.8    0.16       0  5001.0    0.07       0
  5007.0    0.16       0
Bank Sta=4952.1,5054.2
Exp/Cntr=0.3,0.1

Type RM Length L Ch R = 1,5198,423,423,423
BEGIN DESCRIPTION:
UNT 139 in Running Cr Watershed 14.0
END DESCRIPTION:
XS GIS Cut Line= 3
      2868180.94      7031867.15      2867852.84      7031794.24
      2867670.52      7031818.99
#Sta/Elev= 30
  4708.9  469.59  4715.0  469.21  4741.2  468.31  4868.6  467.23  4877.0  466.71
  4882.1  466.05  4899.4  465.47  4919.9  465.17  4932.3  464.38  4935.8  464.22
  4969.2  462.31  4974.3  461.90  4981.3  460.29  4991.6  459.55  4998.8  459.54
  4999.3  458.74  5004.3  458.74  5004.8  459.54  5017.8  462.80  5022.9  462.74
  5041.3  463.65  5064.4  464.38  5093.3  465.83  5133.7  466.96  5143.7  467.06
  5165.6  466.56  5204.3  466.91  5214.4  466.78  5224.2  467.25  5229.0  467.25
#Mann=4,-1,0
  4708.9    0.05       0  4935.8    0.16       0  4998.8    0.07       0
  5004.8    0.16       0
Bank Sta=4932.3,5064.4
Exp/Cntr=0.3,0.1

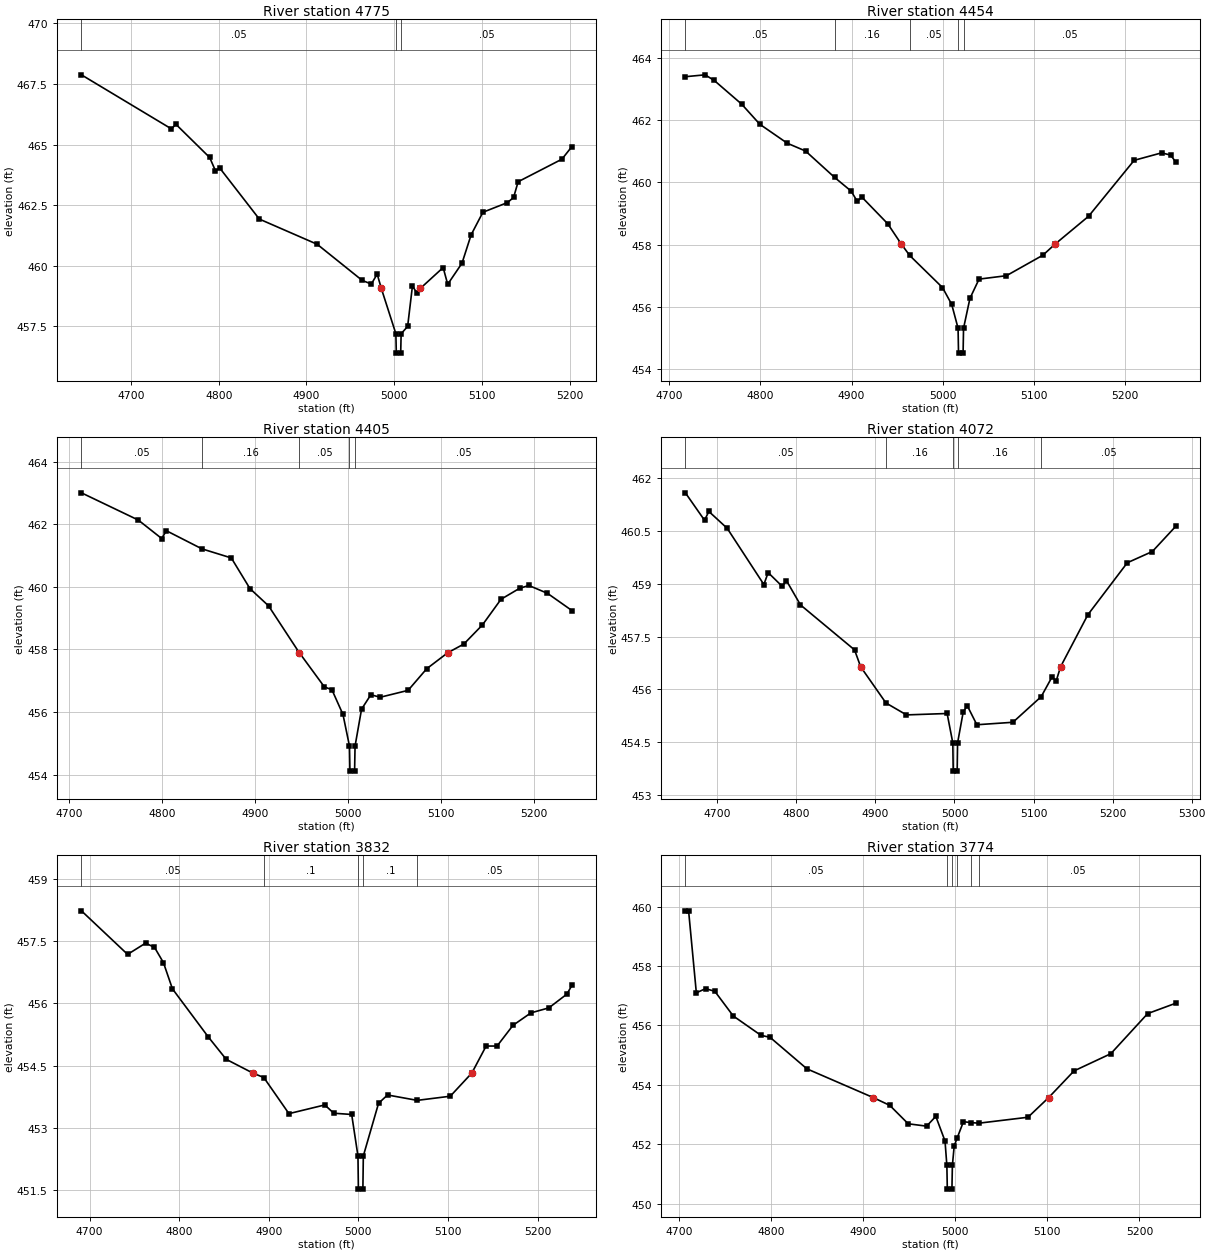
Type RM Length L Ch R = 1,4775,321,321,321
BEGIN DESCRIPTION:
UNT 139 in Running Cr Watershed 13.0
END DESCRIPTION:
XS GIS Cut Line= 3
      2868268.17      7031441.37      2867973.94      7031380.18
      2867723.94      7031446.58
#Sta/Elev= 30
  4643.4  467.88  4746.0  465.65  4751.1  465.84  4789.6  464.47  4796.1  463.93
  4801.2  464.03  4846.2  461.93  4912.2  460.89  4963.5  459.40  4973.9  459.25
  4980.6  459.66  4985.3  459.07  5001.9  457.20  5002.4  456.40  5007.4  456.40
  5007.9  457.20  5015.3  457.50  5020.8  459.17  5026.0  458.87  5029.8  459.07
  5055.8  459.93  5061.0  459.24  5077.3  460.11  5087.7  461.28  5101.1  462.21
  5129.1  462.61  5136.1  462.82  5141.3  463.47  5191.2  464.40  5202.6  464.92
#Mann=3,-1,0
  4643.4    0.05       0  5001.9    0.03       0  5007.9    0.05       0
Bank Sta=4985.3,5029.8
Exp/Cntr=0.3,0.1

Type RM Length L Ch R = 1,4454,49,49,49
BEGIN DESCRIPTION:
Mapping XS 2401d7f3
END DESCRIPTION:
XS GIS Cut Line= 3
      2868256.54      7031098.93      2867924.46      7031083.30
      2867719.32      7031080.71
#Sta/Elev= 30
  4717.9  463.40  4739.5  463.46  4749.5  463.28  4779.5  462.52  4799.5  461.87
  4829.6  461.26  4849.6  461.01  4881.5  460.16  4899.6  459.72  4906.3  459.39
  4911.3  459.53  4939.7  458.67  4954.5  458.02  4963.8  457.65  4999.7  456.62
  5009.8  456.08  5016.8  455.31  5017.3  454.51  5022.3  454.51  5022.8  455.31
  5029.8  456.27  5039.8  456.89  5069.8  457.00  5109.8  457.66  5123.3  458.02
  5159.8  458.91  5209.8  460.71  5239.8  460.95  5249.8  460.88  5255.5  460.65
#Mann=5,-1,0
  4717.9    0.05       0  4881.5    0.16       0  4963.8    0.05       0
  5016.8    0.04       0  5022.8    0.05       0
Bank Sta=4954.5,5123.3
Exp/Cntr=0.3,0.1

Type RM Length L Ch R = 1,4405,333,333,333
BEGIN DESCRIPTION:
UNT 139 in Running Cr Watershed 12.0
END DESCRIPTION:
XS GIS Cut Line= 3
      2868246.10      7031054.66      2867907.53      7031036.43
      2867718.73      7031032.55
#Sta/Elev= 30
  4713.1  463.00  4774.3  462.13  4799.5  461.54  4804.5  461.79  4842.8  461.21
  4874.4  460.92  4894.5  459.94  4914.5  459.39  4947.6  457.89  4947.7  457.89
  4974.6  456.80  4982.7  456.71  4994.6  455.92  5001.6  454.91  5002.1  454.11
  5007.1  454.11  5007.6  454.91  5014.6  456.09  5024.6  456.55  5034.7  456.47
  5064.7  456.69  5084.7  457.38  5107.3  457.89  5124.7  458.17  5144.7  458.78
  5164.7  459.60  5184.7  459.95  5194.7  460.04  5214.7  459.79  5241.0  459.24
#Mann=5,-1,0
  4713.1    0.05       0  4842.8    0.16       0  4947.6    0.05       0
  5001.6    0.04       0  5007.6    0.05       0
Bank Sta=4947.7,5107.3
Exp/Cntr=0.3,0.1

Type RM Length L Ch R = 1,4072,240,240,240
BEGIN DESCRIPTION:
UNT 139 in Running Cr Watershed 11.0
END DESCRIPTION:
XS GIS Cut Line= 4
      2868210.24      7030860.75      2867948.77      7030743.57
      2867871.67      7030728.33      2867629.30      7030808.46
#Sta/Elev= 30
  4659.6  461.59  4683.8  460.81  4689.3  461.06  4712.5  460.58  4758.9  458.98
  4764.3  459.32  4782.0  458.93  4787.5  459.09  4805.2  458.40  4873.6  457.12
  4881.3  456.64  4913.3  455.61  4939.3  455.27  4990.7  455.31  4997.9  454.47
  4998.4  453.67  5003.4  453.67  5003.9  454.47  5011.1  455.36  5016.2  455.53
  5028.3  454.99  5073.9  455.06  5109.7  455.79  5123.4  456.35  5128.7  456.24
  5134.2  456.64  5168.7  458.12  5218.6  459.60  5250.3  459.92  5280.0  460.64
#Mann=5,-1,0
  4659.6    0.05       0  4913.3    0.16       0  4997.9    0.07       0
  5003.9    0.16       0  5109.7    0.05       0
Bank Sta=4881.3,5134.2
Exp/Cntr=0.3,0.1

Type RM Length L Ch R = 1,3832,58,58,58
BEGIN DESCRIPTION:
Mapping XS 9a7838b5
END DESCRIPTION:
XS GIS Cut Line= 3
      2868236.51      7030503.44      2867859.79      7030501.71
      2867689.35      7030498.25
#Sta/Elev= 30
  4691.0  458.23  4742.5  457.18  4762.5  457.45  4772.5  457.35  4782.5  456.98
  4792.5  456.35  4832.5  455.19  4852.5  454.65  4882.1  454.32  4894.5  454.21
  4922.5  453.34  4962.5  453.55  4972.5  453.35  4992.5  453.32  4999.5  452.32
  5000.0  451.52  5005.0  451.52  5005.5  452.32  5022.5  453.59  5032.5  453.79
  5065.6  453.66  5102.5  453.76  5126.6  454.32  5142.5  454.97  5154.7  454.97
  5172.5  455.47  5192.5  455.77  5212.5  455.89  5232.5  456.22  5238.2  456.43
#Mann=5,-1,0
  4691.0    0.05       0  4894.5     0.1       0  4999.5    0.07       0
  5005.5     0.1       0  5065.6    0.05       0
Bank Sta=4882.1,5126.6
Exp/Cntr=0.3,0.1

Type RM Length L Ch R = 1,3774,121,121,121
BEGIN DESCRIPTION:
Mapping XS d2766e4e
END DESCRIPTION:
XS GIS Cut Line= 3
      2868236.94      7030457.43      2867885.40      7030448.32
      2867704.40      7030444.41
#Sta/Elev= 30
  4706.8  459.86  4710.3  459.86  4718.7  457.10  4728.7  457.24  4738.8  457.15
  4758.8  456.32  4788.8  455.67  4798.8  455.60  4838.8  454.54  4911.0  453.57
  4928.8  453.31  4948.8  452.69  4968.8  452.61  4978.8  452.94  4988.8  452.11
  4990.8  451.29  4991.3  450.49  4996.3  450.49  4996.8  451.29  4998.8  451.95
  5002.1  452.22  5008.8  452.76  5017.1  452.73  5025.5  452.71  5078.9  452.91
  5101.3  453.57  5128.9  454.47  5168.9  455.05  5208.9  456.40  5239.5  456.75
#Mann=6,-1,0
  4706.8    0.05       0  4990.8    0.03       0  4996.8    0.05       0
  5002.1     0.1       0  5017.1    0.16       0  5025.5    0.05       0
Bank Sta=4911,5101.3
Exp/Cntr=0.3,0.1

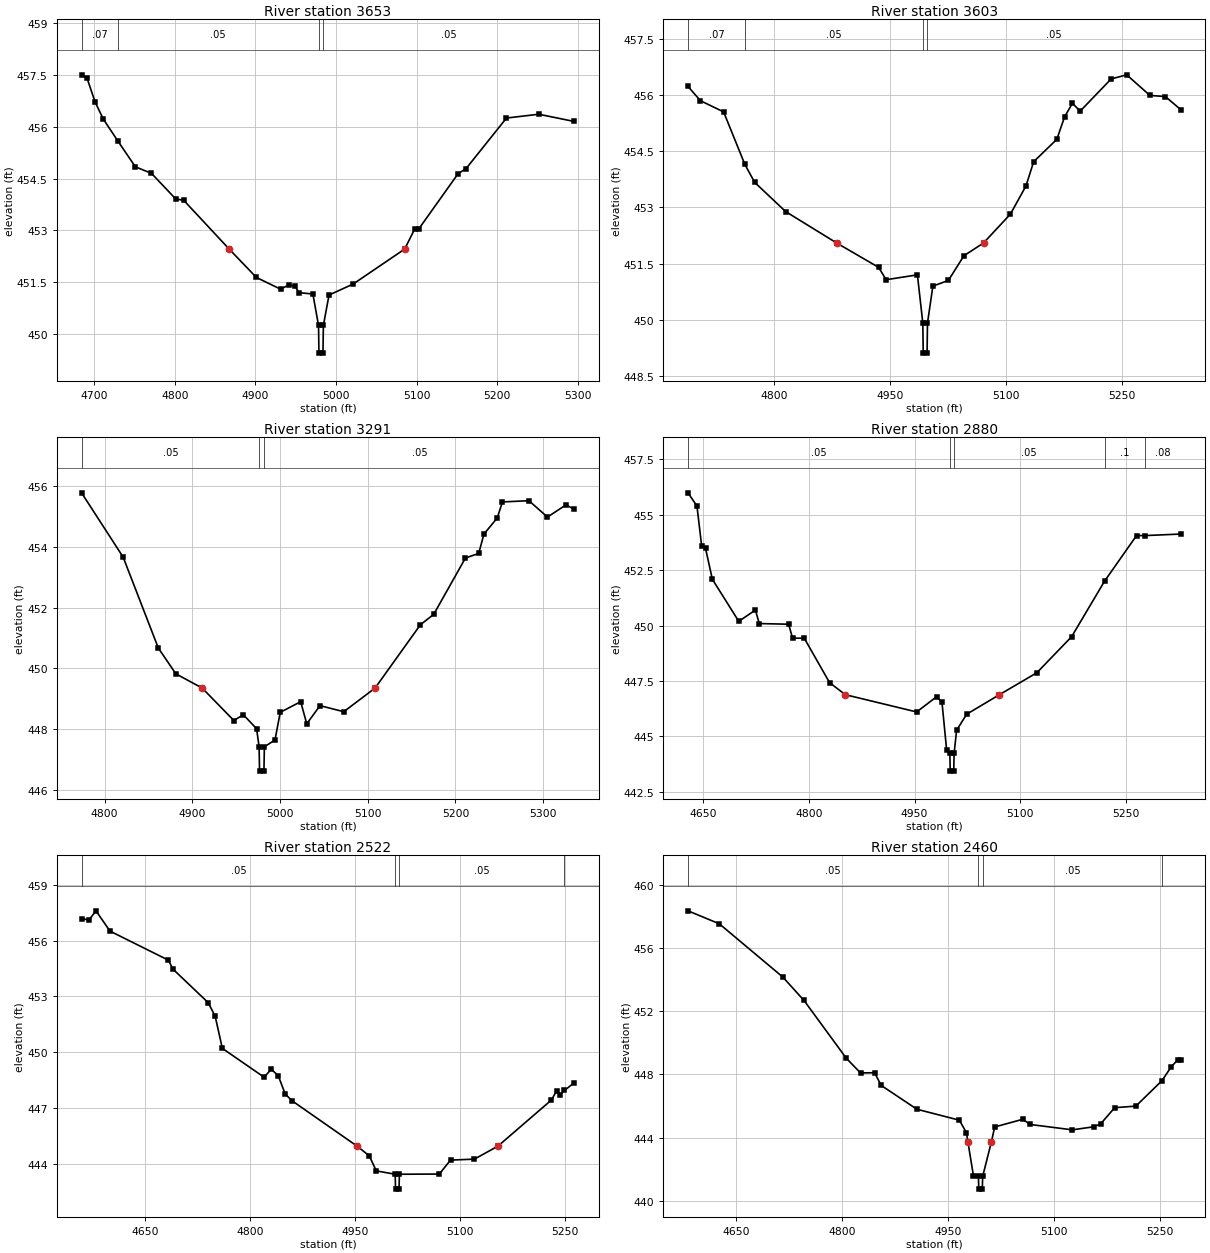
Type RM Length L Ch R = 1,3653,50,50,50
BEGIN DESCRIPTION:
Mapping XS 64767655
END DESCRIPTION:
XS GIS Cut Line= 3
      2868261.71      7030335.04      2867847.64      7030327.23
      2867650.99      7030320.72
#Sta/Elev= 30
  4684.5  457.50  4691.2  457.41  4701.2  456.72  4711.2  456.23  4729.1  455.60
  4751.2  454.84  4771.2  454.65  4801.2  453.91  4811.2  453.87  4867.5  452.46
  4901.2  451.64  4931.2  451.30  4941.3  451.42  4949.0  451.39  4954.0  451.20
  4971.3  451.16  4978.3  450.25  4978.8  449.45  4983.8  449.45  4984.3  450.25
  4991.3  451.13  5021.3  451.45  5085.1  452.46  5097.5  453.04  5102.5  453.04
  5151.3  454.64  5161.3  454.79  5211.3  456.25  5251.4  456.36  5295.4  456.15
#Mann=4,-1,0
  4684.5    0.07       0  4729.1    0.05       0  4978.3    0.03       0
  4984.3    0.05       0
Bank Sta=4867.5,5085.1
Exp/Cntr=0.3,0.1

Type RM Length L Ch R = 1,3603,312,312,312
BEGIN DESCRIPTION:
UNT 139 in Running Cr Watershed 10.0
END DESCRIPTION:
XS GIS Cut Line= 3
      2868270.98      7030297.60      2868010.61      7030284.58
      2867635.17      7030263.97
#Sta/Elev= 30
  4688.9  456.23  4704.9  455.85  4734.9  455.55  4762.3  454.15  4775.0  453.67
  4815.0  452.89  4881.0  452.05  4935.2  451.40  4944.9  451.07  4985.3  451.20
  4992.3  449.91  4992.8  449.11  4997.8  449.11  4998.3  449.91  5005.3  450.90
  5025.3  451.05  5045.4  451.71  5070.7  452.05  5105.4  452.82  5125.5  453.57
  5135.5  454.22  5165.5  454.82  5175.5  455.42  5185.6  455.78  5195.6  455.57
  5235.6  456.43  5255.7  456.54  5285.7  455.99  5305.7  455.96  5325.6  455.61
#Mann=4,-1,0
  4688.9    0.07       0  4762.3    0.05       0  4992.3    0.03       0
  4998.3    0.05       0
Bank Sta=4881,5070.7
Exp/Cntr=0.3,0.1

Type RM Length L Ch R = 1,3291,411,411,411
BEGIN DESCRIPTION:
UNT 139 in Running Cr Watershed 9.0
END DESCRIPTION:
XS GIS Cut Line= 3
      2868112.41      7029957.89      2867937.86      7029964.52
      2867614.14      7030176.64
#Sta/Elev= 30
  4773.8  455.79  4821.2  453.67  4861.3  450.67  4881.3  449.82  4911.3  449.35
  4947.4  448.28  4958.2  448.47  4973.3  448.01  4976.2  447.41  4976.7  446.61
  4981.7  446.61  4982.2  447.41  4994.3  447.64  5000.3  448.55  5023.6  448.90
  5030.5  448.17  5045.6  448.77  5072.7  448.57  5108.4  449.35  5160.1  451.44
  5175.2  451.78  5211.4  453.64  5226.5  453.79  5232.5  454.43  5247.6  454.96
  5253.6  455.49  5283.8  455.53  5304.9  454.99  5325.9  455.39  5335.5  455.25
#Mann=3,-1,0
  4773.8    0.05       0  4976.2    0.04       0  4982.2    0.05       0
Bank Sta=4911.3,5108.4
Exp/Cntr=0.3,0.1

Type RM Length L Ch R = 1,2880,358,358,358
BEGIN DESCRIPTION:
UNT 139 in Running Cr Watershed 8.0
END DESCRIPTION:
XS GIS Cut Line= 3
      2867886.69      7029641.92      2867575.00      7029775.00
      2867305.07      7030013.48
#Sta/Elev= 30
  4628.6  455.99  4641.3  455.39  4648.0  453.58  4653.4  453.49  4663.1  452.09
  4700.6  450.19  4724.2  450.70  4729.7  450.09  4771.4  450.06  4776.9  449.43
  4793.5  449.43  4829.5  447.42  4851.8  446.88  4953.0  446.10  4981.3  446.79
  4988.9  446.54  4995.5  444.39  5000.1  444.23  5000.6  443.43  5005.6  443.43
  5006.1  444.23  5009.7  445.28  5024.0  446.00  5070.4  446.88  5123.5  447.87
  5172.9  449.50  5219.5  452.00  5264.9  454.06  5276.6  454.06  5327.7  454.13
#Mann=5,-1,0
  4628.6    0.05       0  5000.1   0.035       0  5006.1    0.05       0
  5219.5     0.1       0  5276.6    0.08       0
Bank Sta=4851.8,5070.4
Exp/Cntr=0.3,0.1

Type RM Length L Ch R = 1,2522,62,62,62
BEGIN DESCRIPTION:
Mapping XS e2aca958
END DESCRIPTION:
XS GIS Cut Line= 4
      2867945.54      7029466.79      2867821.81      7029461.36
      2867418.17      7029453.77      2867242.39      7029449.43
#Sta/Elev= 30
  4559.6  457.18  4570.2  457.11  4580.2  457.60  4600.2  456.51  4683.5  454.95
  4690.3  454.46  4740.3  452.67  4750.3  451.94  4760.6  450.21  4820.3  448.66
  4830.3  449.09  4840.3  448.75  4850.3  447.76  4860.3  447.39  4952.9  444.96
  4970.3  444.44  4980.3  443.63  5007.3  443.45  5007.8  442.65  5012.8  442.65
  5013.3  443.45  5070.3  443.46  5086.3  444.21  5120.3  444.26  5154.0  444.96
  5230.4  447.44  5237.6  447.92  5242.6  447.72  5248.9  447.95  5263.0  448.37
#Mann=4,-1,0
  4559.6    0.05       0  5007.3    0.04       0  5013.3    0.05       0
  5248.9    0.08       0
Bank Sta=4952.9,5154
Exp/Cntr=0.3,0.1

Type RM Length L Ch R = 1,2460,424,424,424
BEGIN DESCRIPTION:
UNT 139 in Running Cr Watershed 7.0
END DESCRIPTION:
XS GIS Cut Line= 3
      2867929.26      7029393.00      2867651.46      7029393.00
      2867231.36      7029393.00
#Sta/Elev= 30
  4581.8  458.35  4626.1  457.53  4716.1  454.16  4746.1  452.68  4806.1  449.02
  4826.1  448.10  4846.1  448.11  4855.3  447.31  4906.1  445.80  4966.1  445.11
  4976.1  444.32  4978.2  443.74  4986.1  441.58  4993.1  441.55  4993.6  440.75
  4998.6  440.75  4999.1  441.55  5011.5  443.74  5016.1  444.68  5056.1  445.17
  5066.1  444.84  5126.1  444.50  5156.1  444.69  5166.1  444.87  5186.1  445.90
  5216.1  446.00  5253.1  447.61  5266.1  448.48  5275.4  448.93  5279.7  448.93
#Mann=4,-1,0
  4581.8    0.05       0  4993.1    0.04       0  4999.1    0.05       0
  5253.1    0.08       0
Bank Sta=4978.2,5011.5
Exp/Cntr=0.3,0.1

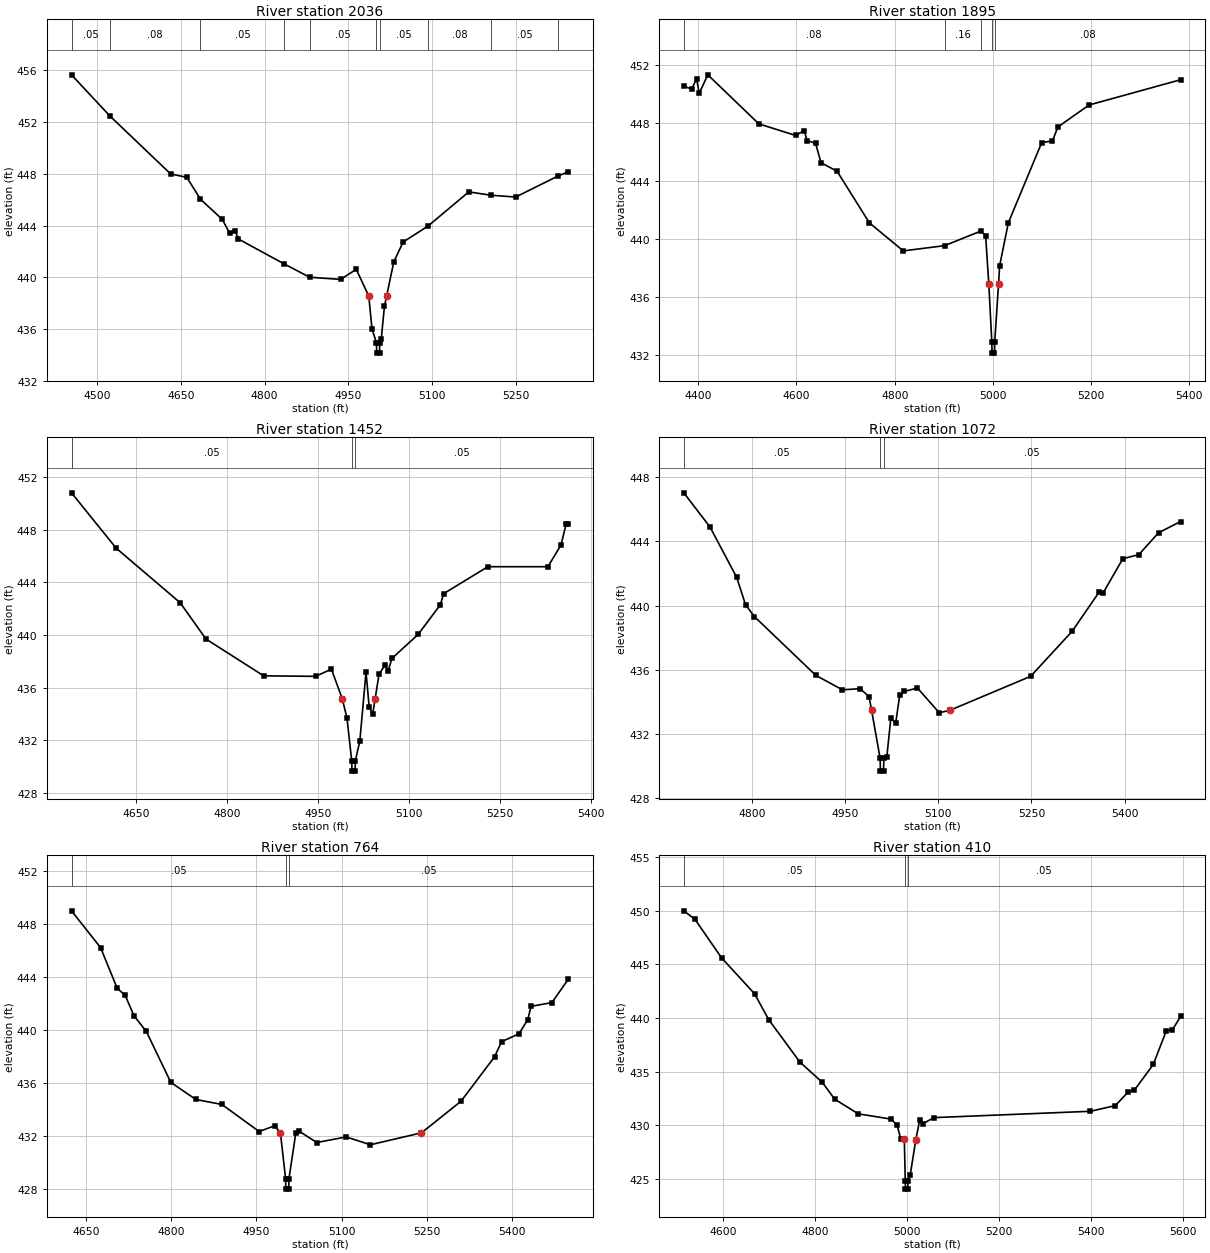
Type RM Length L Ch R = 1,2036,141,141,141
BEGIN DESCRIPTION:
UNT 139 in Running Cr Watershed 6.0
END DESCRIPTION:
XS GIS Cut Line= 3
      2867632.35      7028577.05      2867454.26      7028971.05
      2867250.43      7029379.09
#Sta/Elev= 30
  4454.6  455.66  4523.2  452.48  4631.8  448.00  4660.9  447.73  4685.3  446.04
  4724.3  444.48  4737.7  443.40  4747.4  443.61  4752.9  442.97  4835.3  441.03
  4880.5  440.01  4935.9  439.84  4963.9  440.62  4986.3  438.55  4992.0  436.03
  5000.0  434.94  5000.5  434.14  5005.5  434.14  5006.0  434.94  5008.6  435.23
  5014.4  437.79  5018.2  438.55  5031.0  441.19  5047.7  442.73  5092.1  443.96
  5165.2  446.61  5204.6  446.35  5249.0  446.21  5324.5  447.83  5343.1  448.16
#Mann=10,-1,0
  4454.6    0.05       0  4523.2    0.08       0  4685.3    0.05       0
  4835.3    0.08       0  4880.5    0.05       0  5000.0   0.035       0
  5006.0    0.05       0  5092.1    0.08       0  5204.6    0.05       0
  5324.5    0.08       0
Bank Sta=4986.3,5018.2
Exp/Cntr=0.3,0.1

Type RM Length L Ch R = 1,1895,443,443,443
BEGIN DESCRIPTION:
UNT 139 in Running Cr Watershed 5.0
END DESCRIPTION:
XS GIS Cut Line= 3
      2867552.48      7028410.40      2867240.00      7029104.81
      2867125.41      7029327.03
#Sta/Elev= 30
  4370.6  450.53  4386.6  450.32  4396.5  451.04  4402.0  450.04  4419.5  451.31
  4523.3  447.93  4598.2  447.13  4615.9  447.47  4621.3  446.78  4638.8  446.59
  4650.0  445.25  4682.7  444.66  4748.5  441.10  4817.5  439.17  4901.5  439.53
  4975.0  440.53  4985.1  440.23  4991.6  436.90  4997.7  432.92  4998.2  432.12
  5003.2  432.12  5003.7  432.92  5011.5  436.90  5013.7  438.15  5031.4  441.11
  5099.4  446.64  5121.3  446.75  5132.1  447.71  5195.8  449.23  5382.1  450.97
#Mann=5,-1,0
  4370.6    0.08       0  4901.5    0.16       0  4975.0    0.08       0
  4997.7    0.07       0  5003.7    0.08       0
Bank Sta=4991.6,5011.5
Exp/Cntr=0.3,0.1

Type RM Length L Ch R = 1,1452,380,380,380
BEGIN DESCRIPTION:
UNT 139 in Running Cr Watershed 4.0
END DESCRIPTION:
XS GIS Cut Line= 3
      2867160.15      7028285.33      2866975.00      7028821.82
      2866882.34      7029056.23
#Sta/Elev= 30
  4542.8  450.82  4616.5  446.61  4722.1  442.46  4764.6  439.70  4859.8  436.90
  4945.7  436.86  4971.6  437.41  4989.4  435.17  4997.3  433.69  5005.1  430.45
  5005.6  429.65  5010.6  429.65  5011.1  430.45  5018.5  431.93  5028.7  437.19
  5034.0  434.50  5039.7  433.99  5043.8  435.17  5050.2  437.02  5059.9  437.71
  5065.2  437.27  5071.4  438.22  5114.7  440.05  5151.3  442.30  5156.8  443.15
  5229.7  445.20  5328.8  445.20  5350.3  446.84  5359.0  448.46  5362.4  448.46
#Mann=3,-1,0
  4542.8    0.05       0  5005.1    0.03       0  5011.1    0.05       0
Bank Sta=4989.4,5043.8
Exp/Cntr=0.3,0.1

Type RM Length L Ch R = 1,1072,308,308,308
BEGIN DESCRIPTION:
UNT 139 in Running Cr Watershed 3.0
END DESCRIPTION:
XS GIS Cut Line= 3
      2866925.02      7028274.97      2866649.72      7028597.87
      2866467.42      7028926.00
#Sta/Elev= 30
  4690.3  447.03  4732.6  444.89  4775.4  441.76  4789.7  440.05  4804.0  439.31
  4902.8  435.65  4945.6  434.75  4974.2  434.82  4988.5  434.32  4992.6  433.47
  5006.3  430.48  5006.8  429.68  5011.8  429.68  5012.3  430.48  5017.0  430.53
  5023.6  432.99  5031.3  432.66  5037.9  434.42  5045.2  434.65  5066.4  434.86
  5101.5  433.32  5118.5  433.47  5248.6  435.59  5315.7  438.41  5359.2  440.86
  5364.9  440.76  5397.0  442.92  5422.9  443.18  5454.5  444.54  5490.0  445.24
#Mann=3,-1,0
  4690.3    0.05       0  5006.3    0.03       0  5012.3    0.05       0
Bank Sta=4992.6,5118.5
Exp/Cntr=0.3,0.1

Type RM Length L Ch R = 1,764,354,354,354
BEGIN DESCRIPTION:
UNT 139 in Running Cr Watershed 2.0
END DESCRIPTION:
XS GIS Cut Line= 3
      2866824.96      7028125.02      2866475.00      7028325.00
      2866224.98      7028725.03
#Sta/Elev= 30
  4624.3  449.03  4675.4  446.26  4704.9  443.17  4718.6  442.67  4734.4  441.10
  4756.0  439.93  4799.2  436.08  4843.1  434.79  4889.2  434.41  4954.7  432.37
  4982.0  432.80  4992.2  432.27  5001.3  428.82  5001.8  428.02  5006.8  428.02
  5007.3  428.82  5019.4  432.28  5024.5  432.41  5056.3  431.54  5108.1  431.96
  5150.6  431.37  5240.6  432.27  5310.4  434.66  5369.3  438.01  5381.7  439.15
  5412.4  439.75  5427.7  440.81  5433.6  441.82  5470.2  442.10  5499.1  443.86
#Mann=3,-1,0
  4624.3    0.05       0  5001.3    0.03       0  5007.3    0.05       0
Bank Sta=4992.2,5240.6
Exp/Cntr=0.3,0.1

Type RM Length L Ch R = 1,410,0,0,0
BEGIN DESCRIPTION:
UNT 139 in Running Cr Watershed 1.0
END DESCRIPTION:
XS GIS Cut Line= 3
      2866825.04      7027874.99      2866375.00      7027975.00
      2866225.00      7028575.02
#Sta/Elev= 30
  4515.4  449.98  4539.8  449.18  4597.4  445.60  4669.1  442.26  4699.8  439.85
  4767.7  435.89  4816.4  434.00  4843.2  432.44  4894.5  431.07  4966.2  430.58
  4979.0  430.00  4986.7  428.75  4994.5  428.74  4996.6  424.86  4997.1  424.06
  5002.1  424.06  5002.6  424.86  5007.3  425.35  5019.6  428.68  5028.0  430.48
  5035.7  430.17  5058.9  430.72  5399.0  431.31  5453.2  431.84  5481.5  433.13
  5494.4  433.27  5535.6  435.67  5564.0  438.83  5576.8  438.87  5594.9  440.14
#Mann=3,-1,0
  4515.4    0.05       0  4996.6    0.03       0  5002.6    0.05       0
Bank Sta=4994.5,5019.6
Exp/Cntr=0.3,0.1

Chan Stop Cuts=-1