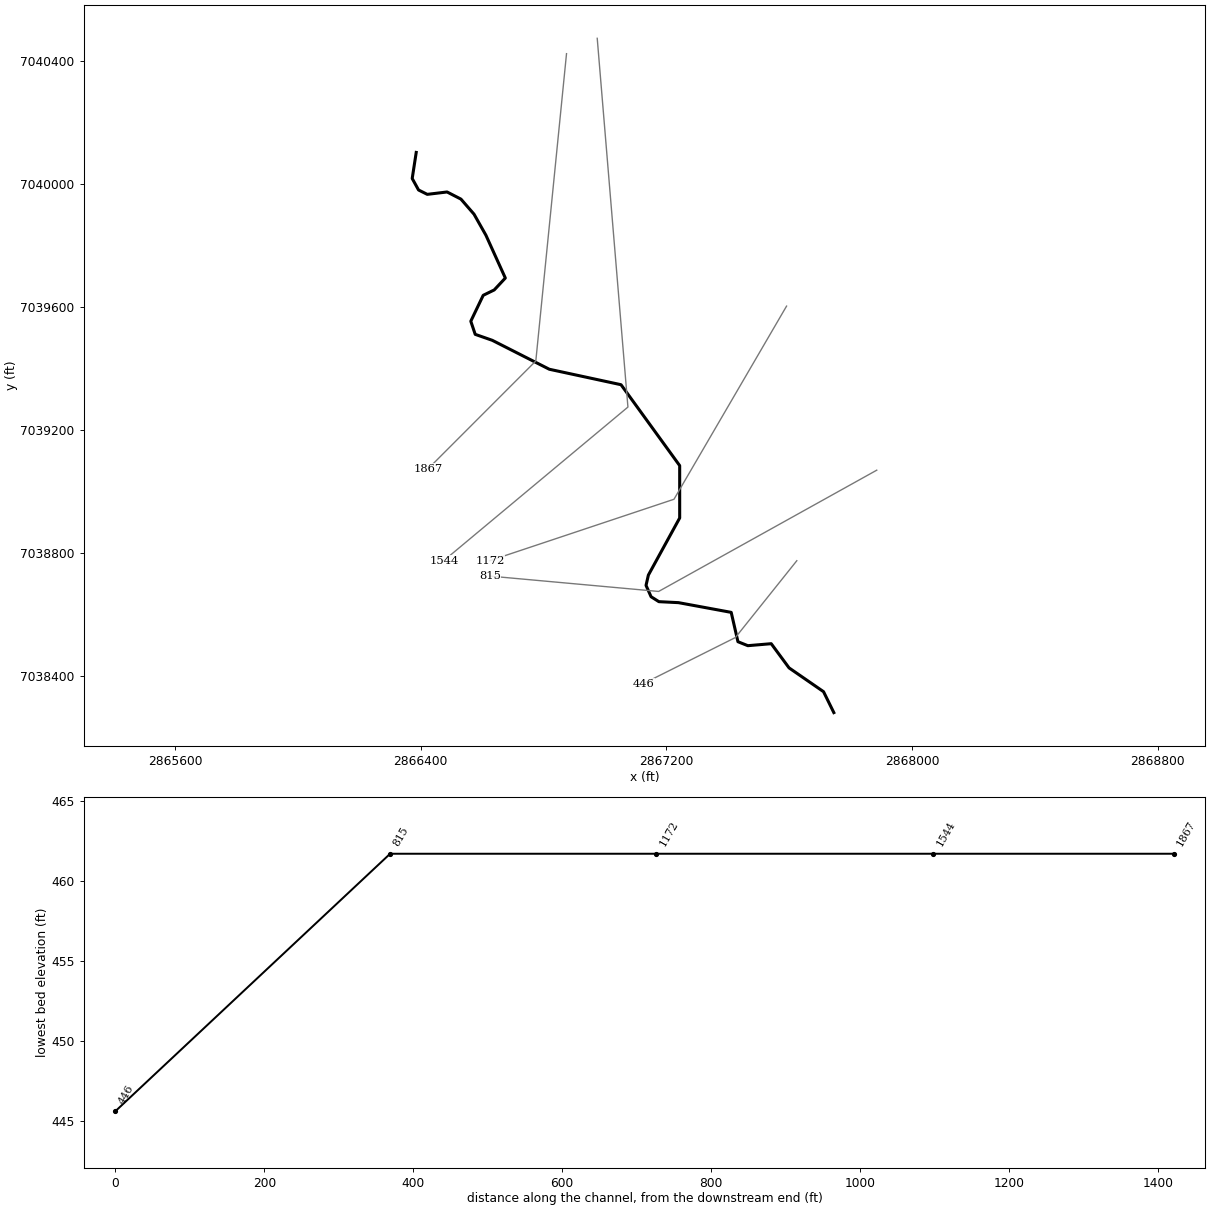
--- UNT 140 in Running Cr Watershed.prj (project) ---

Proj Title=UNT 140 in Running Cr Watershed Base Level Engineering
Current Plan=p01
Default Exp/Contr=0.3,0.1
English Units
Geom File=g01
Flow File=f01
Plan File=p01
BEGIN DESCRIPTION:
UNT 140 in Running Cr Watershed
END DESCRIPTION:

--- UNT 140 in Running Cr Watershed.p01 (plan) ---

Plan Title=Multiple Run
Short Identifier=Multiple
Geom File=g01
Flow File=f01
Subcritical Flow
K Sum by GR= 0
Std Step Tol= 0.01
Critical Tol= 0.01
Num of Std Step Trials= 20
Max Error Tol= 0.3
Flow Tol Ratio= 0.001
Split Flow NTrial= 30
Split Flow Tol= 0.02
Split Flow Ratio= 0.02
Log Output Level= 0
Friction Slope Method= 1
Unsteady Friction Slope Method= 2
Unsteady Bridges Friction Slope Method= 1
Parabolic Critical Depth
Global Vel Dist=  1 , 1 , 1
Global Log Level= 0
CheckData=True
Encroach Param= -1, 0, 0, 0
BEGIN DESCRIPTION:
Multiple Run
END DESCRIPTION:

--- UNT 140 in Running Cr Watershed.f01 (steady flow) ---

Flow Title=Multiple
Number of Profiles=7
Profile Names=10-year,25-year,50-year,1pct_min,100-year,1pct_plu,500-year
River Rch & RM= UNT 140 in Runni,Reach-1,1867
     264     337     393     229     457     912     618
Boundary for River Rch & Prof#=UNT 140 in Runni,Reach-1,1
Up Type=0
Dn Type=3
Dn Slope=0.005
Boundary for River Rch & Prof#=UNT 140 in Runni,Reach-1,2
Up Type=0
Dn Type=3
Dn Slope=0.005
Boundary for River Rch & Prof#=UNT 140 in Runni,Reach-1,3
Up Type=0
Dn Type=3
Dn Slope=0.005
Boundary for River Rch & Prof#=UNT 140 in Runni,Reach-1,4
Up Type=0
Dn Type=3
Dn Slope=0.005
Boundary for River Rch & Prof#=UNT 140 in Runni,Reach-1,5
Up Type=0
Dn Type=3
Dn Slope=0.005
Boundary for River Rch & Prof#=UNT 140 in Runni,Reach-1,6
Up Type=0
Dn Type=3
Dn Slope=0.005
Boundary for River Rch & Prof#=UNT 140 in Runni,Reach-1,7
Up Type=0
Dn Type=3
Dn Slope=0.005

--- UNT 140 in Running Cr Watershed.g01 (geometry) ---

Geom Title=Existing Conditions

River Reach=UNT 140 in Runni,Reach-1
Reach XY= 30
      2866385.50      7040103.65      2866372.43      7040018.82
      2866393.08      7039981.40      2866421.47      7039967.20
      2866486.00      7039974.94      2866531.17      7039951.71
      2866573.76      7039902.67      2866612.48      7039834.27
      2866675.72      7039694.89      2866639.58      7039656.17
      2866603.69      7039638.66      2866563.25      7039554.37
      2866577.63      7039511.63      2866633.13      7039492.27
      2866818.97      7039398.06      2867052.57      7039347.72
      2867243.57      7039084.45      2867243.57      7038914.09
      2867141.61      7038728.25      2867133.96      7038694.75
      2867150.37      7038657.81      2867175.80      7038641.76
      2867239.68      7038638.54      2867411.35      7038606.93
      2867433.29      7038511.43      2867465.55      7038498.52
      2867541.69      7038504.98      2867599.77      7038426.25
      2867712.05      7038348.82      2867745.59      7038280.71

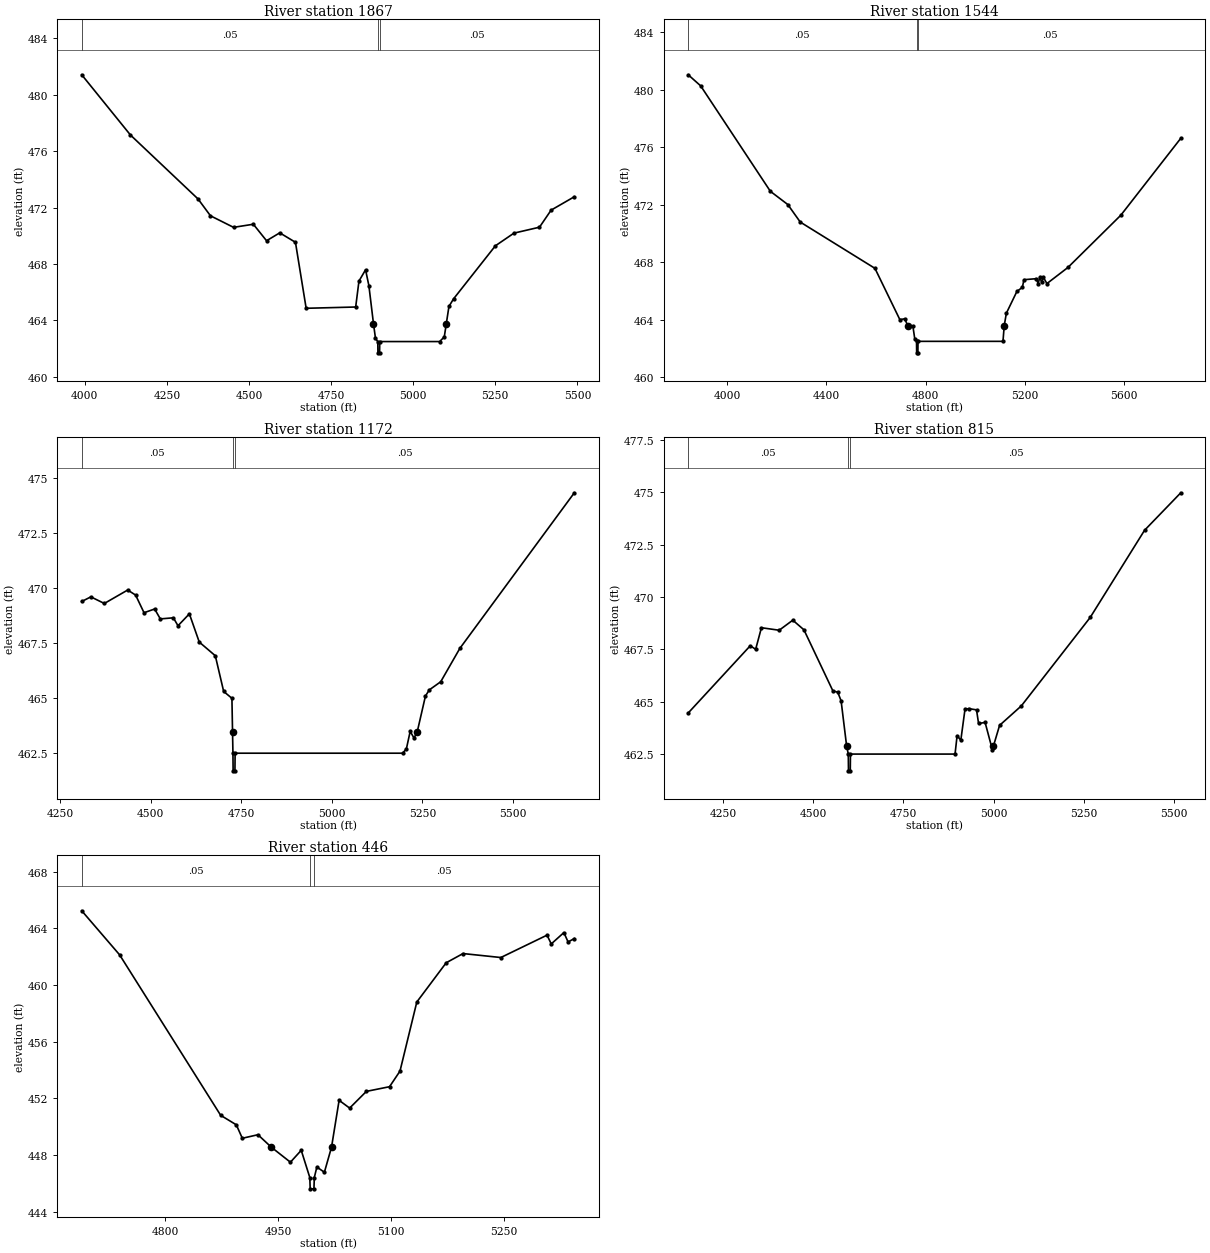
Type RM Length L Ch R = 1,1867,323,323,323
BEGIN DESCRIPTION:
UNT 140 in Running Cr Watershed 5.0
END DESCRIPTION:
XS GIS Cut Line= 3
      2866875.00      7040425.05      2866775.00      7039425.00
      2866425.01      7039075.01
#Sta/Elev= 30
  3990.6  481.42  4138.9  477.15  4344.9  472.61  4382.6  471.42  4452.9  470.60
  4513.2  470.82  4553.4  469.65  4593.6  470.21  4641.4  469.54  4674.0  464.86
  4824.8  464.95  4834.8  466.79  4854.9  467.59  4865.0  466.47  4879.0  463.77
  4885.1  462.73  4892.1  462.50  4892.6  461.70  4897.6  461.70  4898.1  462.50
  5080.5  462.50  5094.6  462.83  5100.8  463.77  5108.8  464.99  5122.9  465.53
  5250.2  469.29  5306.8  470.19  5384.5  470.61  5419.9  471.82  5490.6  472.77
#Mann=3,-1,0
  3990.6    0.05       0  4892.1   0.033       0  4898.1    0.05       0
Bank Sta=4879,5100.8
Exp/Cntr=0.3,0.1

Type RM Length L Ch R = 1,1544,372,372,372
BEGIN DESCRIPTION:
UNT 140 in Running Cr Watershed 4.0
END DESCRIPTION:
XS GIS Cut Line= 3
      2866975.00      7040475.03      2867075.00      7039275.00
      2866475.01      7038775.01
#Sta/Elev= 30
  3843.2  481.05  3893.4  480.28  4174.4  472.94  4244.6  472.02  4294.8  470.80
  4595.8  467.58  4696.2  464.01  4716.2  464.07  4727.5  463.60  4748.9  463.54
  4756.4  462.66  4763.4  462.50  4763.9  461.70  4768.9  461.70  4769.4  462.50
  5111.8  462.50  5116.9  463.60  5125.5  464.46  5167.8  465.97  5189.9  466.26
  5196.4  466.79  5245.9  466.86  5253.7  466.51  5260.2  466.97  5268.0  466.60
  5274.5  466.96  5288.9  466.52  5373.5  467.64  5586.9  471.28  5828.4  476.63
#Mann=3,-1,0
  3843.2    0.05       0  4763.4   0.033       0  4769.4    0.05       0
Bank Sta=4727.5,5116.9
Exp/Cntr=0.3,0.1

Type RM Length L Ch R = 1,1172,357,357,357
BEGIN DESCRIPTION:
UNT 140 in Running Cr Watershed 3.0
END DESCRIPTION:
XS GIS Cut Line= 3
      2867591.64      7039603.53      2867225.00      7038975.00
      2866625.01      7038775.00
#Sta/Elev= 30
  4309.2  469.38  4334.4  469.59  4371.6  469.29  4436.1  469.90  4458.0  469.67
  4481.2  468.87  4510.5  469.04  4526.2  468.59  4562.2  468.64  4575.0  468.28
  4606.4  468.82  4633.7  467.54  4678.0  466.92  4701.1  465.30  4723.9  464.99
  4725.6  463.45  4726.7  462.50  4727.2  461.70  4732.2  461.70  4732.7  462.50
  5195.0  462.50  5205.5  462.69  5216.1  463.49  5226.6  463.19  5235.3  463.45
  5258.2  465.09  5268.8  465.37  5300.4  465.74  5353.1  467.25  5669.3  474.31
#Mann=3,-1,0
  4309.2    0.05       0  4726.7   0.033       0  4732.7    0.05       0
Bank Sta=4725.6,5235.3
Exp/Cntr=0.3,0.1

Type RM Length L Ch R = 1,815,369,369,369
BEGIN DESCRIPTION:
UNT 140 in Running Cr Watershed 2.0
END DESCRIPTION:
XS GIS Cut Line= 3
      2867885.37      7039069.65      2867175.00      7038675.00
      2866625.01      7038725.00
#Sta/Elev= 30
  4153.6  464.46  4325.6  467.67  4340.5  467.50  4356.5  468.53  4405.7  468.41
  4443.4  468.89  4474.3  468.43  4554.4  465.52  4568.1  465.45  4577.3  465.04
  4592.6  462.88  4597.2  462.50  4597.7  461.70  4602.7  461.70  4603.2  462.50
  4893.0  462.50  4898.7  463.38  4909.0  463.16  4920.5  464.63  4930.8  464.67
  4952.5  464.61  4958.2  463.96  4976.3  464.01  4996.4  462.71  4999.3  462.88
  5016.4  463.87  5076.7  464.80  5267.5  469.02  5418.1  473.18  5518.5  474.97
#Mann=3,-1,0
  4153.6    0.05       0  4597.2    0.03       0  4603.2    0.05       0
Bank Sta=4592.6,4999.3
Exp/Cntr=0.3,0.1

Type RM Length L Ch R = 1,446,0,0,0
BEGIN DESCRIPTION:
UNT 140 in Running Cr Watershed 1.0
END DESCRIPTION:
XS GIS Cut Line= 3
      2867624.98      7038774.98      2867425.00      7038525.00
      2867125.04      7038375.02
#Sta/Elev= 30
  4688.6  465.25  4739.0  462.14  4873.5  450.81  4894.3  450.14  4902.3  449.19
  4923.1  449.44  4940.9  448.56  4966.3  447.50  4980.7  448.34  4992.1  446.42
  4992.6  445.62  4997.6  445.62  4998.1  446.42  5001.5  447.16  5011.5  446.79
  5021.0  448.56  5031.1  451.87  5045.1  451.32  5067.4  452.50  5098.2  452.83
  5112.1  453.93  5134.5  458.81  5173.6  461.58  5196.0  462.23  5246.3  461.95
  5307.8  463.53  5313.4  462.91  5330.2  463.71  5335.8  463.05  5344.1  463.29
#Mann=3,-1,0
  4688.6    0.05       0  4992.1    0.03       0  4998.1    0.05       0
Bank Sta=4940.9,5021
Exp/Cntr=0.3,0.1

Chan Stop Cuts=-1