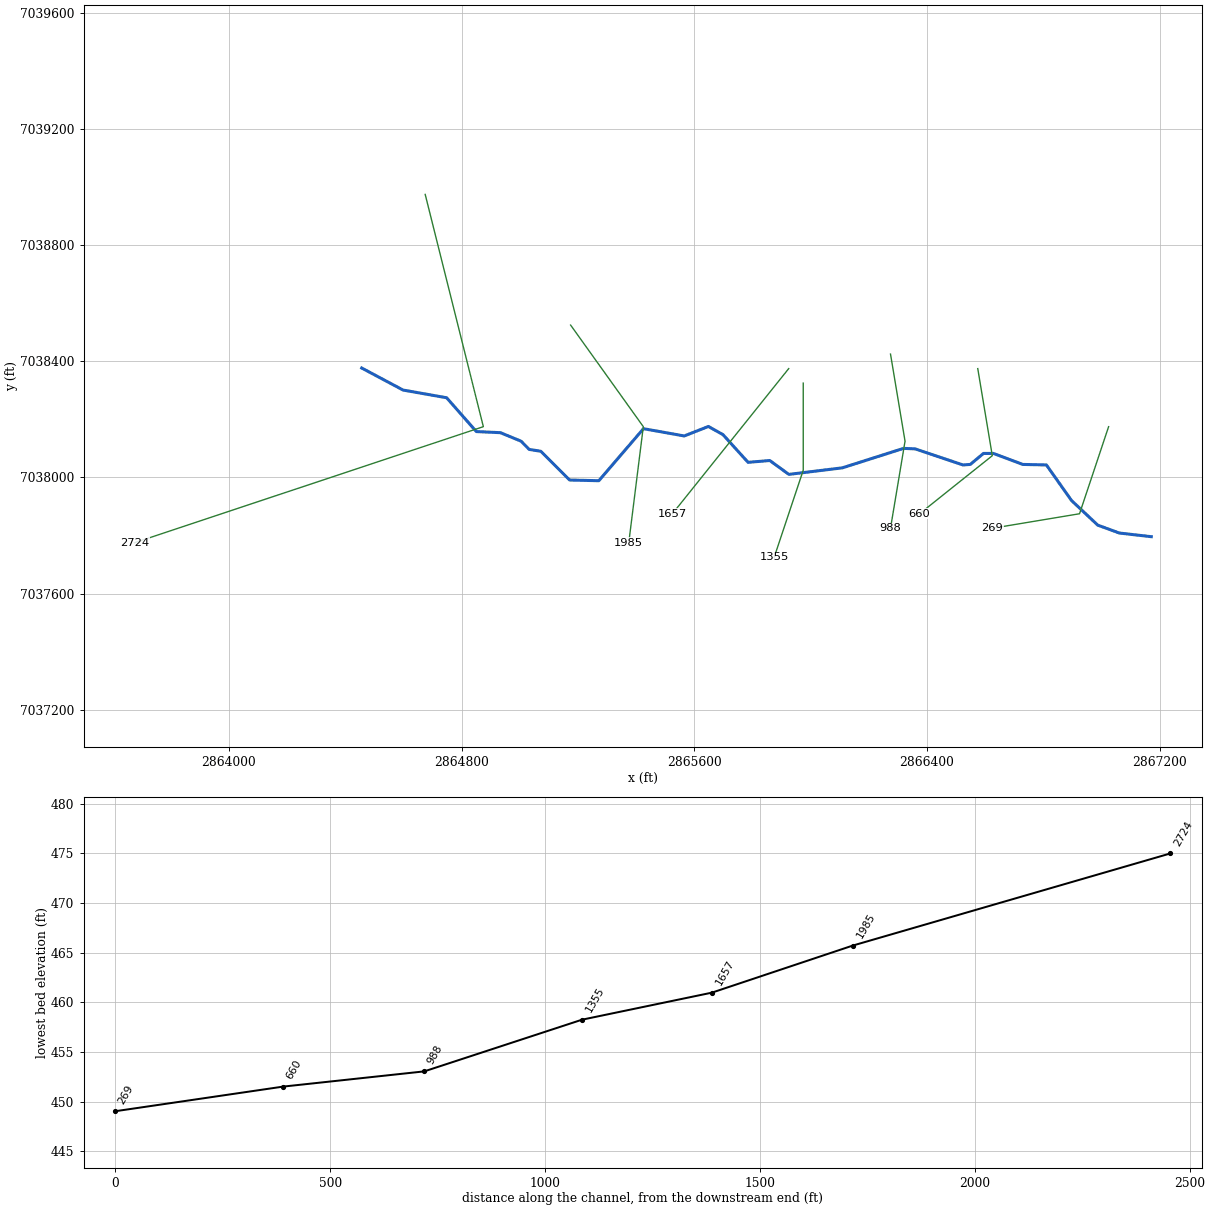
--- UNT 141 in Running Cr Watershed.prj (project) ---

Proj Title=UNT 141 in Running Cr Watershed Base Level Engineering
Current Plan=p01
Default Exp/Contr=0.3,0.1
English Units
Geom File=g01
Flow File=f01
Plan File=p01
BEGIN DESCRIPTION:
UNT 141 in Running Cr Watershed
END DESCRIPTION:

--- UNT 141 in Running Cr Watershed.p01 (plan) ---

Plan Title=Multiple Run
Short Identifier=Multiple
Geom File=g01
Flow File=f01
Subcritical Flow
K Sum by GR= 0
Std Step Tol= 0.01
Critical Tol= 0.01
Num of Std Step Trials= 20
Max Error Tol= 0.3
Flow Tol Ratio= 0.001
Split Flow NTrial= 30
Split Flow Tol= 0.02
Split Flow Ratio= 0.02
Log Output Level= 0
Friction Slope Method= 1
Unsteady Friction Slope Method= 2
Unsteady Bridges Friction Slope Method= 1
Parabolic Critical Depth
Global Vel Dist=  1 , 1 , 1
Global Log Level= 0
CheckData=True
Encroach Param= -1, 0, 0, 0
BEGIN DESCRIPTION:
Multiple Run
END DESCRIPTION:

--- UNT 141 in Running Cr Watershed.f01 (steady flow) ---

Flow Title=Multiple
Number of Profiles=7
Profile Names=10-year,25-year,50-year,1pct_min,100-year,1pct_plu,500-year
River Rch & RM= UNT 141 in Runni,Reach-1,2724
     204     255     295     170     339     676     448
Boundary for River Rch & Prof#=UNT 141 in Runni,Reach-1,1
Up Type=0
Dn Type=3
Dn Slope=0.005
Boundary for River Rch & Prof#=UNT 141 in Runni,Reach-1,2
Up Type=0
Dn Type=3
Dn Slope=0.005
Boundary for River Rch & Prof#=UNT 141 in Runni,Reach-1,3
Up Type=0
Dn Type=3
Dn Slope=0.005
Boundary for River Rch & Prof#=UNT 141 in Runni,Reach-1,4
Up Type=0
Dn Type=3
Dn Slope=0.005
Boundary for River Rch & Prof#=UNT 141 in Runni,Reach-1,5
Up Type=0
Dn Type=3
Dn Slope=0.005
Boundary for River Rch & Prof#=UNT 141 in Runni,Reach-1,6
Up Type=0
Dn Type=3
Dn Slope=0.005
Boundary for River Rch & Prof#=UNT 141 in Runni,Reach-1,7
Up Type=0
Dn Type=3
Dn Slope=0.005

--- UNT 141 in Running Cr Watershed.g01 (geometry) ---

Geom Title=Existing Conditions

River Reach=UNT 141 in Runni,Reach-1
Reach XY= 30
      2864456.73      7038377.02      2864598.88      7038301.12
      2864748.75      7038274.59      2864850.83      7038158.10
      2864933.64      7038154.28      2865004.65      7038125.00
      2865032.60      7038096.64      2865072.70      7038090.22
      2865171.49      7037991.26      2865272.05      7037988.80
      2865425.52      7038168.06      2865565.74      7038143.02
      2865648.82      7038175.69      2865698.99      7038147.49
      2865785.25      7038052.10      2865859.83      7038058.33
      2865925.60      7038010.60      2866109.56      7038033.18
      2866319.94      7038100.24      2866359.83      7038098.49
      2866524.20      7038043.12      2866549.45      7038044.93
      2866594.55      7038082.81      2866628.82      7038082.81
      2866729.83      7038044.93      2866811.01      7038043.12
      2866897.59      7037920.46      2866987.78      7037835.68
      2867061.74      7037808.63      2867171.77      7037796.00

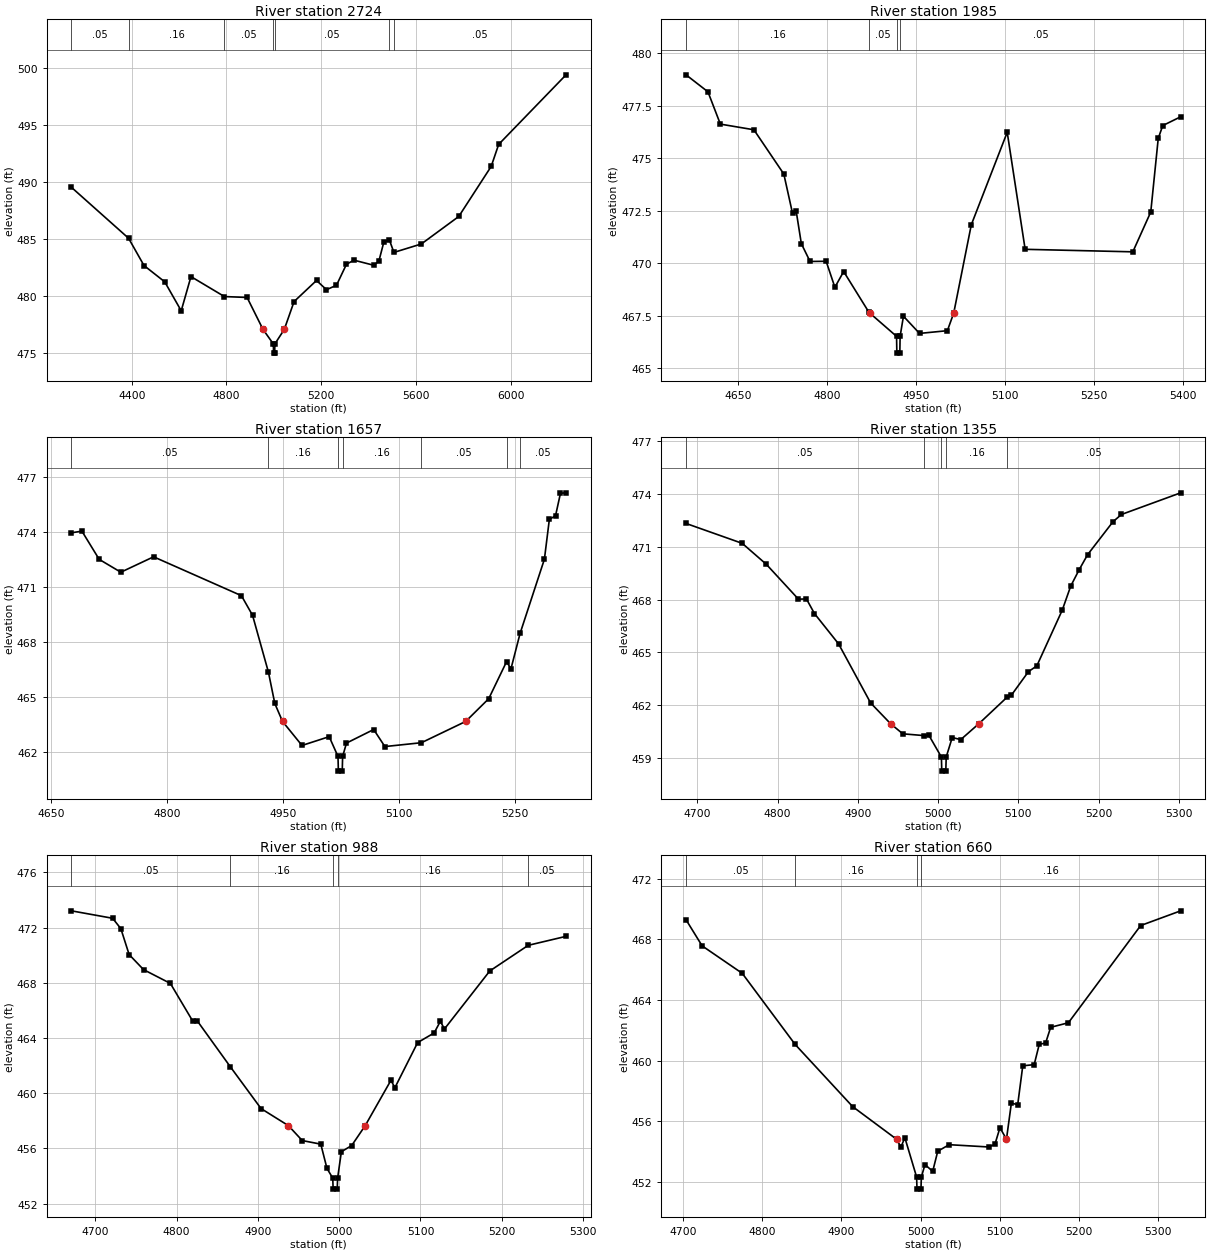
Type RM Length L Ch R = 1,2724,739,739,739
BEGIN DESCRIPTION:
UNT 141 in Running Cr Watershed 7.0
END DESCRIPTION:
XS GIS Cut Line= 3
      2864675.00      7038975.01      2864875.00      7038175.00
      2863675.04      7037775.01
#Sta/Elev= 30
  4145.1  489.52  4386.7  485.05  4451.8  482.66  4539.4  481.23  4609.0  478.69
  4650.2  481.69  4791.5  479.94  4887.3  479.86  4954.5  477.06  4998.4  475.78
  4998.9  474.98  5003.9  474.98  5004.4  475.78  5044.4  477.06  5085.7  479.50
  5180.5  481.35  5222.7  480.54  5264.9  480.93  5307.0  482.77  5338.7  483.13
  5423.0  482.68  5444.1  483.06  5465.2  484.74  5488.6  484.89  5507.5  483.81
  5623.3  484.55  5781.4  486.96  5918.4  491.35  5950.0  493.28  6234.6  499.38
#Mann=7,-1,0
  4145.1    0.05       0  4386.7    0.16       0  4791.5    0.05       0
  4998.4    0.03       0  5004.4    0.05       0  5488.6    0.08       0
  5507.5    0.05       0
Bank Sta=4954.5,5044.4
Exp/Cntr=0.3,0.1

Type RM Length L Ch R = 1,1985,328,328,328
BEGIN DESCRIPTION:
UNT 141 in Running Cr Watershed 6.0
END DESCRIPTION:
XS GIS Cut Line= 3
      2865174.99      7038525.01      2865425.00      7038175.00
      2865375.00      7037775.04
#Sta/Elev= 30
  4562.3  478.98  4599.2  478.17  4620.1  476.63  4676.6  476.36  4727.0  474.25
  4741.7  472.37  4747.9  472.47  4756.5  470.93  4771.2  470.08  4798.3  470.09
  4813.0  468.85  4827.8  469.60  4870.1  467.67  4871.8  467.62  4916.9  466.51
  4917.4  465.71  4922.4  465.71  4922.9  466.51  4928.5  467.47  4955.6  466.65
  5002.5  466.78  5013.2  467.62  5042.8  471.83  5103.3  476.24  5133.5  470.66
  5314.9  470.54  5345.1  472.44  5357.7  475.95  5365.3  476.56  5395.5  476.98
#Mann=4,-1,0
  4562.3    0.16       0  4870.1    0.05       0  4916.9    0.03       0
  4922.9    0.05       0
Bank Sta=4871.8,5013.2
Exp/Cntr=0.3,0.1

Type RM Length L Ch R = 1,1657,302,302,302
BEGIN DESCRIPTION:
UNT 141 in Running Cr Watershed 5.0
END DESCRIPTION:
XS GIS Cut Line= 3
      2865924.97      7038374.97      2865725.00      7038125.00
      2865524.98      7037874.98
#Sta/Elev= 30
  4676.0  473.97  4689.6  474.06  4712.0  472.52  4740.0  471.82  4782.4  472.66
  4896.1  470.54  4910.5  469.47  4931.1  466.36  4939.3  464.66  4949.3  463.68
  4974.5  462.37  5009.7  462.85  5021.1  461.77  5021.6  460.97  5026.6  460.97
  5027.1  461.77  5032.1  462.50  5067.3  463.24  5081.8  462.31  5129.1  462.52
  5186.4  463.68  5216.2  464.92  5239.3  466.94  5245.0  466.55  5256.8  468.48
  5288.3  472.53  5294.7  474.70  5302.7  474.90  5309.1  476.13  5316.3  476.15
#Mann=7,-1,0
  4676.0    0.05       0  4931.1    0.16       0  5021.1    0.07       0
  5027.1    0.16       0  5129.1    0.05       0  5239.3    0.16       0
  5256.8    0.05       0
Bank Sta=4949.3,5186.4
Exp/Cntr=0.3,0.1

Type RM Length L Ch R = 1,1355,367,367,367
BEGIN DESCRIPTION:
UNT 141 in Running Cr Watershed 4.0
END DESCRIPTION:
XS GIS Cut Line= 3
      2865975.00      7038325.00      2865975.00      7038025.00
      2865875.01      7037725.03
#Sta/Elev= 30
  4686.0  472.32  4756.0  471.19  4786.0  470.00  4826.0  468.02  4836.0  468.03
  4846.0  467.20  4876.0  465.48  4916.0  462.12  4940.9  460.94  4956.0  460.37
  4982.1  460.27  4988.6  460.28  5004.1  459.05  5004.6  458.25  5009.6  458.25
  5010.1  459.05  5017.6  460.16  5028.2  460.04  5050.7  460.94  5085.7  462.44
  5091.4  462.57  5112.5  463.90  5123.0  464.23  5154.7  467.40  5165.2  468.76
  5175.7  469.69  5186.3  470.55  5217.9  472.42  5228.4  472.83  5302.2  474.06
#Mann=5,-1,0
  4686.0    0.05       0  4982.1    0.16       0  5004.1    0.07       0
  5010.1    0.16       0  5085.7    0.05       0
Bank Sta=4940.9,5050.7
Exp/Cntr=0.3,0.1

Type RM Length L Ch R = 1,988,328,328,328
BEGIN DESCRIPTION:
UNT 141 in Running Cr Watershed 3.0
END DESCRIPTION:
XS GIS Cut Line= 3
      2866275.00      7038425.01      2866325.00      7038125.00
      2866275.00      7037824.99
#Sta/Elev= 30
  4670.7  473.22  4721.4  472.68  4731.5  471.93  4741.7  470.05  4759.4  468.96
  4792.4  467.96  4820.2  465.20  4825.3  465.26  4866.0  461.93  4903.9  458.89
  4937.6  457.65  4954.6  456.57  4977.4  456.31  4985.0  454.55  4992.1  453.85
  4992.6  453.05  4997.6  453.05  4998.1  453.85  5002.7  455.76  5015.4  456.21
  5032.0  457.65  5063.6  460.93  5068.6  460.41  5096.5  463.67  5116.8  464.37
  5124.4  465.21  5129.5  464.66  5185.2  468.86  5232.5  470.72  5279.0  471.37
#Mann=5,-1,0
  4670.7    0.05       0  4866.0    0.16       0  4992.1    0.07       0
  4998.1    0.16       0  5232.5    0.05       0
Bank Sta=4937.6,5032
Exp/Cntr=0.3,0.1

Type RM Length L Ch R = 1,660,391,391,391
BEGIN DESCRIPTION:
UNT 141 in Running Cr Watershed 2.0
END DESCRIPTION:
XS GIS Cut Line= 3
      2866575.00      7038374.98      2866625.00      7038075.00
      2866374.98      7037874.98
#Sta/Elev= 30
  4703.8  469.28  4724.1  467.56  4774.7  465.75  4841.5  461.06  4914.1  456.96
  4969.5  454.81  4975.0  454.30  4980.0  454.91  4994.8  452.32  4995.3  451.52
  5000.3  451.52  5000.8  452.32  5005.4  453.14  5015.1  452.69  5021.5  454.02
  5035.9  454.45  5085.6  454.30  5093.6  454.47  5100.0  455.57  5108.2  454.81
  5114.4  457.19  5122.4  457.09  5128.8  459.65  5143.2  459.73  5149.6  461.07
  5157.6  461.15  5164.0  462.19  5186.4  462.49  5277.6  468.90  5328.1  469.87
#Mann=4,-1,0
  4703.8    0.05       0  4841.5    0.16       0  4994.8    0.07       0
  5000.8    0.16       0
Bank Sta=4969.5,5108.2
Exp/Cntr=0.3,0.1

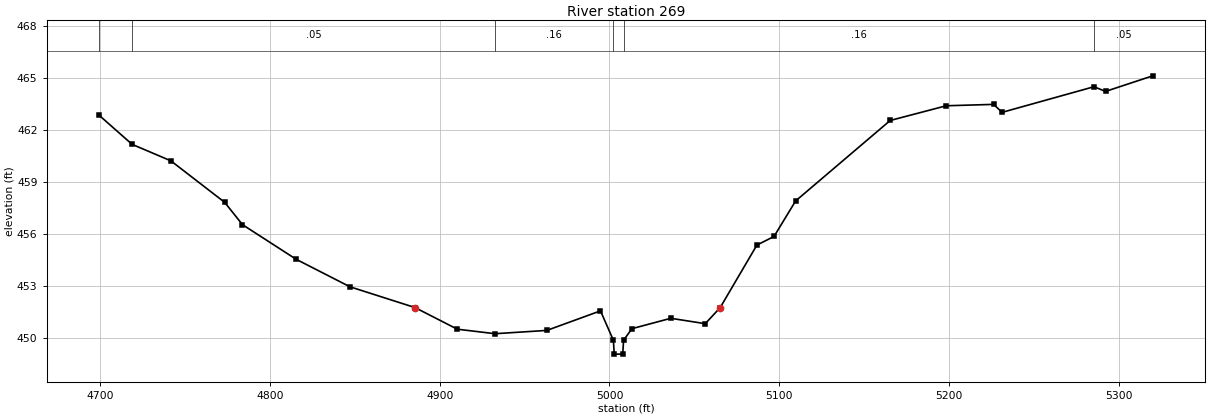
Type RM Length L Ch R = 1,269,0,0,0
BEGIN DESCRIPTION:
UNT 141 in Running Cr Watershed 1.0
END DESCRIPTION:
XS GIS Cut Line= 3
      2867024.99      7038174.98      2866925.00      7037875.00
      2866625.05      7037825.01
#Sta/Elev= 30
  4699.6  462.83  4718.9  461.16  4741.7  460.21  4773.4  457.81  4783.9  456.52
  4815.5  454.52  4847.2  452.93  4885.5  451.73  4910.4  450.48  4932.6  450.22
  4963.1  450.41  4994.7  451.54  5002.3  449.84  5002.8  449.04  5007.8  449.04
  5008.3  449.84  5013.2  450.51  5036.1  451.11  5056.4  450.80  5065.2  451.73
  5086.8  455.34  5096.9  455.84  5109.6  457.89  5165.3  462.54  5198.3  463.39
  5226.2  463.47  5231.2  463.01  5285.3  464.49  5292.1  464.22  5319.9  465.12
#Mann=6,-1,0
  4699.6    0.16       0  4718.9    0.05       0  4932.6    0.16       0
  5002.3    0.07       0  5008.3    0.16       0  5285.3    0.05       0
Bank Sta=4885.5,5065.2
Exp/Cntr=0.3,0.1

Chan Stop Cuts=-1