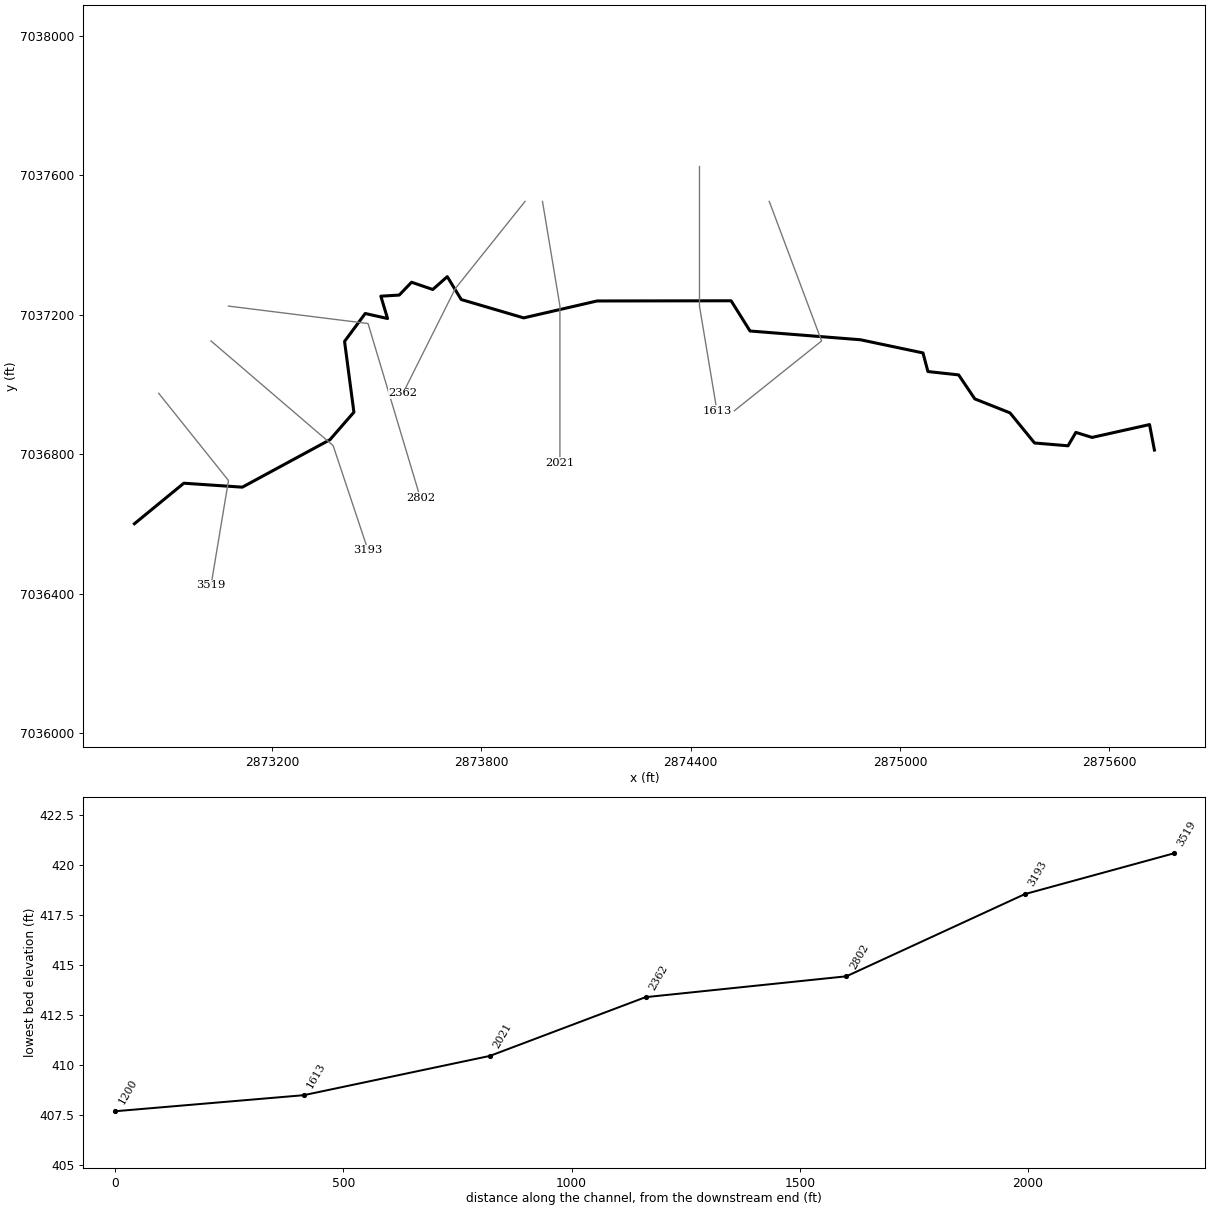
--- UNT 142 in Running Cr Watershed.prj (project) ---

Proj Title=UNT 142 in Running Cr Watershed Base Level Engineering
Current Plan=p01
Default Exp/Contr=0.3,0.1
English Units
Geom File=g01
Flow File=f01
Plan File=p01
BEGIN DESCRIPTION:
UNT 142 in Running Cr Watershed
END DESCRIPTION:

--- UNT 142 in Running Cr Watershed.p01 (plan) ---

Plan Title=Multiple Run
Short Identifier=Multiple
Geom File=g01
Flow File=f01
Subcritical Flow
K Sum by GR= 0
Std Step Tol= 0.01
Critical Tol= 0.01
Num of Std Step Trials= 20
Max Error Tol= 0.3
Flow Tol Ratio= 0.001
Split Flow NTrial= 30
Split Flow Tol= 0.02
Split Flow Ratio= 0.02
Log Output Level= 0
Friction Slope Method= 1
Unsteady Friction Slope Method= 2
Unsteady Bridges Friction Slope Method= 1
Parabolic Critical Depth
Global Vel Dist=  1 , 1 , 1
Global Log Level= 0
CheckData=True
Encroach Param= -1, 0, 0, 0
BEGIN DESCRIPTION:
Multiple Run
END DESCRIPTION:

--- UNT 142 in Running Cr Watershed.f01 (steady flow) ---

Flow Title=Multiple
Number of Profiles=7
Profile Names=10-year,25-year,50-year,1pct_min,100-year,1pct_plu,500-year
River Rch & RM= UNT 142 in Runni,Reach-1,3519
     514     683     819     489     975    1946    1385
Boundary for River Rch & Prof#=UNT 142 in Runni,Reach-1,1
Up Type=0
Dn Type=3
Dn Slope=0.005
Boundary for River Rch & Prof#=UNT 142 in Runni,Reach-1,2
Up Type=0
Dn Type=3
Dn Slope=0.005
Boundary for River Rch & Prof#=UNT 142 in Runni,Reach-1,3
Up Type=0
Dn Type=3
Dn Slope=0.005
Boundary for River Rch & Prof#=UNT 142 in Runni,Reach-1,4
Up Type=0
Dn Type=3
Dn Slope=0.005
Boundary for River Rch & Prof#=UNT 142 in Runni,Reach-1,5
Up Type=0
Dn Type=3
Dn Slope=0.005
Boundary for River Rch & Prof#=UNT 142 in Runni,Reach-1,6
Up Type=0
Dn Type=3
Dn Slope=0.005
Boundary for River Rch & Prof#=UNT 142 in Runni,Reach-1,7
Up Type=0
Dn Type=3
Dn Slope=0.005

--- UNT 142 in Running Cr Watershed.g01 (geometry) ---

Geom Title=Existing Conditions

River Reach=UNT 142 in Runni,Reach-1
Reach XY= 30
      2872805.38      7036601.12      2872947.00      7036717.29
      2873114.70      7036705.95      2873365.77      7036841.93
      2873434.48      7036920.83      2873407.70      7037123.75
      2873466.91      7037203.75      2873530.91      7037189.35
      2873511.71      7037253.36      2873564.51      7037256.56
      2873599.71      7037293.36      2873660.52      7037272.56
      2873702.12      7037309.36      2873742.12      7037243.75
      2873921.09      7037191.18      2874131.36      7037239.65
      2874515.63      7037240.19      2874569.88      7037153.56
      2874886.27      7037128.48      2875065.59      7037090.71
      2875079.79      7037037.34      2875167.80      7037027.74
      2875214.20      7036958.94      2875315.00      7036918.94
      2875385.41      7036832.53      2875481.41      7036824.53
      2875503.81      7036862.93      2875550.22      7036848.53
      2875715.02      7036885.34      2875728.97      7036812.35

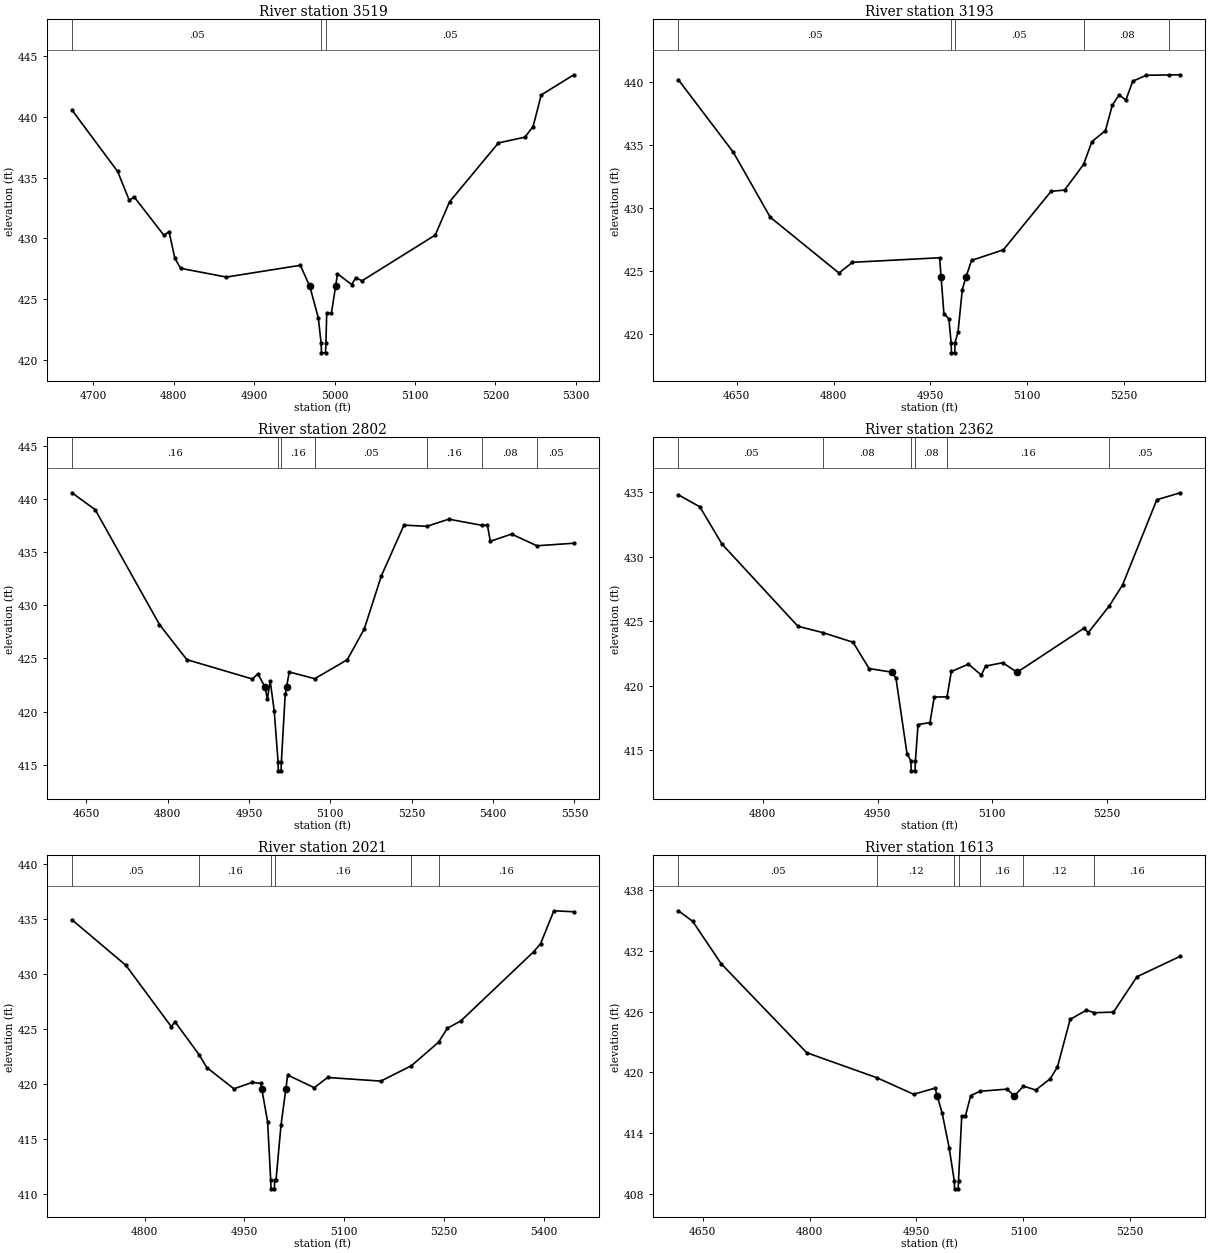
Type RM Length L Ch R = 1,3519,326,326,326
BEGIN DESCRIPTION:
UNT 142 in Running Cr Watershed 7.0
END DESCRIPTION:
XS GIS Cut Line= 3
      2872875.01      7036974.99      2873075.00      7036725.00
      2873025.00      7036424.98
#Sta/Elev= 30
  4673.3  440.56  4730.1  435.50  4744.5  433.14  4750.9  433.38  4787.7  430.24
  4794.1  430.54  4801.3  428.34  4808.5  427.52  4865.4  426.80  4957.4  427.77
  4969.2  426.03  4979.8  423.42  4983.2  421.36  4983.7  420.56  4988.7  420.56
  4989.2  421.36  4990.2  423.81  4996.0  423.81  5001.2  426.03  5003.6  427.07
  5021.3  426.18  5026.4  426.76  5034.0  426.49  5125.2  430.26  5143.0  433.00
  5203.8  437.85  5236.7  438.32  5246.9  439.20  5257.0  441.80  5297.6  443.46
#Mann=3,-1,0
  4673.3    0.05       0  4983.2    0.03       0  4989.2    0.05       0
Bank Sta=4969.2,5001.2
Exp/Cntr=0.3,0.1

Type RM Length L Ch R = 1,3193,391,391,391
BEGIN DESCRIPTION:
UNT 142 in Running Cr Watershed 6.0
END DESCRIPTION:
XS GIS Cut Line= 3
      2873024.97      7037125.02      2873375.00      7036825.00
      2873474.99      7036525.04
#Sta/Elev= 30
  4559.7  440.15  4644.8  434.41  4701.9  429.27  4808.3  424.85  4829.2  425.70
  4964.2  426.06  4966.5  424.50  4970.8  421.64  4978.5  421.23  4982.0  419.33
  4982.5  418.53  4987.5  418.53  4988.0  419.33  4992.7  420.18  4999.3  423.54
  5004.8  424.50  5013.6  425.85  5062.9  426.69  5136.7  431.32  5157.7  431.42
  5187.1  433.45  5199.9  435.25  5221.0  436.13  5231.5  438.13  5242.1  438.96
  5252.6  438.55  5263.2  440.04  5284.2  440.51  5319.8  440.54  5336.9  440.55
#Mann=5,-1,0
  4559.7    0.05       0  4982.0    0.03       0  4988.0    0.05       0
  5187.1    0.08       0  5319.8    0.05       0
Bank Sta=4966.5,5004.8
Exp/Cntr=0.3,0.1

Type RM Length L Ch R = 1,2802,440,440,440
BEGIN DESCRIPTION:
UNT 142 in Running Cr Watershed 5.0
END DESCRIPTION:
XS GIS Cut Line= 3
      2873074.97      7037225.00      2873475.00      7037175.00
      2873625.01      7036674.96
#Sta/Elev= 30
  4623.7  440.56  4666.6  438.97  4785.0  428.18  4835.4  424.88  4956.3  423.06
  4966.4  423.55  4979.2  422.34  4984.0  421.18  4989.1  422.89  4996.6  420.05
  5003.7  415.23  5004.2  414.43  5009.2  414.43  5009.7  415.23  5016.8  421.61
  5019.4  422.34  5024.3  423.72  5071.3  423.09  5131.2  424.87  5162.6  427.77
  5193.9  432.73  5235.7  437.52  5278.0  437.41  5318.3  438.08  5379.4  437.50
  5389.6  437.50  5394.9  436.00  5434.0  436.68  5480.8  435.58  5548.9  435.82
#Mann=7,-1,0
  4623.7    0.16       0  5003.7    0.07       0  5009.7    0.16       0
  5071.3    0.05       0  5278.0    0.16       0  5379.4    0.08       0
  5480.8    0.05       0
Bank Sta=4979.2,5019.4
Exp/Cntr=0.3,0.1

Type RM Length L Ch R = 1,2362,341,341,341
BEGIN DESCRIPTION:
UNT 142 in Running Cr Watershed 4.0
END DESCRIPTION:
XS GIS Cut Line= 3
      2873925.02      7037525.03      2873725.00      7037275.00
      2873575.00      7036975.00
#Sta/Elev= 30
  4689.9  434.81  4717.9  433.88  4746.8  430.99  4846.0  424.61  4878.4  424.12
  4918.0  423.37  4938.9  421.33  4969.4  421.04  4974.1  420.56  4988.5  414.72
  4993.5  414.19  4994.0  413.39  4999.0  413.39  4999.5  414.19  5002.9  416.98
  5018.5  417.14  5024.1  419.12  5040.8  419.13  5046.4  421.10  5068.8  421.67
  5085.6  420.82  5091.1  421.52  5113.5  421.78  5132.3  421.04  5219.7  424.46
  5225.3  424.12  5252.5  426.17  5270.0  427.81  5314.8  434.43  5345.5  434.97
#Mann=6,-1,0
  4689.9    0.05       0  4878.4    0.08       0  4993.5    0.07       0
  4999.5    0.08       0  5040.8    0.16       0  5252.5    0.05       0
Bank Sta=4969.4,5132.3
Exp/Cntr=0.3,0.1

Type RM Length L Ch R = 1,2021,408,408,408
BEGIN DESCRIPTION:
UNT 142 in Running Cr Watershed 3.0
END DESCRIPTION:
XS GIS Cut Line= 3
      2873975.00      7037524.98      2874025.00      7037225.00
      2874025.00      7036775.02
#Sta/Elev= 30
  4690.8  434.96  4771.9  430.81  4840.3  425.21  4845.4  425.69  4881.9  422.67
  4893.5  421.50  4934.1  419.57  4962.0  420.16  4974.6  420.06  4976.0  419.57
  4984.8  416.56  4989.4  411.26  4989.9  410.46  4994.9  410.46  4995.4  411.26
  4997.4  411.26  5004.9  416.26  5012.2  419.57  5014.9  420.82  5054.9  419.67
  5074.9  420.60  5154.9  420.27  5200.8  421.67  5241.6  423.81  5254.9  425.09
  5274.9  425.74  5384.9  432.07  5394.9  432.78  5414.9  435.78  5444.9  435.69
#Mann=6,-1,0
  4690.8    0.05       0  4881.9    0.16       0  4989.4    0.07       0
  4995.4    0.16       0  5200.8    0.12       0  5241.6    0.16       0
Bank Sta=4976,5012.2
Exp/Cntr=0.3,0.1

Type RM Length L Ch R = 1,1613,413,413,413
BEGIN DESCRIPTION:
UNT 142 in Running Cr Watershed 2.0
END DESCRIPTION:
XS GIS Cut Line= 3
      2874425.00      7037625.02      2874425.00      7037225.00
      2874475.01      7036924.96
#Sta/Elev= 30
  4616.0  435.97  4636.0  434.93  4676.0  430.74  4796.0  421.95  4894.7  419.47
  4946.0  417.84  4976.0  418.45  4979.2  417.67  4986.0  415.99  4996.0  412.51
  5003.0  409.30  5003.5  408.50  5008.5  408.50  5009.0  409.30  5013.5  415.68
  5018.6  415.68  5026.2  417.72  5039.4  418.14  5076.9  418.35  5087.4  417.67
  5100.0  418.65  5117.4  418.26  5137.7  419.38  5147.8  420.54  5165.6  425.24
  5188.4  426.15  5199.6  425.90  5226.4  425.96  5259.3  429.45  5320.2  431.48
#Mann=7,-1,0
  4616.0    0.05       0  4894.7    0.12       0  5003.0    0.07       0
  5009.0    0.12       0  5039.4    0.16       0  5100.0    0.12       0
  5199.6    0.16       0
Bank Sta=4979.2,5087.4
Exp/Cntr=0.3,0.1

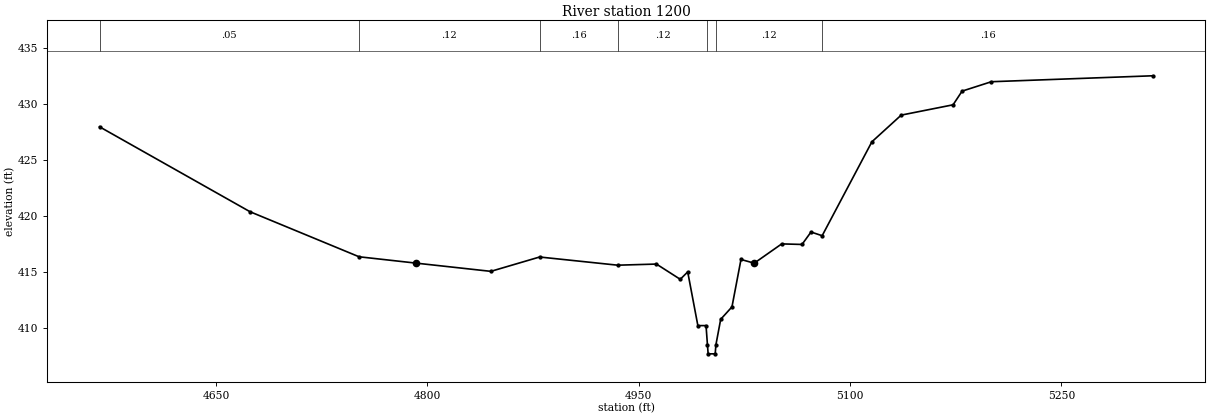
Type RM Length L Ch R = 1,1200,0,0,0
BEGIN DESCRIPTION:
UNT 142 in Running Cr Watershed 1.0
END DESCRIPTION:
XS GIS Cut Line= 3
      2874624.99      7037525.03      2874775.00      7037125.00
      2874524.99      7036924.99
#Sta/Elev= 30
  4567.4  427.96  4674.2  420.38  4751.6  416.36  4792.3  415.79  4845.1  415.06
  4879.7  416.34  4935.1  415.61  4962.6  415.71  4979.5  414.35  4984.8  415.01
  4992.0  410.22  4997.8  410.22  4998.8  408.50  4999.3  407.70  5004.3  407.70
  5004.8  408.50  5008.2  410.78  5016.2  411.89  5022.6  416.12  5032.0  415.79
  5051.5  417.51  5065.9  417.46  5072.3  418.57  5080.2  418.24  5115.5  426.62
  5136.3  429.00  5173.1  429.92  5179.5  431.14  5200.3  431.98  5314.8  432.51
#Mann=7,-1,0
  4567.4    0.05       0  4751.6    0.12       0  4879.7    0.16       0
  4935.1    0.12       0  4998.8    0.07       0  5004.8    0.12       0
  5080.2    0.16       0
Bank Sta=4792.3,5032
Exp/Cntr=0.3,0.1

Chan Stop Cuts=-1