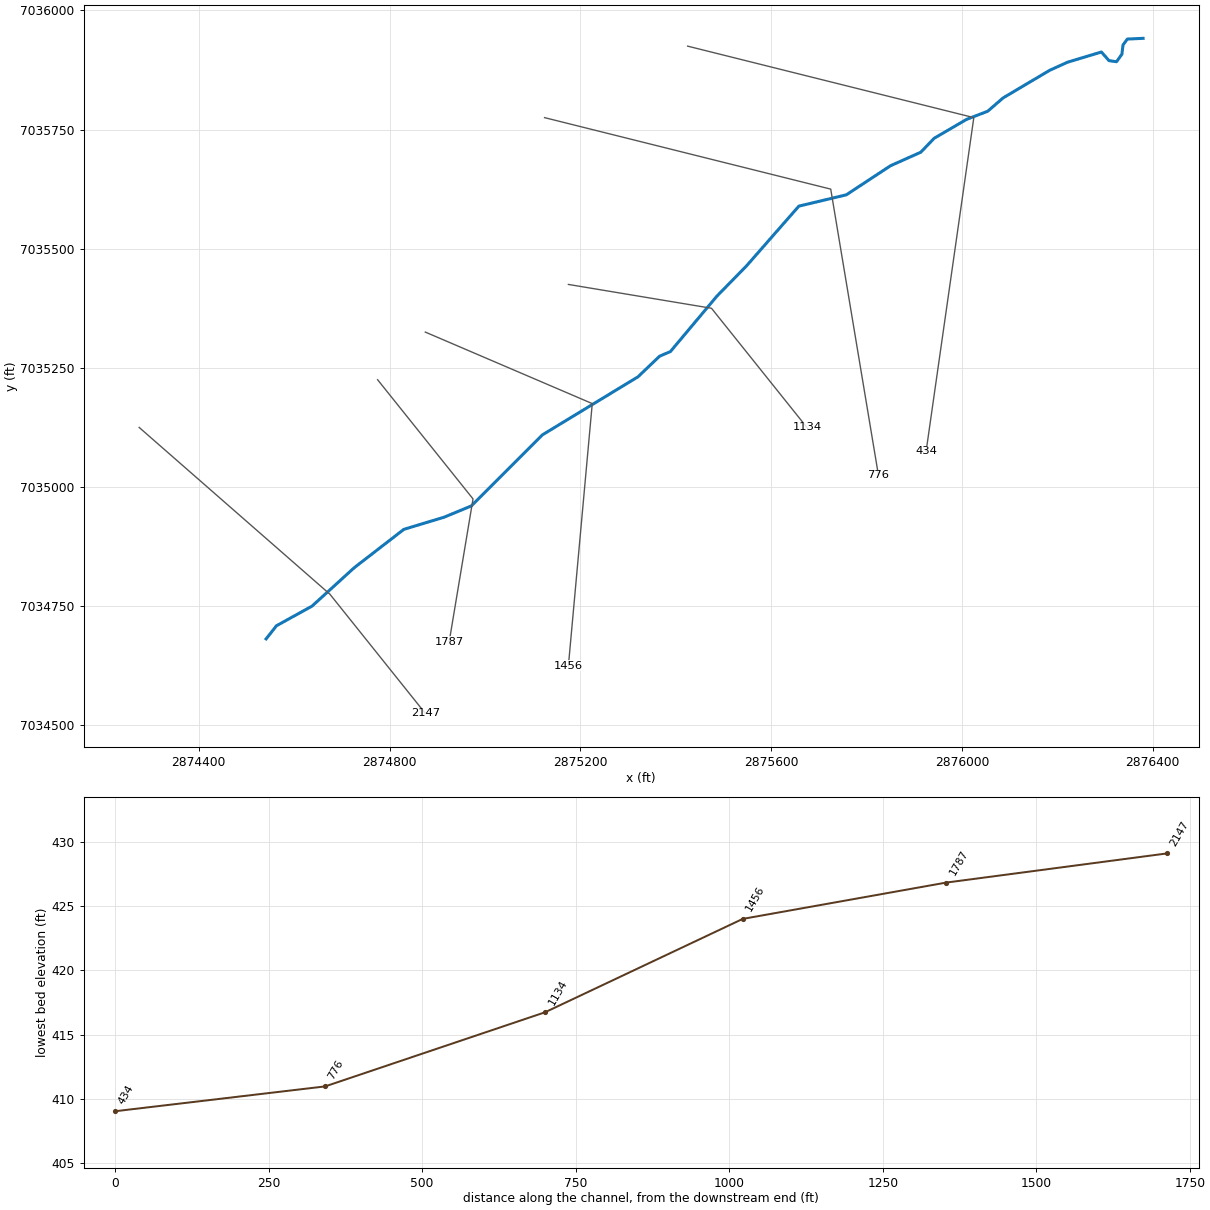
--- UNT 143 in Running Cr Watershed.prj (project) ---

Proj Title=UNT 143 in Running Cr Watershed Base Level Engineering
Current Plan=p01
Default Exp/Contr=0.3,0.1
English Units
Geom File=g01
Flow File=f01
Plan File=p01
BEGIN DESCRIPTION:
UNT 143 in Running Cr Watershed
END DESCRIPTION:

--- UNT 143 in Running Cr Watershed.p01 (plan) ---

Plan Title=Multiple Run
Short Identifier=Multiple
Geom File=g01
Flow File=f01
Subcritical Flow
K Sum by GR= 0
Std Step Tol= 0.01
Critical Tol= 0.01
Num of Std Step Trials= 20
Max Error Tol= 0.3
Flow Tol Ratio= 0.001
Split Flow NTrial= 30
Split Flow Tol= 0.02
Split Flow Ratio= 0.02
Log Output Level= 0
Friction Slope Method= 1
Unsteady Friction Slope Method= 2
Unsteady Bridges Friction Slope Method= 1
Parabolic Critical Depth
Global Vel Dist=  1 , 1 , 1
Global Log Level= 0
CheckData=True
Encroach Param= -1, 0, 0, 0
BEGIN DESCRIPTION:
Multiple Run
END DESCRIPTION:

--- UNT 143 in Running Cr Watershed.f01 (steady flow) ---

Flow Title=Multiple
Number of Profiles=7
Profile Names=10-year,25-year,50-year,1pct_min,100-year,1pct_plu,500-year
River Rch & RM= UNT 143 in Runni,Reach-1,2147
     240     305     355     206     412     821     553
Boundary for River Rch & Prof#=UNT 143 in Runni,Reach-1,1
Up Type=0
Dn Type=3
Dn Slope=0.005
Boundary for River Rch & Prof#=UNT 143 in Runni,Reach-1,2
Up Type=0
Dn Type=3
Dn Slope=0.005
Boundary for River Rch & Prof#=UNT 143 in Runni,Reach-1,3
Up Type=0
Dn Type=3
Dn Slope=0.005
Boundary for River Rch & Prof#=UNT 143 in Runni,Reach-1,4
Up Type=0
Dn Type=3
Dn Slope=0.005
Boundary for River Rch & Prof#=UNT 143 in Runni,Reach-1,5
Up Type=0
Dn Type=3
Dn Slope=0.005
Boundary for River Rch & Prof#=UNT 143 in Runni,Reach-1,6
Up Type=0
Dn Type=3
Dn Slope=0.005
Boundary for River Rch & Prof#=UNT 143 in Runni,Reach-1,7
Up Type=0
Dn Type=3
Dn Slope=0.005

--- UNT 143 in Running Cr Watershed.g01 (geometry) ---

Geom Title=Existing Conditions

River Reach=UNT 143 in Runni,Reach-1
Reach XY= 30
      2874541.25      7034681.31      2874562.86      7034708.81
      2874637.50      7034750.05      2874725.88      7034830.58
      2874829.98      7034911.11      2874914.44      7034936.64
      2874971.40      7034960.21      2875120.67      7035109.49
      2875321.01      7035231.26      2875366.07      7035274.36
      2875388.86      7035284.16      2875486.67      7035400.80
      2875548.05      7035463.50      2875658.17      7035589.27
      2875757.68      7035613.02      2875850.41      7035674.08
      2875913.73      7035702.35      2875942.00      7035731.76
      2876009.85      7035771.33      2876053.95      7035788.30
      2876086.75      7035816.57      2876184.00      7035874.24
      2876221.31      7035891.20      2876292.55      7035912.68
      2876308.38      7035894.59      2876324.22      7035892.33
      2876335.52      7035908.16      2876337.79      7035927.38
      2876346.83      7035939.82      2876379.85      7035941.37

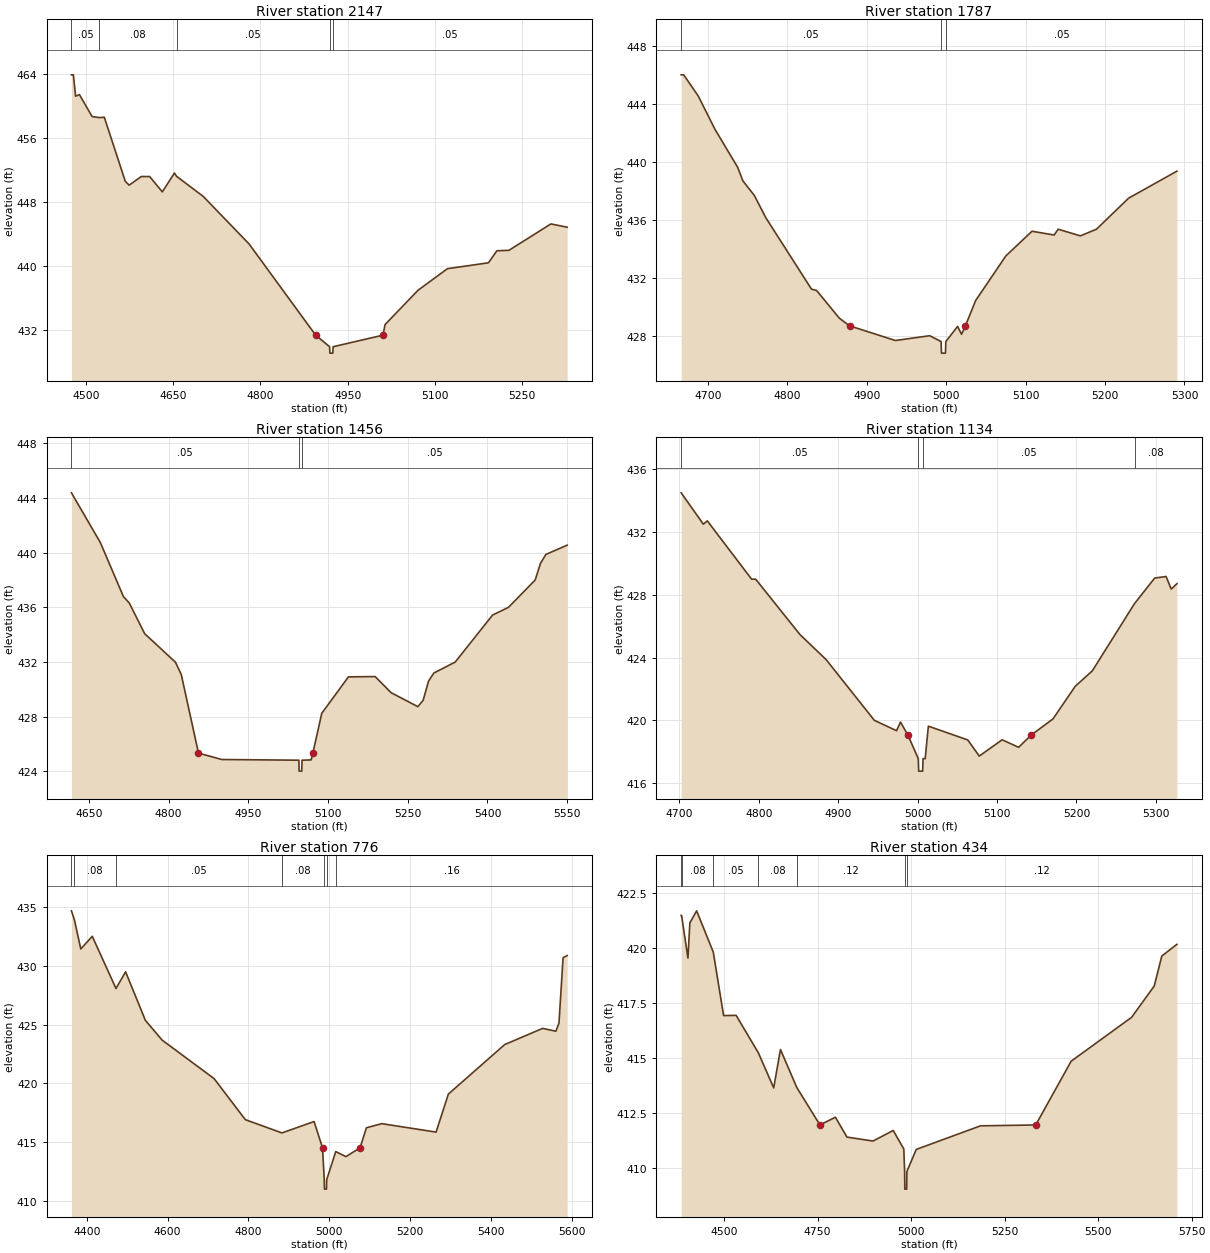
Type RM Length L Ch R = 1,2147,360,360,360
BEGIN DESCRIPTION:
UNT 143 in Running Cr Watershed 6.0
END DESCRIPTION:
XS GIS Cut Line= 3
      2874275.03      7035124.97      2874675.00      7034775.00
      2874874.99      7034525.01
#Sta/Elev= 30
  4475.4  463.91  4478.7  463.91  4482.5  461.24  4489.1  461.44  4510.9  458.69
  4523.2  458.56  4531.8  458.61  4567.9  450.59  4574.5  450.11  4595.4  451.19
  4609.7  451.19  4631.5  449.27  4652.4  451.63  4655.9  451.22  4701.7  448.71
  4780.5  442.76  4894.9  431.35  4918.9  429.90  4919.4  429.10  4924.4  429.10
  4924.9  429.90  5010.7  431.35  5014.1  432.67  5070.9  436.97  5121.3  439.66
  5191.8  440.40  5206.2  441.90  5227.0  441.96  5299.0  445.26  5327.0  444.85
#Mann=5,-1,0
  4475.4    0.05       0  4523.2    0.08       0  4655.9    0.05       0
  4918.9    0.03       0  4924.9    0.05       0
Bank Sta=4894.9,5010.7
Exp/Cntr=0.3,0.1

Type RM Length L Ch R = 1,1787,331,331,331
BEGIN DESCRIPTION:
UNT 143 in Running Cr Watershed 5.0
END DESCRIPTION:
XS GIS Cut Line= 3
      2874774.98      7035225.03      2874975.00      7034975.00
      2874925.01      7034675.03
#Sta/Elev= 30
  4666.2  446.01  4669.4  446.01  4687.8  444.54  4708.7  442.26  4737.5  439.62
  4743.9  438.70  4758.3  437.70  4772.7  436.17  4830.3  431.24  4836.7  431.15
  4865.5  429.23  4878.3  428.71  4936.0  427.70  4979.2  428.03  4993.5  427.63
  4994.0  426.83  4999.0  426.83  4999.5  427.63  5014.3  428.67  5019.3  428.13
  5024.1  428.71  5037.1  430.46  5075.1  433.53  5108.0  435.23  5135.9  434.97
  5141.0  435.37  5168.9  434.91  5189.2  435.37  5229.7  437.51  5290.5  439.37
#Mann=3,-1,0
  4666.2    0.05       0  4993.5    0.03       0  4999.5    0.05       0
Bank Sta=4878.3,5024.1
Exp/Cntr=0.3,0.1

Type RM Length L Ch R = 1,1456,322,322,322
BEGIN DESCRIPTION:
UNT 143 in Running Cr Watershed 4.0
END DESCRIPTION:
XS GIS Cut Line= 3
      2874875.02      7035324.99      2875225.00      7035175.00
      2875175.00      7034625.04
#Sta/Elev= 30
  4617.0  444.38  4671.4  440.74  4714.9  436.78  4725.8  436.32  4754.8  434.07
  4812.8  431.98  4823.7  431.08  4856.1  425.33  4899.9  424.86  5045.0  424.81
  5045.5  424.01  5050.5  424.01  5051.0  424.81  5068.1  424.83  5071.4  425.33
  5088.1  428.24  5138.3  430.91  5188.6  430.93  5218.7  429.75  5268.9  428.73
  5278.9  429.19  5289.0  430.59  5299.0  431.19  5339.2  431.99  5409.5  435.43
  5439.6  436.00  5489.8  438.00  5499.8  439.22  5509.9  439.87  5550.0  440.55
#Mann=3,-1,0
  4617.0    0.05       0  5045.0    0.03       0  5051.0    0.05       0
Bank Sta=4856.1,5071.4
Exp/Cntr=0.3,0.1

Type RM Length L Ch R = 1,1134,358,358,358
BEGIN DESCRIPTION:
UNT 143 in Running Cr Watershed 3.0
END DESCRIPTION:
XS GIS Cut Line= 3
      2875175.02      7035425.00      2875475.00      7035375.00
      2875675.02      7035124.98
#Sta/Elev= 30
  4702.2  434.51  4730.1  432.51  4735.1  432.72  4790.9  429.00  4796.0  429.00
  4851.7  425.47  4884.7  423.87  4945.5  419.99  4973.4  419.33  4978.4  419.88
  4987.8  419.04  5000.8  417.55  5001.3  416.75  5006.3  416.75  5006.8  417.55
  5009.5  417.55  5013.5  419.62  5063.1  418.74  5077.6  417.71  5106.4  418.75
  5127.2  418.27  5142.7  419.04  5170.4  420.08  5198.4  422.16  5220.0  423.15
  5273.1  427.44  5298.5  429.07  5312.9  429.17  5319.3  428.37  5326.5  428.71
#Mann=4,-1,0
  4702.2    0.05       0  5000.8    0.03       0  5006.8    0.05       0
  5273.1    0.08       0
Bank Sta=4987.8,5142.7
Exp/Cntr=0.3,0.1

Type RM Length L Ch R = 1,776,342,342,342
BEGIN DESCRIPTION:
UNT 143 in Running Cr Watershed 2.0
END DESCRIPTION:
XS GIS Cut Line= 3
      2875125.05      7035774.99      2875725.00      7035625.00
      2875825.00      7035024.99
#Sta/Elev= 30
  4362.3  434.71  4369.8  433.92  4385.4  431.46  4413.8  432.54  4472.5  428.09
  4496.3  429.51  4545.2  425.38  4586.4  423.70  4715.3  420.41  4792.6  416.91
  4883.2  415.78  4962.7  416.75  4983.6  414.51  4987.9  411.79  4988.4  410.99
  4993.4  410.99  4993.9  411.79  5016.3  414.19  5041.5  413.76  5076.5  414.51
  5092.2  416.22  5130.3  416.57  5264.6  415.85  5295.0  419.09  5434.4  423.31
  5528.2  424.69  5561.1  424.45  5568.7  425.14  5578.9  430.72  5589.0  430.90
#Mann=7,-1,0
  4362.3    0.05       0  4369.8    0.08       0  4472.5    0.05       0
  4883.2    0.08       0  4987.9    0.07       0  4993.9    0.08       0
  5016.3    0.16       0
Bank Sta=4983.6,5076.5
Exp/Cntr=0.3,0.1

Type RM Length L Ch R = 1,434,0,0,0
BEGIN DESCRIPTION:
UNT 143 in Running Cr Watershed 1.0
END DESCRIPTION:
XS GIS Cut Line= 3
      2875424.96      7035925.01      2876025.00      7035775.00
      2875925.00      7035075.01
#Sta/Elev= 30
  4385.0  421.47  4386.0  421.47  4403.1  419.54  4408.2  421.13  4426.3  421.68
  4470.8  419.81  4498.4  416.93  4531.9  416.94  4591.4  415.24  4632.4  413.65
  4650.5  415.39  4694.1  413.67  4756.1  411.97  4797.4  412.32  4828.3  411.42
  4897.9  411.24  4952.0  411.72  4980.3  410.88  4982.5  409.86  4983.0  409.06
  4988.0  409.06  4988.5  409.86  5013.6  410.86  5185.3  411.93  5333.1  411.97
  5427.8  414.86  5589.4  416.85  5650.0  418.27  5670.2  419.63  5710.6  420.16
#Mann=7,-1,0
  4385.0    0.05       0  4386.0    0.08       0  4470.8    0.05       0
  4591.4    0.08       0  4694.1    0.12       0  4982.5    0.07       0
  4988.5    0.12       0
Bank Sta=4756.1,5333.1
Exp/Cntr=0.3,0.1

Chan Stop Cuts=-1