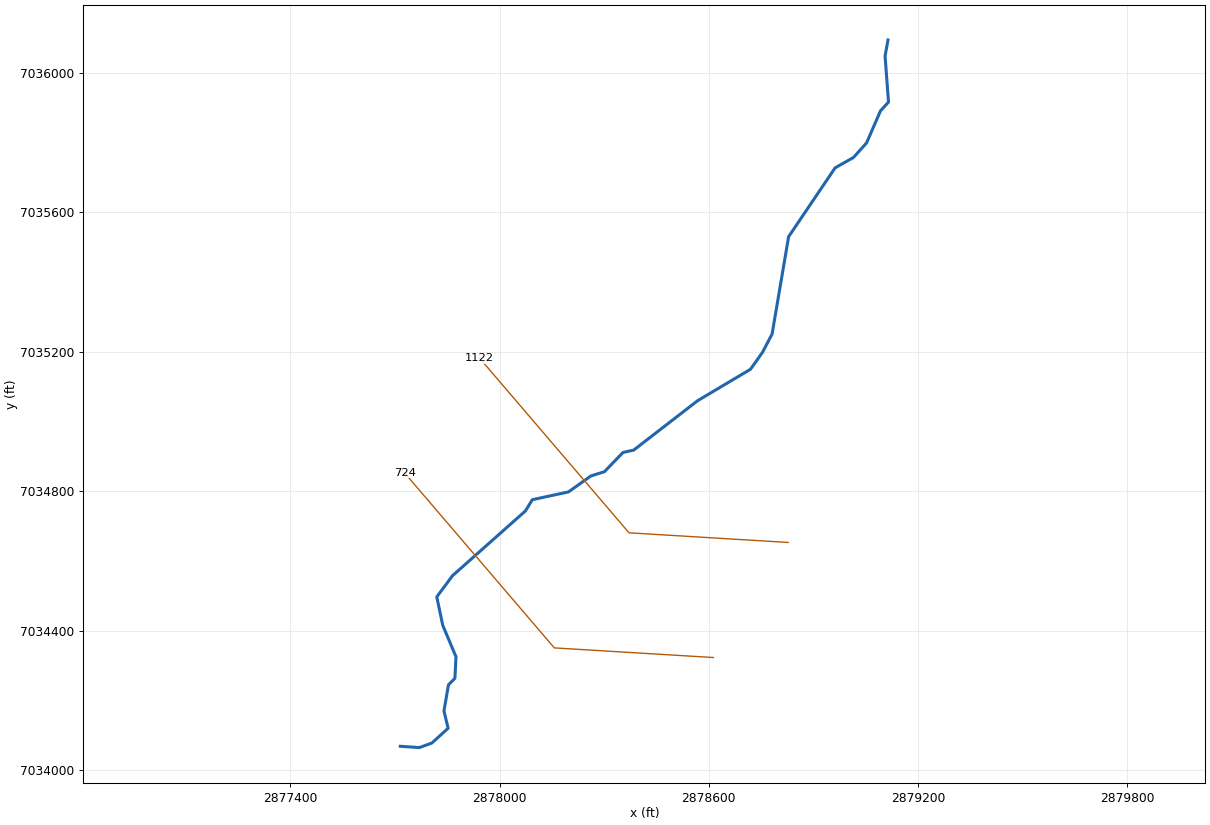
--- UNT 144 in Running Cr Watershed.prj (project) ---

Proj Title=UNT 144 in Running Cr Watershed Base Level Engineering
Current Plan=p01
Default Exp/Contr=0.3,0.1
English Units
Geom File=g01
Flow File=f01
Plan File=p01
BEGIN DESCRIPTION:
UNT 144 in Running Cr Watershed
END DESCRIPTION:

--- UNT 144 in Running Cr Watershed.p01 (plan) ---

Plan Title=Multiple Run
Short Identifier=Multiple
Geom File=g01
Flow File=f01
Subcritical Flow
K Sum by GR= 0
Std Step Tol= 0.01
Critical Tol= 0.01
Num of Std Step Trials= 20
Max Error Tol= 0.3
Flow Tol Ratio= 0.001
Split Flow NTrial= 30
Split Flow Tol= 0.02
Split Flow Ratio= 0.02
Log Output Level= 0
Friction Slope Method= 1
Unsteady Friction Slope Method= 2
Unsteady Bridges Friction Slope Method= 1
Parabolic Critical Depth
Global Vel Dist=  1 , 1 , 1
Global Log Level= 0
CheckData=True
Encroach Param= -1, 0, 0, 0
BEGIN DESCRIPTION:
Multiple Run
END DESCRIPTION:

--- UNT 144 in Running Cr Watershed.f01 (steady flow) ---

Flow Title=Multiple
Number of Profiles=7
Profile Names=10-year,25-year,50-year,1pct_min,100-year,1pct_plu,500-year
River Rch & RM= UNT 144 in Runni,Reach-1,1122
     143     174     196     110     220     439     277
Boundary for River Rch & Prof#=UNT 144 in Runni,Reach-1,1
Up Type=0
Dn Type=3
Dn Slope=0.005
Boundary for River Rch & Prof#=UNT 144 in Runni,Reach-1,2
Up Type=0
Dn Type=3
Dn Slope=0.005
Boundary for River Rch & Prof#=UNT 144 in Runni,Reach-1,3
Up Type=0
Dn Type=3
Dn Slope=0.005
Boundary for River Rch & Prof#=UNT 144 in Runni,Reach-1,4
Up Type=0
Dn Type=3
Dn Slope=0.005
Boundary for River Rch & Prof#=UNT 144 in Runni,Reach-1,5
Up Type=0
Dn Type=3
Dn Slope=0.005
Boundary for River Rch & Prof#=UNT 144 in Runni,Reach-1,6
Up Type=0
Dn Type=3
Dn Slope=0.005
Boundary for River Rch & Prof#=UNT 144 in Runni,Reach-1,7
Up Type=0
Dn Type=3
Dn Slope=0.005

--- UNT 144 in Running Cr Watershed.g01 (geometry) ---

Geom Title=Existing Conditions

River Reach=UNT 144 in Runni,Reach-1
Reach XY= 30
      2879113.69      7036093.45      2879105.36      7036047.09
      2879115.26      7035915.32      2879092.34      7035890.32
      2879052.24      7035798.14      2879014.74      7035756.47
      2878962.13      7035726.78      2878828.80      7035529.39
      2878781.40      7035250.22      2878753.80      7035197.62
      2878719.42      7035149.18      2878567.86      7035059.07
      2878384.53      7034917.41      2878353.80      7034910.64
      2878300.67      7034855.43      2878262.13      7034843.45
      2878197.58      7034797.58      2878093.90      7034775.22
      2878074.11      7034742.93      2877865.26      7034557.51
      2877819.94      7034496.57      2877837.13      7034414.80
      2877875.00      7034325.00      2877871.98      7034263.02
      2877853.54      7034244.58      2877840.52      7034169.71
      2877852.45      7034119.79      2877805.79      7034077.48
      2877769.99      7034064.46      2877715.37      7034068.22

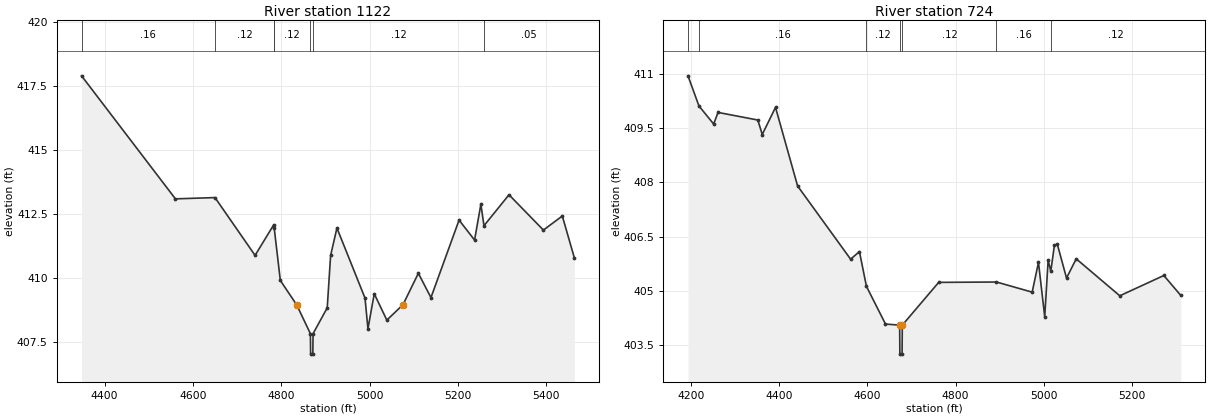
Type RM Length L Ch R = 1,1122,398,398,398
BEGIN DESCRIPTION:
UNT 144 in Running Cr Watershed 2.0
END DESCRIPTION:
XS GIS Cut Line= 3
      2878827.23      7034652.65      2878371.15      7034680.28
      2877942.72      7035181.11
#Sta/Elev= 30
  4347.8  417.91  4560.4  413.10  4650.0  413.15  4740.8  410.89  4783.2  412.09
  4784.0  411.98  4798.0  409.91  4834.9  408.96  4866.1  407.83  4866.6  407.03
  4871.6  407.03  4872.1  407.83  4904.2  408.84  4911.9  410.89  4926.2  411.96
  4989.8  409.22  4996.4  408.02  5010.7  409.39  5039.2  408.36  5075.7  408.96
  5110.6  410.19  5139.1  409.24  5202.8  412.27  5237.9  411.49  5252.2  412.89
  5259.2  412.05  5315.9  413.26  5393.8  411.88  5436.6  412.43  5463.8  410.80
#Mann=7,-1,0
  4347.8    0.16       0  4650.0    0.12       0  4783.2    0.16       0
  4784.0    0.12       0  4866.1    0.07       0  4872.1    0.12       0
  5259.2    0.05       0
Bank Sta=4834.9,5075.7
Exp/Cntr=0.3,0.1

Type RM Length L Ch R = 1,724,0,0,0
BEGIN DESCRIPTION:
UNT 144 in Running Cr Watershed 1.0
END DESCRIPTION:
XS GIS Cut Line= 3
      2878613.01      7034322.68      2878156.94      7034350.31
      2877727.59      7034852.21
#Sta/Elev= 30
  4193.3  410.94  4218.0  410.11  4251.4  409.61  4261.4  409.93  4351.6  409.72
  4361.6  409.32  4391.7  410.07  4441.8  407.90  4562.0  405.88  4582.0  406.09
  4597.9  405.13  4641.1  404.09  4673.2  404.06  4673.7  403.26  4678.7  403.26
  4679.2  404.06  4761.7  405.24  4892.8  405.25  4973.7  404.97  4988.0  405.79
  5002.2  404.29  5009.9  405.85  5016.0  405.55  5024.2  406.27  5030.8  406.29
  5051.6  405.36  5073.6  405.89  5172.4  404.87  5272.3  405.43  5310.7  404.88
#Mann=7,-1,0
  4193.3    0.12       0  4218.0    0.16       0  4597.9    0.12       0
  4673.2    0.07       0  4679.2    0.12       0  4892.8    0.16       0
  5016.0    0.12       0
Bank Sta=4673.2,4679.2
Exp/Cntr=0.3,0.1

Chan Stop Cuts=-1