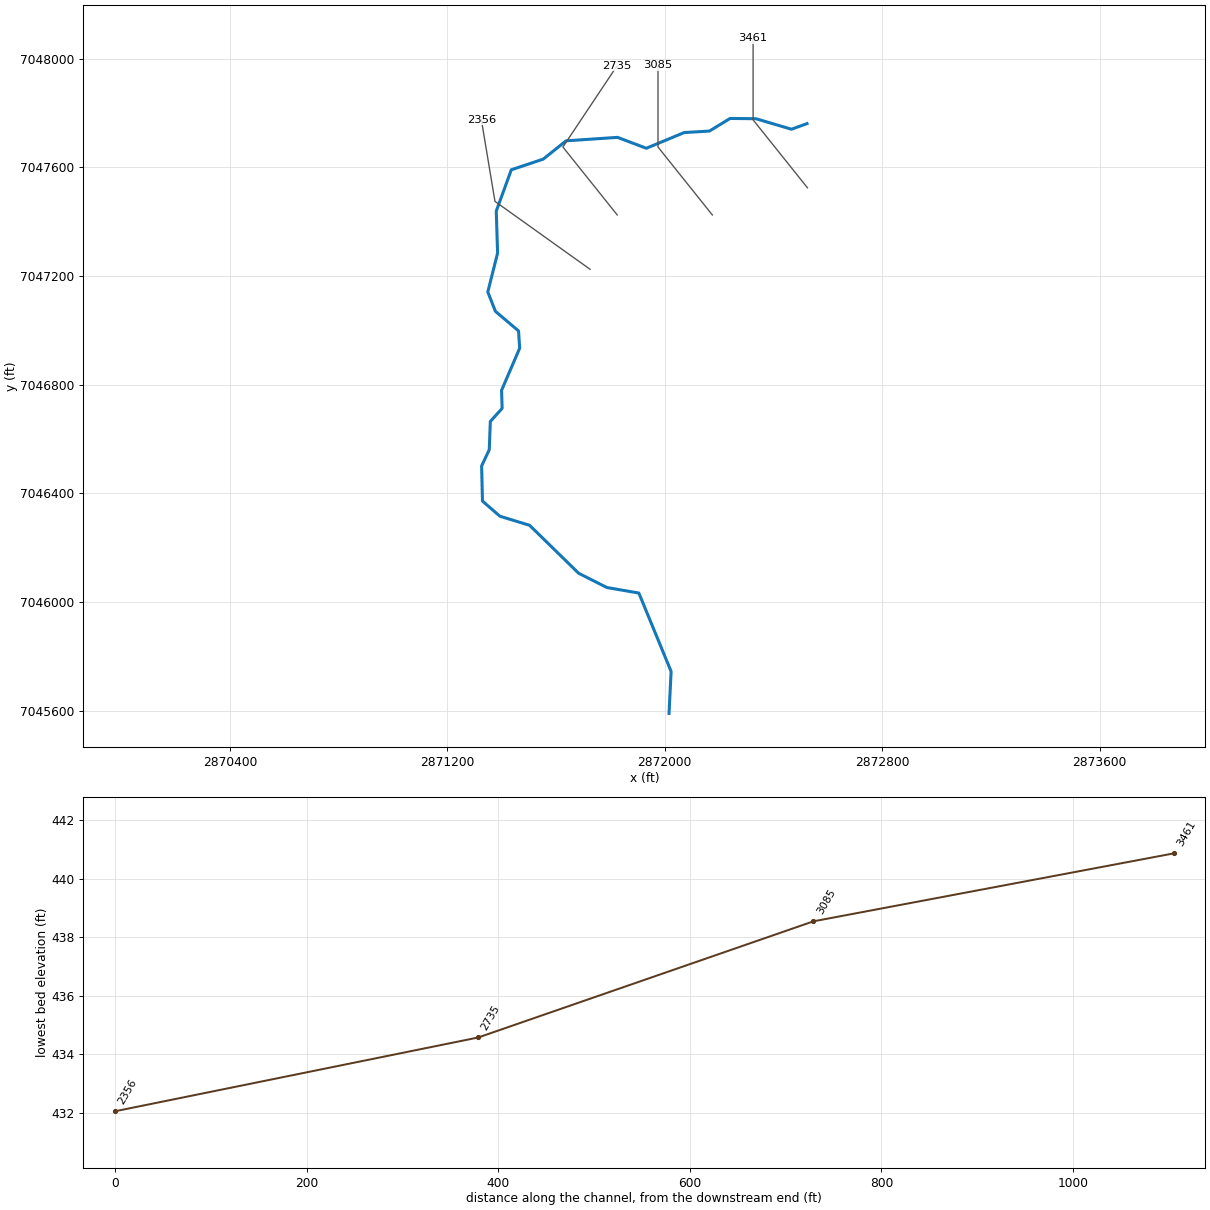
--- UNT 145 in Running Cr Watershed.prj (project) ---

Proj Title=UNT 145 in Running Cr Watershed Base Level Engineering
Current Plan=p01
Default Exp/Contr=0.3,0.1
English Units
Geom File=g01
Flow File=f01
Plan File=p01
BEGIN DESCRIPTION:
UNT 145 in Running Cr Watershed
END DESCRIPTION:

--- UNT 145 in Running Cr Watershed.p01 (plan) ---

Plan Title=Multiple Run
Short Identifier=Multiple
Geom File=g01
Flow File=f01
Subcritical Flow
K Sum by GR= 0
Std Step Tol= 0.01
Critical Tol= 0.01
Num of Std Step Trials= 20
Max Error Tol= 0.3
Flow Tol Ratio= 0.001
Split Flow NTrial= 30
Split Flow Tol= 0.02
Split Flow Ratio= 0.02
Log Output Level= 0
Friction Slope Method= 1
Unsteady Friction Slope Method= 2
Unsteady Bridges Friction Slope Method= 1
Parabolic Critical Depth
Global Vel Dist=  1 , 1 , 1
Global Log Level= 0
CheckData=True
Encroach Param= -1, 0, 0, 0
BEGIN DESCRIPTION:
Multiple Run
END DESCRIPTION:

--- UNT 145 in Running Cr Watershed.f01 (steady flow) ---

Flow Title=Multiple
Number of Profiles=7
Profile Names=10-year,25-year,50-year,1pct_min,100-year,1pct_plu,500-year
River Rch & RM= UNT 145 in Runni,Reach-1,3461
     180     222     253     144     288     575     373
Boundary for River Rch & Prof#=UNT 145 in Runni,Reach-1,1
Up Type=0
Dn Type=3
Dn Slope=0.005
Boundary for River Rch & Prof#=UNT 145 in Runni,Reach-1,2
Up Type=0
Dn Type=3
Dn Slope=0.005
Boundary for River Rch & Prof#=UNT 145 in Runni,Reach-1,3
Up Type=0
Dn Type=3
Dn Slope=0.005
Boundary for River Rch & Prof#=UNT 145 in Runni,Reach-1,4
Up Type=0
Dn Type=3
Dn Slope=0.005
Boundary for River Rch & Prof#=UNT 145 in Runni,Reach-1,5
Up Type=0
Dn Type=3
Dn Slope=0.005
Boundary for River Rch & Prof#=UNT 145 in Runni,Reach-1,6
Up Type=0
Dn Type=3
Dn Slope=0.005
Boundary for River Rch & Prof#=UNT 145 in Runni,Reach-1,7
Up Type=0
Dn Type=3
Dn Slope=0.005

--- UNT 145 in Running Cr Watershed.g01 (geometry) ---

Geom Title=Existing Conditions

River Reach=UNT 145 in Runni,Reach-1
Reach XY= 30
      2872523.48      7047761.15      2872466.07      7047740.53
      2872335.33      7047779.20      2872240.26      7047780.14
      2872164.33      7047733.75      2872071.38      7047728.22
      2871932.04      7047670.44      2871826.11      7047710.51
      2871636.79      7047697.77      2871552.57      7047630.40
      2871435.16      7047591.22      2871379.77      7047439.23
      2871384.67      7047284.79      2871348.64      7047141.73
      2871376.59      7047070.38      2871461.74      7046998.24
      2871465.91      7046934.60      2871399.33      7046779.49
      2871401.41      7046713.13      2871357.95      7046665.03
      2871354.00      7046560.97      2871325.89      7046501.21
      2871329.05      7046372.02      2871393.09      7046316.30
      2871502.32      7046282.94      2871682.96      7046106.37
      2871786.91      7046053.86      2871904.59      7046033.48
      2872023.27      7045744.91      2872015.59      7045590.71

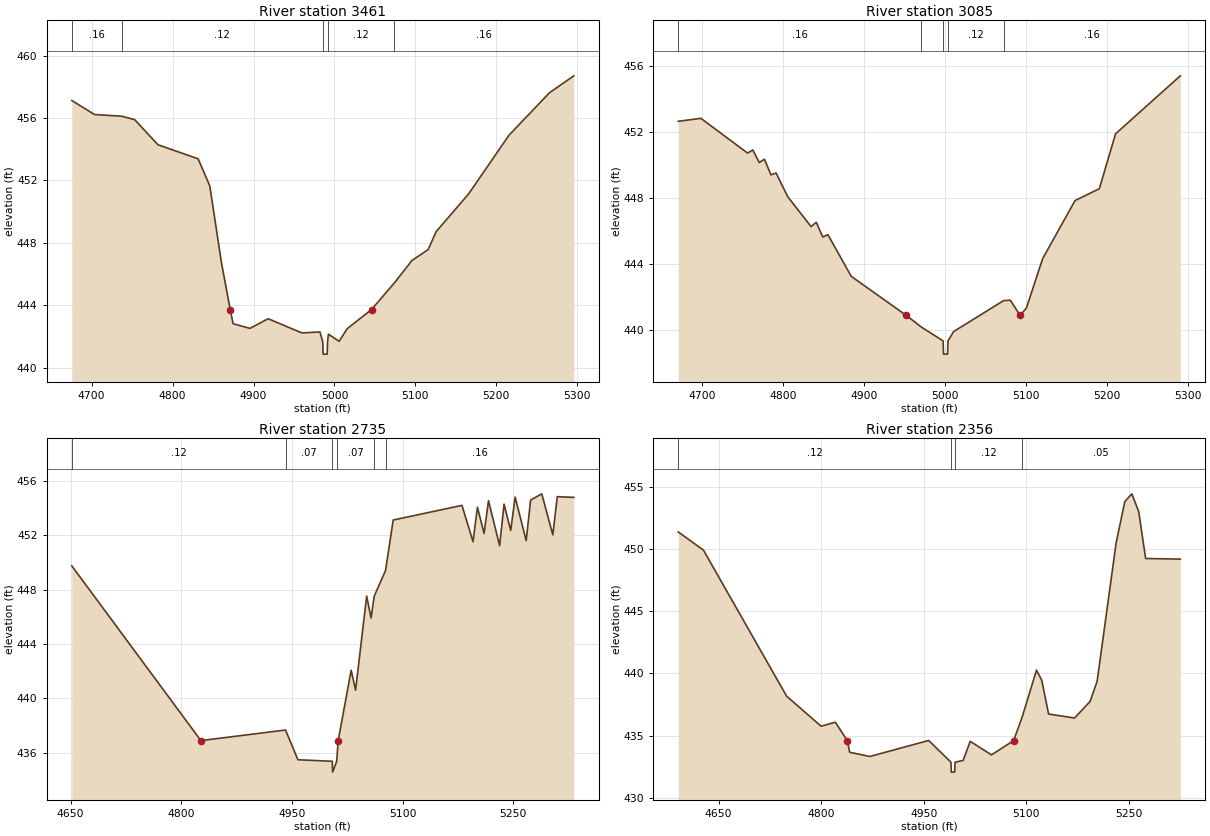
Type RM Length L Ch R = 1,3461,376,376,376
BEGIN DESCRIPTION:
UNT 145 in Running Cr Watershed 4.0
END DESCRIPTION:
XS GIS Cut Line= 3
      2872525.03      7047524.97      2872325.00      7047775.00
      2872325.00      7048075.00
#Sta/Elev= 30
  4675.5  457.12  4703.6  456.22  4737.2  456.11  4753.2  455.89  4782.0  454.28
  4831.6  453.38  4846.0  451.64  4860.4  446.72  4871.2  443.72  4874.8  442.81
  4895.6  442.51  4918.1  443.13  4959.7  442.22  4982.1  442.28  4985.5  441.66
  4986.0  440.86  4991.0  440.86  4991.5  441.66  4992.5  442.14  5005.7  441.68
  5015.7  442.49  5045.8  443.72  5073.6  445.40  5095.7  446.86  5115.7  447.56
  5125.7  448.72  5165.7  451.13  5215.7  454.90  5265.7  457.62  5295.7  458.70
#Mann=5,-1,0
  4675.5    0.16       0  4737.2    0.12       0  4985.5    0.07       0
  4991.5    0.12       0  5073.6    0.16       0
Bank Sta=4871.2,5045.8
Exp/Cntr=0.3,0.1

Type RM Length L Ch R = 1,3085,350,350,350
BEGIN DESCRIPTION:
UNT 145 in Running Cr Watershed 3.0
END DESCRIPTION:
XS GIS Cut Line= 3
      2872175.01      7047424.99      2871975.00      7047675.00
      2871975.00      7047975.03
#Sta/Elev= 30
  4670.4  452.67  4698.4  452.85  4756.1  450.74  4762.5  450.93  4770.5  450.17
  4776.9  450.37  4784.9  449.42  4791.3  449.53  4805.7  448.09  4834.5  446.28
  4840.9  446.54  4848.9  445.65  4855.3  445.79  4884.1  443.26  4952.1  440.89
  4970.5  440.19  4997.6  439.34  4998.1  438.54  5003.1  438.54  5003.6  439.34
  5010.6  439.91  5072.4  441.79  5080.6  441.81  5092.8  440.89  5100.6  441.35
  5120.6  444.34  5160.6  447.86  5190.6  448.58  5210.6  451.91  5290.6  455.43
#Mann=5,-1,0
  4670.4    0.16       0  4970.5    0.12       0  4997.6    0.07       0
  5003.6    0.12       0  5072.4    0.16       0
Bank Sta=4952.1,5092.8
Exp/Cntr=0.3,0.1

Type RM Length L Ch R = 1,2735,379,379,379
BEGIN DESCRIPTION:
UNT 145 in Running Cr Watershed 2.0
END DESCRIPTION:
XS GIS Cut Line= 3
      2871825.01      7047424.99      2871625.00      7047675.00
      2871824.99      7047974.98
#Sta/Elev= 30
  4651.6  449.76  4826.7  436.89  4941.4  437.67  4958.2  435.48  5004.8  435.37
  5005.3  434.57  5010.8  435.37  5012.8  436.89  5030.4  442.07  5036.4  440.60
  5051.4  447.53  5057.4  445.92  5061.7  447.53  5077.0  449.41  5087.4  453.13
  5180.6  454.21  5195.6  451.54  5201.6  454.07  5210.6  452.14  5216.6  454.55
  5231.7  451.24  5237.7  454.30  5246.7  452.36  5252.7  454.82  5267.7  451.62
  5273.7  454.60  5288.8  455.06  5303.8  452.04  5309.8  454.85  5332.3  454.80
#Mann=6,-1,0
  4651.6    0.12       0  4941.4    0.07       0  5004.8    0.07       0
  5010.8    0.07       0  5061.7     0.1       0  5077.0    0.16       0
Bank Sta=4826.7,5012.8
Exp/Cntr=0.3,0.1

Type RM Length L Ch R = 1,2356,0,0,0
BEGIN DESCRIPTION:
UNT 145 in Running Cr Watershed 1.0
END DESCRIPTION:
XS GIS Cut Line= 3
      2871724.97      7047225.02      2871375.00      7047475.00
      2871325.00      7047774.98
#Sta/Elev= 30
  4590.9  451.40  4627.7  449.94  4749.4  438.17  4799.8  435.75  4820.7  436.07
  4838.2  434.58  4841.6  433.65  4871.1  433.31  4957.1  434.60  4989.7  432.85
  4990.2  432.05  4995.2  432.05  4995.7  432.85  5007.5  432.99  5017.9  434.53
  5048.9  433.44  5081.3  434.58  5093.8  436.48  5114.8  440.26  5122.4  439.47
  5132.5  436.73  5170.5  436.41  5193.3  437.75  5203.5  439.38  5231.3  450.53
  5244.0  453.85  5254.2  454.47  5264.3  453.03  5274.4  449.26  5325.1  449.21
#Mann=4,-1,0
  4590.9    0.12       0  4989.7    0.07       0  4995.7    0.12       0
  5093.8    0.05       0
Bank Sta=4838.2,5081.3
Exp/Cntr=0.3,0.1

Chan Stop Cuts=-1