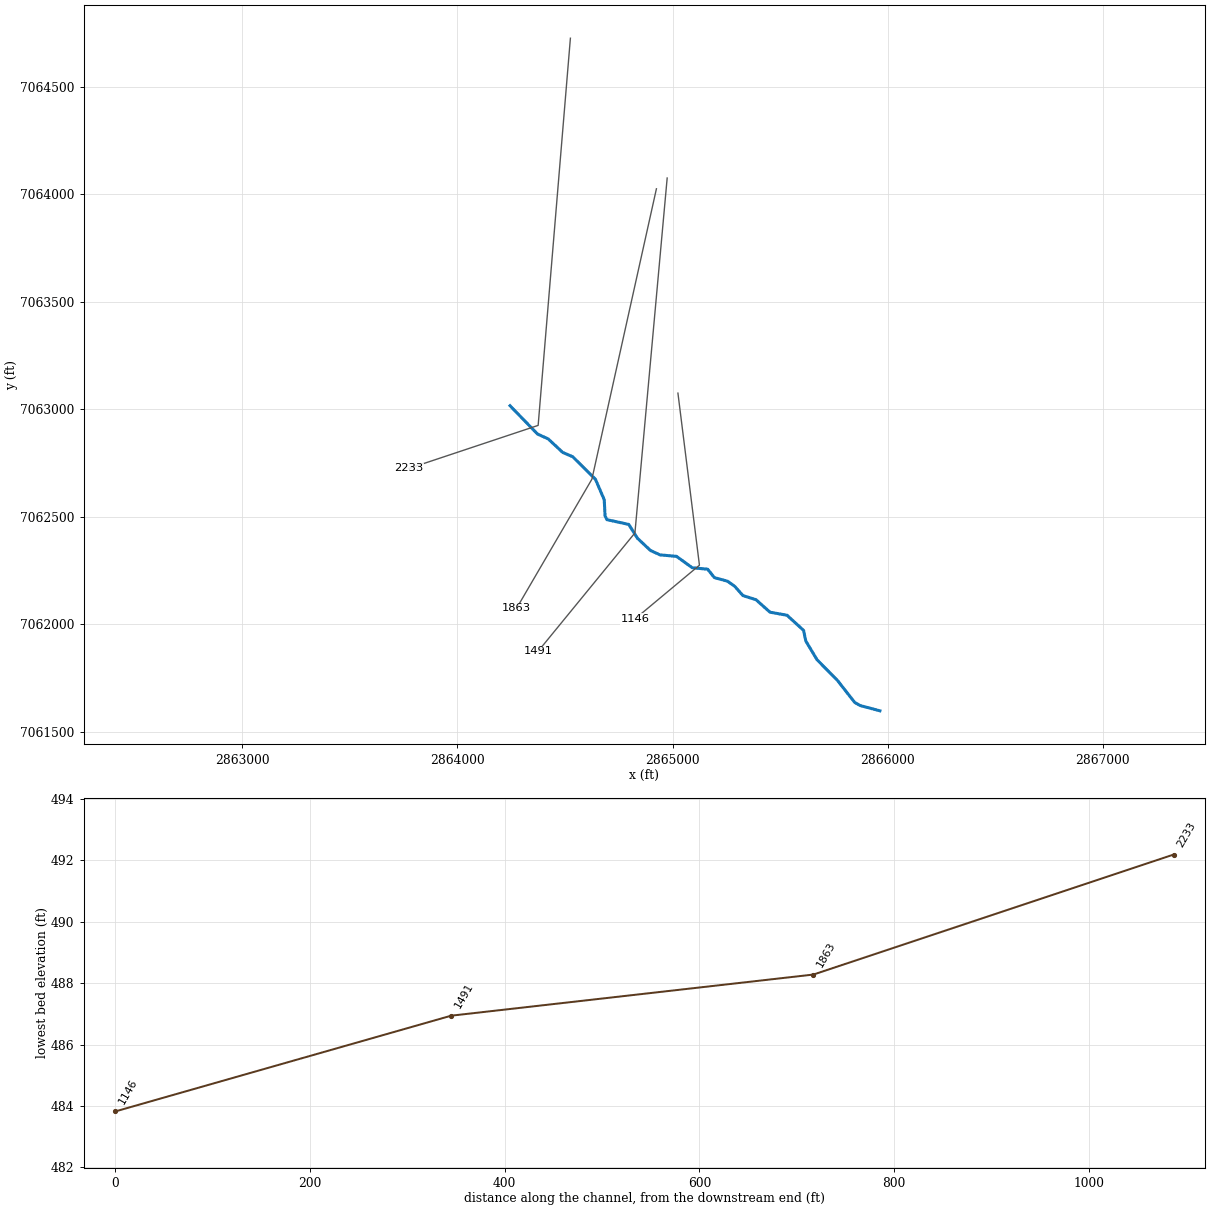
--- UNT 146 in Running Cr Watershed.prj (project) ---

Proj Title=UNT 146 in Running Cr Watershed Base Level Engineering
Current Plan=p01
Default Exp/Contr=0.3,0.1
English Units
Geom File=g01
Flow File=f01
Plan File=p01
BEGIN DESCRIPTION:
UNT 146 in Running Cr Watershed
END DESCRIPTION:

--- UNT 146 in Running Cr Watershed.p01 (plan) ---

Plan Title=Multiple Run
Short Identifier=Multiple
Geom File=g01
Flow File=f01
Subcritical Flow
K Sum by GR= 0
Std Step Tol= 0.01
Critical Tol= 0.01
Num of Std Step Trials= 20
Max Error Tol= 0.3
Flow Tol Ratio= 0.001
Split Flow NTrial= 30
Split Flow Tol= 0.02
Split Flow Ratio= 0.02
Log Output Level= 0
Friction Slope Method= 1
Unsteady Friction Slope Method= 2
Unsteady Bridges Friction Slope Method= 1
Parabolic Critical Depth
Global Vel Dist=  1 , 1 , 1
Global Log Level= 0
CheckData=True
Encroach Param= -1, 0, 0, 0
BEGIN DESCRIPTION:
Multiple Run
END DESCRIPTION:

--- UNT 146 in Running Cr Watershed.f01 (steady flow) ---

Flow Title=Multiple
Number of Profiles=7
Profile Names=10-year,25-year,50-year,1pct_min,100-year,1pct_plu,500-year
River Rch & RM= UNT 146 in Runni,Reach-1,2233
     300     380     440     254     508    1013     671
Boundary for River Rch & Prof#=UNT 146 in Runni,Reach-1,1
Up Type=0
Dn Type=3
Dn Slope=0.005
Boundary for River Rch & Prof#=UNT 146 in Runni,Reach-1,2
Up Type=0
Dn Type=3
Dn Slope=0.005
Boundary for River Rch & Prof#=UNT 146 in Runni,Reach-1,3
Up Type=0
Dn Type=3
Dn Slope=0.005
Boundary for River Rch & Prof#=UNT 146 in Runni,Reach-1,4
Up Type=0
Dn Type=3
Dn Slope=0.005
Boundary for River Rch & Prof#=UNT 146 in Runni,Reach-1,5
Up Type=0
Dn Type=3
Dn Slope=0.005
Boundary for River Rch & Prof#=UNT 146 in Runni,Reach-1,6
Up Type=0
Dn Type=3
Dn Slope=0.005
Boundary for River Rch & Prof#=UNT 146 in Runni,Reach-1,7
Up Type=0
Dn Type=3
Dn Slope=0.005

--- UNT 146 in Running Cr Watershed.g01 (geometry) ---

Geom Title=Existing Conditions

River Reach=UNT 146 in Runni,Reach-1
Reach XY= 30
      2864244.23      7063016.36      2864372.01      7062884.89
      2864421.87      7062862.13      2864489.31      7062799.29
      2864535.77      7062779.30      2864641.34      7062674.69
      2864682.38      7062579.33      2864686.08      7062504.90
      2864694.43      7062486.85      2864796.46      7062464.44
      2864836.60      7062400.44      2864896.85      7062343.84
      2864941.53      7062323.00      2865018.42      7062316.16
      2865091.64      7062263.13      2865163.25      7062256.44
      2865194.58      7062217.34      2865255.53      7062200.64
      2865288.81      7062177.05      2865327.41      7062133.63
      2865387.98      7062114.64      2865453.07      7062056.57
      2865532.10      7062042.44      2865609.27      7061971.88
      2865619.60      7061922.44      2865671.84      7061835.46
      2865766.17      7061740.12      2865847.31      7061636.66
      2865872.67      7061622.46      2865963.95      7061598.12

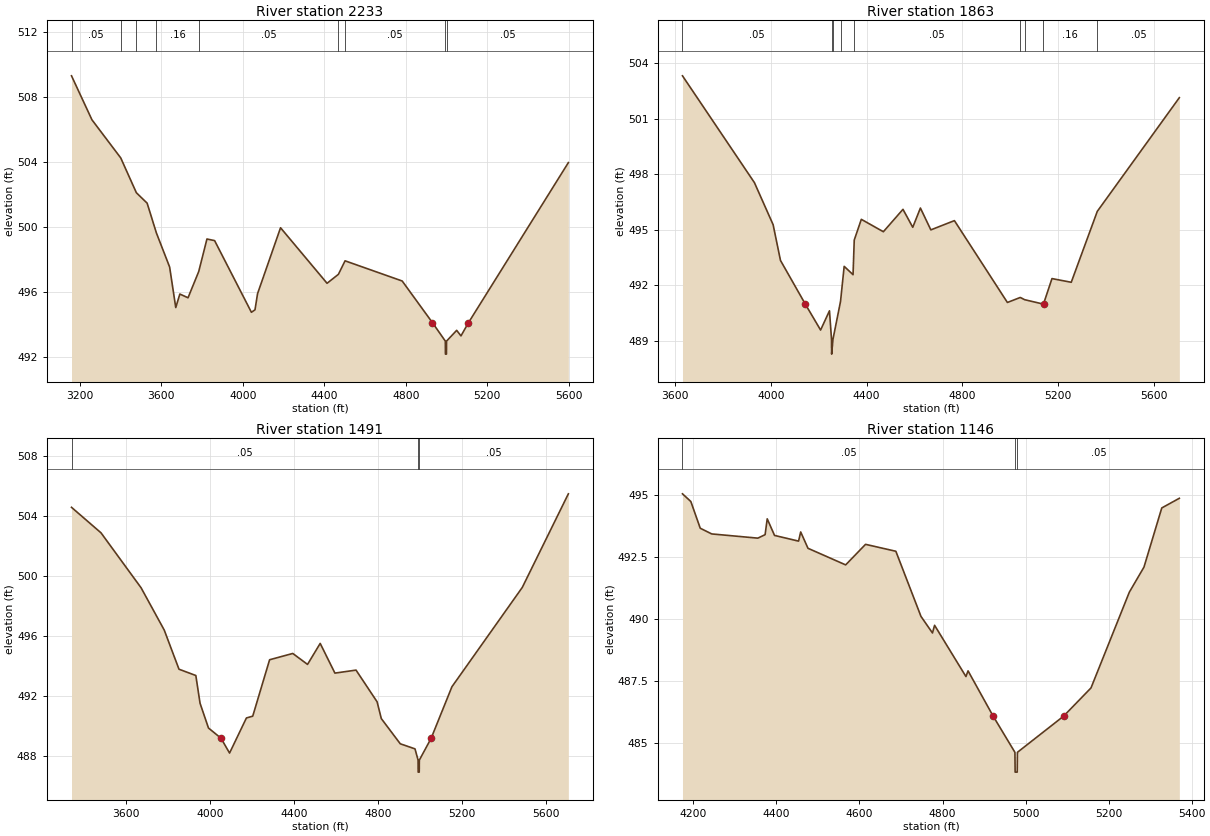
Type RM Length L Ch R = 1,2233,370,370,370
BEGIN DESCRIPTION:
UNT 146 in Running Cr Watershed 4.0
END DESCRIPTION:
XS GIS Cut Line= 3
      2864525.00      7064724.96      2864375.00      7062925.00
      2863774.95      7062724.98
#Sta/Elev= 30
  3159.6  509.28  3259.9  506.58  3401.2  504.24  3478.0  502.10  3530.8  501.46
  3576.3  499.63  3641.2  497.54  3671.3  495.05  3691.4  495.88  3731.5  495.65
  3784.0  497.26  3824.4  499.26  3862.0  499.16  4042.6  494.76  4060.2  494.91
  4072.7  495.90  4185.6  499.95  4413.9  496.54  4469.6  497.09  4502.3  497.92
  4782.7  496.68  4931.3  494.12  4994.4  492.99  4994.9  492.19  4999.9  492.19
  5000.4  492.99  5050.1  493.65  5071.2  493.31  5108.0  494.12  5598.3  503.95
#Mann=9,-1,0
  3159.6    0.05       0  3401.2    0.16       0  3478.0    0.12       0
  3576.3    0.16       0  3784.0    0.05       0  4469.6    0.16       0
  4502.3    0.05       0  4994.4    0.03       0  5000.4    0.05       0
Bank Sta=4931.3,5108
Exp/Cntr=0.3,0.1

Type RM Length L Ch R = 1,1863,372,372,372
BEGIN DESCRIPTION:
UNT 146 in Running Cr Watershed 3.0
END DESCRIPTION:
XS GIS Cut Line= 3
      2864925.00      7064025.00      2864625.00      7062675.00
      2864274.98      7062074.96
#Sta/Elev= 30
  3630.4  503.31  3931.3  497.54  4009.4  495.27  4040.2  493.34  4143.6  490.99
  4207.9  489.58  4245.0  490.62  4253.6  489.08  4254.1  488.28  4259.6  489.08
  4291.3  491.13  4306.5  493.02  4343.6  492.57  4348.6  494.44  4378.2  495.56
  4470.4  494.89  4552.4  496.10  4593.3  495.13  4625.3  496.17  4668.9  494.99
  4767.5  495.49  4989.0  491.07  5042.9  491.34  5061.1  491.22  5139.7  490.98
  5140.1  490.99  5175.4  492.36  5256.0  492.16  5364.9  495.99  5708.0  502.13
#Mann=9,-1,0
  3630.4    0.05       0  4253.6    0.03       0  4259.6    0.05       0
  4291.3    0.16       0  4348.6    0.05       0  5042.9     0.1       0
  5061.1    0.05       0  5139.7    0.16       0  5364.9    0.05       0
Bank Sta=4143.6,5140.1
Exp/Cntr=0.3,0.1

Type RM Length L Ch R = 1,1491,345,345,345
BEGIN DESCRIPTION:
UNT 146 in Running Cr Watershed 2.0
END DESCRIPTION:
XS GIS Cut Line= 3
      2864975.00      7064074.99      2864825.00      7062425.00
      2864375.02      7061875.03
#Sta/Elev= 30
  3339.8  504.59  3480.4  502.89  3671.2  499.23  3781.6  496.41  3851.9  493.80
  3932.2  493.38  3952.3  491.53  3992.5  489.88  4052.1  489.20  4092.9  488.21
  4173.2  490.55  4203.3  490.67  4283.7  494.43  4394.1  494.85  4464.4  494.12
  4524.7  495.52  4594.9  493.54  4695.4  493.74  4795.8  491.63  4815.9  490.51
  4906.2  488.83  4976.5  488.49  4991.1  487.74  4991.6  486.94  4996.6  486.94
  4997.1  487.74  5053.5  489.20  5152.4  492.63  5487.6  499.25  5707.2  505.49
#Mann=3,-1,0
  3339.8    0.05       0  4991.1    0.03       0  4997.1    0.05       0
Bank Sta=4052.1,5053.5
Exp/Cntr=0.3,0.1

Type RM Length L Ch R = 1,1146,0,0,0
BEGIN DESCRIPTION:
UNT 146 in Running Cr Watershed 1.0
END DESCRIPTION:
XS GIS Cut Line= 3
      2865025.00      7063074.98      2865125.00      7062275.00
      2864825.01      7062025.01
#Sta/Elev= 30
  4173.7  495.06  4193.8  494.75  4216.5  493.67  4244.2  493.44  4355.1  493.27
  4372.7  493.41  4377.8  494.05  4395.4  493.38  4453.3  493.15  4458.4  493.52
  4476.0  492.86  4566.7  492.19  4614.6  493.02  4687.6  492.74  4748.1  490.11
  4775.8  489.44  4780.9  489.75  4856.4  487.68  4861.5  487.91  4922.0  486.08
  4974.4  484.62  4974.9  483.82  4979.9  483.82  4980.4  484.62  5091.6  486.08
  5157.6  487.22  5250.0  491.09  5285.2  492.10  5328.1  494.49  5370.4  494.88
#Mann=3,-1,0
  4173.7    0.05       0  4974.4    0.03       0  4980.4    0.05       0
Bank Sta=4922,5091.6
Exp/Cntr=0.3,0.1

Chan Stop Cuts=-1