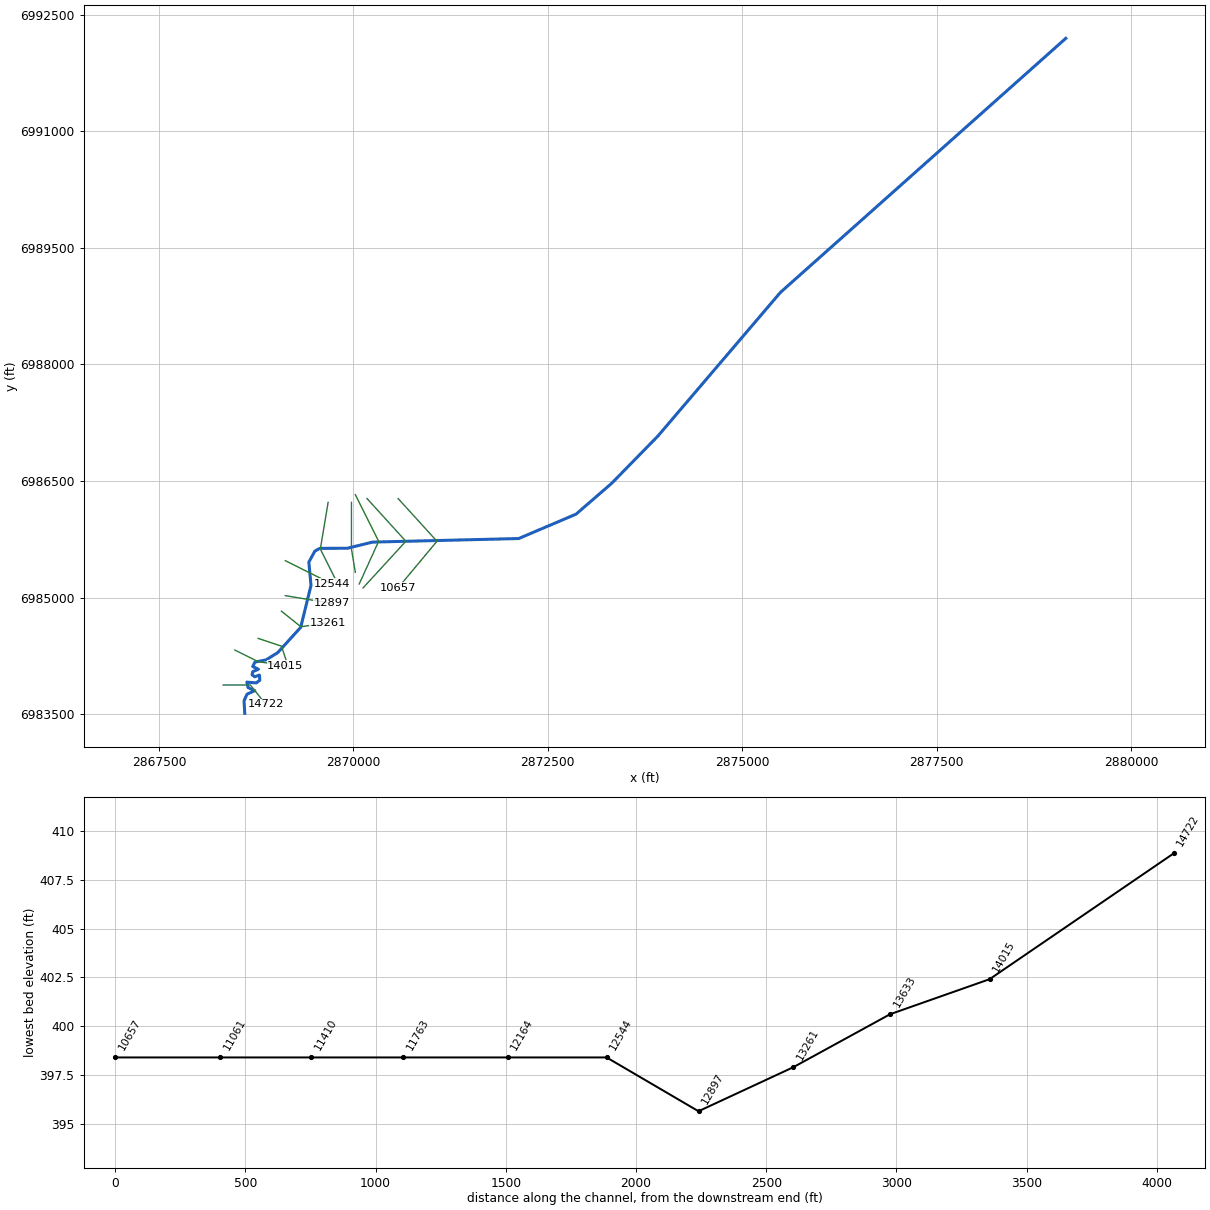
--- UNT 147 in Running Cr Watershed.prj (project) ---

Proj Title=UNT 147 in Running Cr Watershed Base Level Engineering
Current Plan=p01
Default Exp/Contr=0.3,0.1
English Units
Geom File=g01
Flow File=f01
Plan File=p01
BEGIN DESCRIPTION:
UNT 147 in Running Cr Watershed
END DESCRIPTION:

--- UNT 147 in Running Cr Watershed.p01 (plan) ---

Plan Title=Multiple Run
Short Identifier=Multiple
Geom File=g01
Flow File=f01
Subcritical Flow
K Sum by GR= 0
Std Step Tol= 0.01
Critical Tol= 0.01
Num of Std Step Trials= 20
Max Error Tol= 0.3
Flow Tol Ratio= 0.001
Split Flow NTrial= 30
Split Flow Tol= 0.02
Split Flow Ratio= 0.02
Log Output Level= 0
Friction Slope Method= 1
Unsteady Friction Slope Method= 2
Unsteady Bridges Friction Slope Method= 1
Parabolic Critical Depth
Global Vel Dist=  1 , 1 , 1
Global Log Level= 0
CheckData=True
Encroach Param= -1, 0, 0, 0
BEGIN DESCRIPTION:
Multiple Run
END DESCRIPTION:

--- UNT 147 in Running Cr Watershed.f01 (steady flow) ---

Flow Title=Multiple
Number of Profiles=7
Profile Names=10-year,25-year,50-year,1pct_min,100-year,1pct_plu,500-year
River Rch & RM= UNT 147 in Runni,Reach-1,14722
     472     626     749     446     891    1777    1260
Boundary for River Rch & Prof#=UNT 147 in Runni,Reach-1,1
Up Type=0
Dn Type=3
Dn Slope=0.005
Boundary for River Rch & Prof#=UNT 147 in Runni,Reach-1,2
Up Type=0
Dn Type=3
Dn Slope=0.005
Boundary for River Rch & Prof#=UNT 147 in Runni,Reach-1,3
Up Type=0
Dn Type=3
Dn Slope=0.005
Boundary for River Rch & Prof#=UNT 147 in Runni,Reach-1,4
Up Type=0
Dn Type=3
Dn Slope=0.005
Boundary for River Rch & Prof#=UNT 147 in Runni,Reach-1,5
Up Type=0
Dn Type=3
Dn Slope=0.005
Boundary for River Rch & Prof#=UNT 147 in Runni,Reach-1,6
Up Type=0
Dn Type=3
Dn Slope=0.005
Boundary for River Rch & Prof#=UNT 147 in Runni,Reach-1,7
Up Type=0
Dn Type=3
Dn Slope=0.005

--- UNT 147 in Running Cr Watershed.g01 (geometry) ---

Geom Title=Existing Conditions

River Reach=UNT 147 in Runni,Reach-1
Reach XY= 30
      2868602.61      6983509.86      2868593.67      6983672.31
      2868632.42      6983757.26      2868732.27      6983801.97
      2868644.34      6983842.21      2868629.44      6983912.26
      2868751.65      6983901.83      2868796.36      6983937.59
      2868791.89      6984003.17      2868732.27      6983980.81
      2868696.51      6984006.15      2868705.45      6984046.39
      2868778.48      6984077.69      2868705.45      6984113.46
      2868733.76      6984170.09      2868876.84      6984198.41
      2869025.88      6984290.81      2869322.46      6984617.20
      2869455.10      6985158.21      2869426.79      6985456.28
      2869504.29      6985597.87      2869568.37      6985633.64
      2869923.08      6985635.13      2870246.49      6985714.12
      2872126.54      6985759.96      2872864.04      6986074.08
      2873321.56      6986470.15      2873915.66      6987077.91
      2875493.10      6988928.49      2879162.89      6992197.59

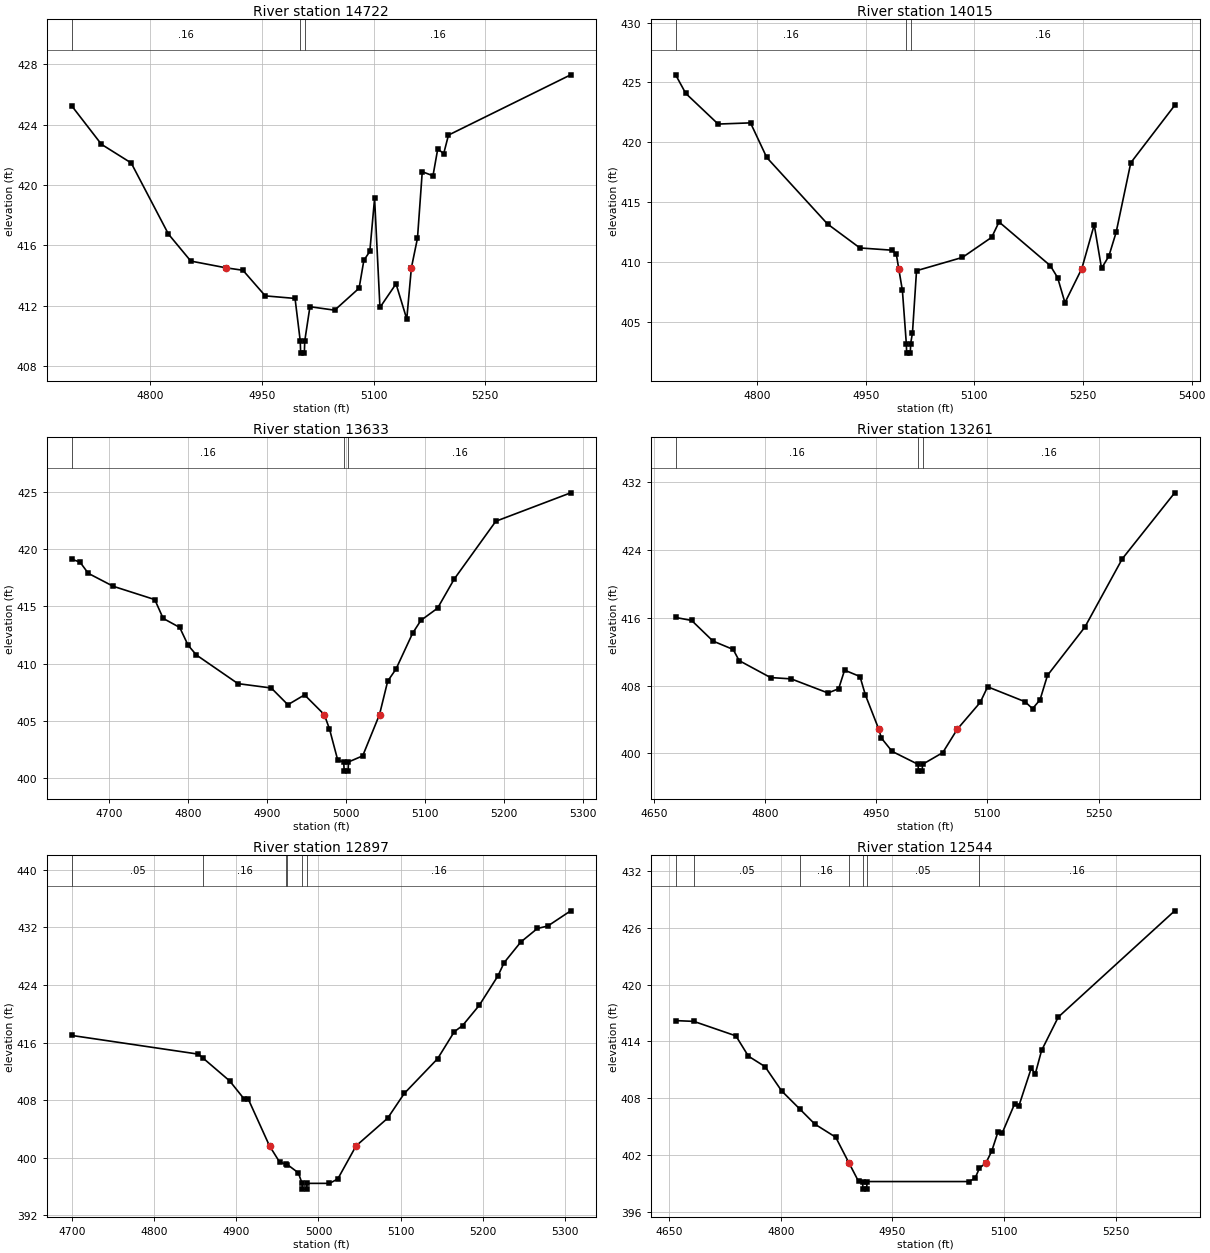
Type RM Length L Ch R = 1,14722,707,707,707
BEGIN DESCRIPTION:
UNT 147 in Running Cr Watershed 26.0
END DESCRIPTION:
XS GIS Cut Line= 3
      2868325.05      6983875.00      2868675.00      6983875.00
      2868874.99      6983625.01
#Sta/Elev= 30
  4694.6  425.26  4734.6  422.70  4774.6  421.46  4824.6  416.74  4854.6  414.95
  4902.0  414.50  4924.6  414.34  4954.6  412.64  4994.6  412.47  5001.6  409.64
  5002.1  408.84  5007.1  408.84  5007.6  409.64  5014.6  411.92  5047.8  411.69
  5080.6  413.15  5087.0  415.00  5095.0  415.59  5101.4  419.11  5108.6  411.87
  5130.2  413.44  5144.6  411.10  5150.8  414.50  5159.0  416.47  5165.4  420.88
  5179.8  420.61  5186.2  422.39  5194.2  422.08  5200.6  423.31  5364.7  427.31
#Mann=3,-1,0
  4694.6    0.16       0  5001.6    0.07       0  5007.6    0.16       0
Bank Sta=4902,5150.8
Exp/Cntr=0.3,0.1

Type RM Length L Ch R = 1,14015,382,382,382
BEGIN DESCRIPTION:
UNT 147 in Running Cr Watershed 25.0
END DESCRIPTION:
XS GIS Cut Line= 3
      2868474.98      6984325.01      2868775.00      6984175.00
      2869125.02      6984125.00
#Sta/Elev= 30
  4687.6  425.64  4701.6  424.09  4746.3  421.53  4791.0  421.63  4813.4  418.74
  4897.3  413.19  4942.0  411.19  4986.7  411.00  4992.3  410.66  4995.6  409.47
  5000.7  407.64  5006.1  403.21  5006.6  402.41  5011.6  402.41  5012.1  403.21
  5014.6  404.11  5020.2  409.29  5083.6  410.40  5124.0  412.08  5134.1  413.36
  5204.9  409.71  5215.0  408.71  5225.1  406.62  5248.4  409.47  5265.5  413.12
  5275.6  409.49  5285.7  410.50  5295.8  412.50  5316.0  418.30  5376.6  423.09
#Mann=3,-1,0
  4687.6    0.16       0  5006.1    0.07       0  5012.1    0.16       0
Bank Sta=4995.6,5248.4
Exp/Cntr=0.3,0.1

Type RM Length L Ch R = 1,13633,372,372,372
BEGIN DESCRIPTION:
UNT 147 in Running Cr Watershed 24.0
END DESCRIPTION:
XS GIS Cut Line= 3
      2868774.99      6984475.00      2869075.00      6984375.00
      2869175.01      6984074.97
#Sta/Elev= 30
  4652.3  419.10  4662.9  418.85  4673.4  417.87  4705.0  416.74  4757.7  415.58
  4768.3  413.94  4789.3  413.15  4799.9  411.60  4810.4  410.75  4863.1  408.25
  4905.3  407.87  4926.4  406.41  4947.5  407.27  4972.5  405.55  4979.1  404.30
  4989.6  401.57  4997.2  401.42  4997.7  400.62  5002.7  400.62  5003.2  401.42
  5021.2  401.95  5042.5  405.55  5052.9  408.47  5063.4  409.52  5084.5  412.65
  5095.0  413.77  5116.1  414.83  5137.2  417.37  5189.9  422.41  5284.8  424.89
#Mann=3,-1,0
  4652.3    0.16       0  4997.2    0.07       0  5003.2    0.16       0
Bank Sta=4972.5,5042.5
Exp/Cntr=0.3,0.1

Type RM Length L Ch R = 1,13261,364,364,364
BEGIN DESCRIPTION:
UNT 147 in Running Cr Watershed 23.0
END DESCRIPTION:
XS GIS Cut Line= 3
      2869074.98      6984825.01      2869325.00      6984625.00
      2869674.97      6984675.00
#Sta/Elev= 30
  4679.1  416.02  4700.7  415.67  4729.5  413.24  4756.8  412.25  4764.8  410.94
  4807.2  408.94  4835.2  408.78  4884.8  407.12  4899.2  407.62  4907.2  409.81
  4928.0  409.06  4935.2  406.90  4953.3  402.86  4956.9  401.80  4971.3  400.24
  5006.4  398.71  5006.9  397.91  5011.9  397.91  5012.4  398.71  5039.7  400.09
  5059.4  402.86  5090.2  406.00  5100.3  407.85  5150.8  406.09  5160.9  405.27
  5171.0  406.31  5181.1  409.20  5231.6  414.89  5282.1  422.94  5352.8  430.71
#Mann=3,-1,0
  4679.1    0.16       0  5006.4    0.07       0  5012.4    0.16       0
Bank Sta=4953.3,5059.4
Exp/Cntr=0.3,0.1

Type RM Length L Ch R = 1,12897,353,353,353
BEGIN DESCRIPTION:
UNT 147 in Running Cr Watershed 22.0
END DESCRIPTION:
XS GIS Cut Line= 3
      2869124.99      6985025.00      2869425.00      6984975.00
      2869725.02      6984925.00
#Sta/Elev= 30
  4699.1  417.00  4853.7  414.40  4859.7  413.81  4891.7  410.69  4909.5  408.16
  4914.5  408.14  4940.3  401.66  4952.6  399.42  4960.5  399.12  4962.0  399.07
  4975.4  397.93  4980.0  396.46  4980.5  395.66  4985.5  395.66  4986.0  396.46
  5013.4  396.46  5023.5  397.07  5045.8  401.66  5084.3  405.51  5104.6  408.95
  5145.2  413.77  5165.5  417.51  5175.6  418.37  5195.9  421.17  5218.7  425.26
  5226.3  427.11  5246.6  429.97  5266.8  431.85  5279.5  432.19  5307.4  434.30
#Mann=6,-1,0
  4699.1    0.05       0  4859.7    0.16       0  4960.5    0.05       0
  4962.0    0.16       0  4980.0    0.07       0  4986.0    0.16       0
Bank Sta=4940.3,5045.8
Exp/Cntr=0.3,0.1

Type RM Length L Ch R = 1,12544,380,380,380
BEGIN DESCRIPTION:
UNT 147 in Running Cr Watershed 21.0
END DESCRIPTION:
XS GIS Cut Line= 3
      2869125.02      6985474.99      2869425.00      6985325.00
      2869725.00      6985175.00
#Sta/Elev= 30
  4658.7  416.20  4683.1  416.12  4739.7  414.59  4756.5  412.45  4778.9  411.34
  4801.2  408.78  4825.3  406.89  4845.9  405.27  4873.9  403.89  4891.7  401.17
  4892.1  401.12  4904.6  399.22  4910.0  399.21  4910.5  398.41  4915.5  398.41
  4916.0  399.21  5052.8  399.21  5061.2  399.56  5067.1  400.63  5075.7  401.17
  5083.5  402.40  5091.9  404.43  5097.5  404.30  5114.3  407.40  5119.9  407.15
  5136.6  411.15  5142.2  410.60  5150.6  413.05  5173.0  416.57  5329.5  427.79
#Mann=7,-1,0
  4658.7    0.08       0  4683.1    0.05       0  4825.3    0.16       0
  4892.1    0.05       0  4910.0   0.033       0  4916.0    0.05       0
  5067.1    0.16       0
Bank Sta=4891.7,5075.7
Exp/Cntr=0.3,0.1

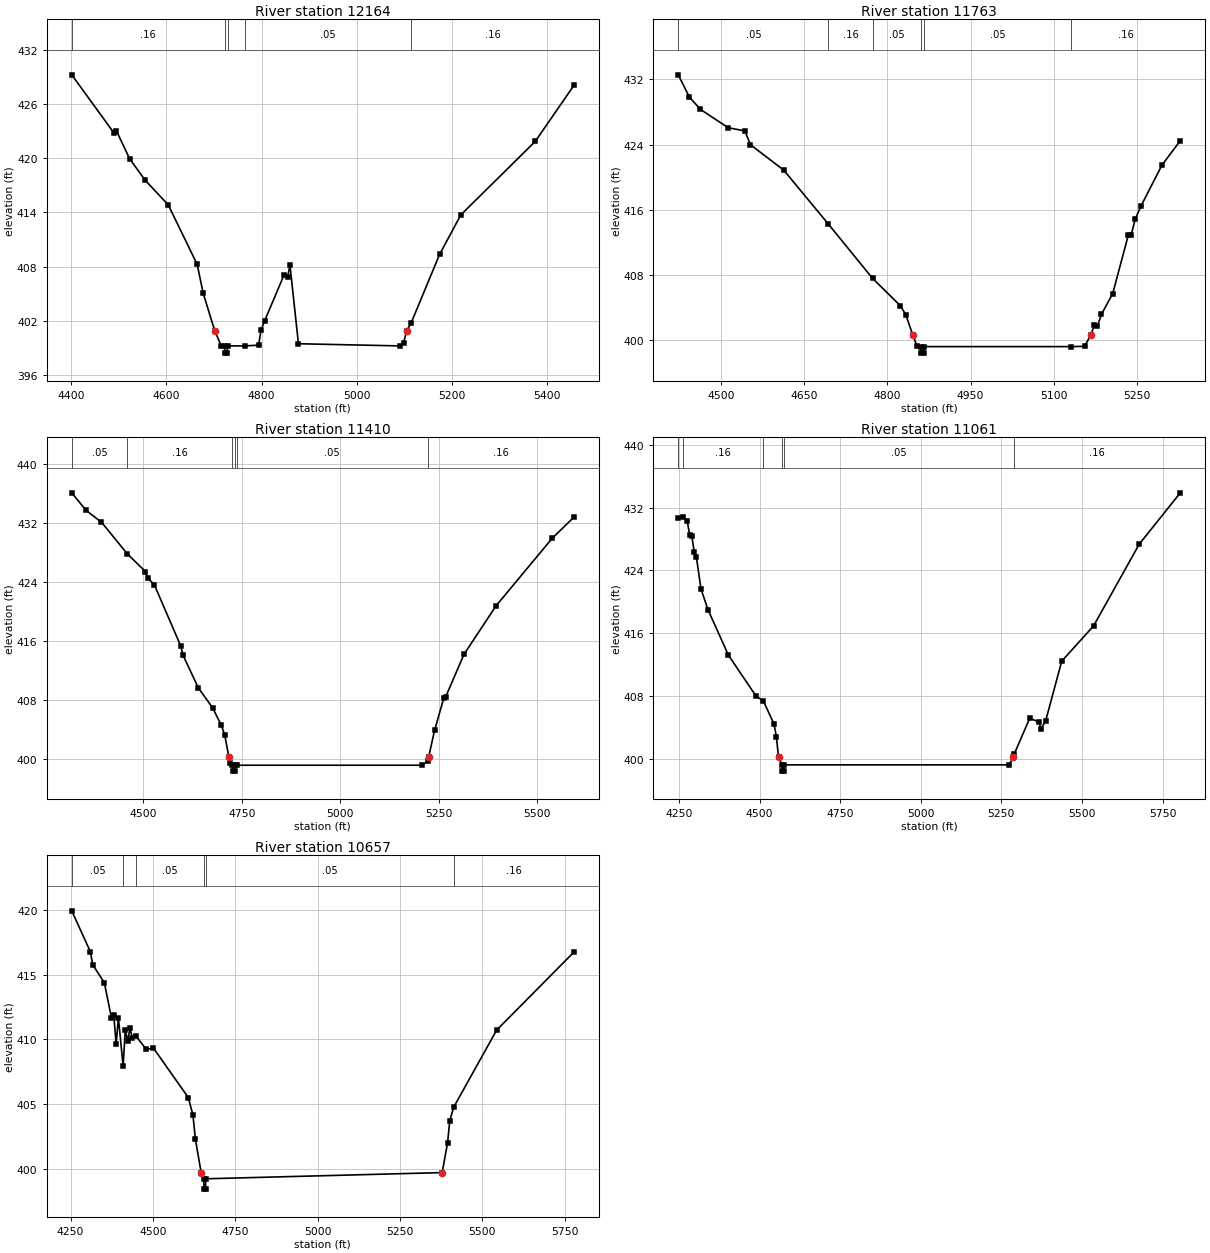
Type RM Length L Ch R = 1,12164,401,401,401
BEGIN DESCRIPTION:
UNT 147 in Running Cr Watershed 20.0
END DESCRIPTION:
XS GIS Cut Line= 3
      2869675.00      6986225.00      2869575.00      6985625.00
      2869775.00      6985224.99
#Sta/Elev= 30
  4400.9  429.23  4489.6  422.79  4494.7  423.04  4522.6  419.93  4555.5  417.54
  4603.7  414.83  4664.5  408.24  4677.2  405.04  4701.3  400.91  4715.2  399.21
  4722.3  399.21  4722.8  398.41  4727.8  398.41  4728.3  399.21  4764.4  399.21
  4793.7  399.29  4798.8  400.96  4806.4  401.99  4847.0  407.05  4854.6  406.82
  4859.6  408.18  4877.4  399.45  5090.2  399.21  5098.6  399.57  5105.0  400.91
  5114.0  401.71  5174.1  409.34  5218.8  413.72  5375.3  421.86  5456.4  428.05
#Mann=5,-1,0
  4400.9    0.16       0  4722.3   0.033       0  4728.3    0.16       0
  4764.4    0.05       0  5114.0    0.16       0
Bank Sta=4701.3,5105
Exp/Cntr=0.3,0.1

Type RM Length L Ch R = 1,11763,353,353,353
BEGIN DESCRIPTION:
UNT 147 in Running Cr Watershed 19.0
END DESCRIPTION:
XS GIS Cut Line= 3
      2869975.00      6986225.03      2869975.00      6985625.00
      2870025.01      6985324.96
#Sta/Elev= 30
  4423.5  432.55  4443.5  429.83  4463.5  428.31  4513.5  426.06  4543.5  425.67
  4553.5  423.98  4613.5  420.86  4694.1  414.22  4773.6  407.57  4823.5  404.23
  4833.5  403.09  4845.9  400.63  4853.5  399.28  4860.5  399.21  4861.0  398.41
  4866.0  398.41  4866.5  399.21  5130.1  399.21  5155.3  399.24  5166.3  400.63
  5173.1  401.84  5178.1  401.68  5185.7  403.17  5206.0  405.72  5233.9  412.86
  5239.0  412.87  5246.6  414.87  5256.7  416.43  5294.7  421.48  5327.7  424.47
#Mann=6,-1,0
  4423.5    0.05       0  4694.1    0.16       0  4773.6    0.05       0
  4860.5   0.033       0  4866.5    0.05       0  5130.1    0.16       0
Bank Sta=4845.9,5166.3
Exp/Cntr=0.3,0.1

Type RM Length L Ch R = 1,11410,349,349,349
BEGIN DESCRIPTION:
UNT 147 in Running Cr Watershed 18.0
END DESCRIPTION:
XS GIS Cut Line= 3
      2870025.02      6986324.97      2870325.00      6985725.00
      2870075.02      6985175.04
#Sta/Elev= 30
  4318.1  436.14  4354.4  433.76  4393.5  432.16  4458.7  427.90  4505.3  425.46
  4510.9  424.60  4527.7  423.68  4594.8  415.38  4600.4  414.15  4639.5  409.70
  4675.8  406.99  4698.2  404.60  4706.6  403.28  4716.8  400.38  4720.6  399.48
  4725.9  399.21  4726.4  398.41  4731.4  398.41  4731.9  399.21  4736.6  399.21
  5208.6  399.21  5222.2  399.82  5224.5  400.38  5239.3  403.92  5262.4  408.26
  5267.9  408.52  5314.0  414.24  5395.3  420.81  5538.1  429.98  5593.0  432.83
#Mann=6,-1,0
  4318.1    0.05       0  4458.7    0.16       0  4725.9   0.033       0
  4731.9    0.16       0  4736.6    0.05       0  5222.2    0.16       0
Bank Sta=4716.8,5224.5
Exp/Cntr=0.3,0.1

Type RM Length L Ch R = 1,11061,404,404,404
BEGIN DESCRIPTION:
UNT 147 in Running Cr Watershed 17.0
END DESCRIPTION:
XS GIS Cut Line= 3
      2870175.02      6986274.98      2870675.00      6985725.00
      2870125.01      6985125.01
#Sta/Elev= 30
  4247.9  430.73  4261.9  430.79  4275.9  430.28  4283.4  428.50  4290.1  428.37
  4297.5  426.36  4304.3  425.68  4318.5  421.63  4340.1  419.00  4403.6  413.19
  4488.8  408.00  4512.2  407.33  4545.2  404.39  4552.3  402.80  4559.0  400.18
  4570.2  399.21  4570.7  398.41  4575.7  398.41  4576.2  399.21  5274.5  399.21
  5286.8  400.19  5289.4  400.53  5338.0  405.15  5366.4  404.68  5373.2  403.82
  5387.4  404.81  5437.3  412.43  5536.0  416.92  5677.8  427.35  5805.1  433.89
#Mann=6,-1,0
  4247.9    0.05       0  4261.9    0.16       0  4512.2    0.05       0
  4570.2   0.033       0  4576.2    0.05       0  5289.4    0.16       0
Bank Sta=4559,5286.8
Exp/Cntr=0.3,0.1

Type RM Length L Ch R = 1,10657,0,0,0
BEGIN DESCRIPTION:
UNT 147 in Running Cr Watershed 16.0
END DESCRIPTION:
XS GIS Cut Line= 3
      2870575.01      6986274.99      2871075.00      6985725.00
      2870575.01      6985125.01
#Sta/Elev= 30
  4253.7  419.95  4310.1  416.79  4317.5  415.77  4352.7  414.38  4374.3  411.65
  4381.1  411.90  4388.5  409.64  4395.2  411.68  4409.6  407.93  4416.2  410.71
  4423.6  409.88  4430.4  410.88  4437.8  410.07  4448.1  410.27  4480.4  409.22
  4501.3  409.34  4607.4  405.50  4621.6  404.14  4629.1  402.26  4646.5  399.69
  4654.4  399.21  4654.9  398.41  4659.9  398.41  4660.4  399.21  5378.2  399.69
  5394.7  402.00  5401.2  403.70  5413.4  404.76  5543.7  410.72  5778.0  416.75
#Mann=6,-1,0
  4253.7    0.05       0  4409.6    0.16       0  4448.1    0.05       0
  4654.4   0.033       0  4660.4    0.05       0  5413.4    0.16       0
Bank Sta=4646.5,5378.2
Exp/Cntr=0.3,0.1

Chan Stop Cuts=-1