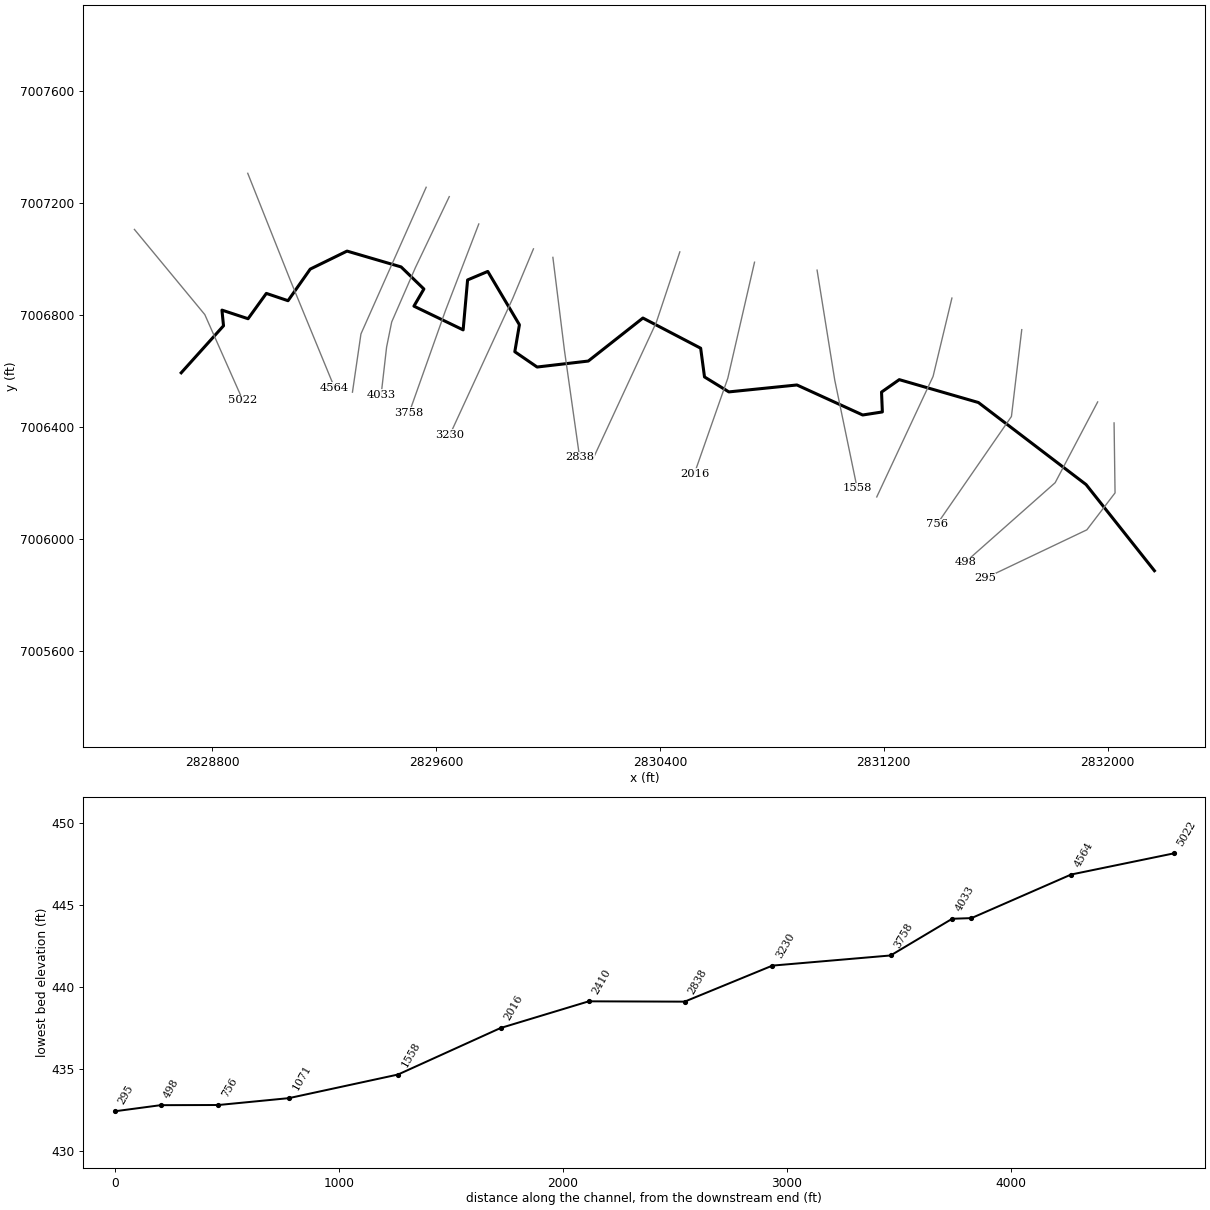
--- UNT 148 in Running Cr Watershed.prj (project) ---

Proj Title=UNT 148 in Running Cr Watershed Base Level Engineering
Current Plan=p01
Default Exp/Contr=0.3,0.1
English Units
Geom File=g01
Flow File=f01
Plan File=p01
BEGIN DESCRIPTION:
UNT 148 in Running Cr Watershed
END DESCRIPTION:

--- UNT 148 in Running Cr Watershed.p01 (plan) ---

Plan Title=Multiple Run
Short Identifier=Multiple
Geom File=g01
Flow File=f01
Subcritical Flow
K Sum by GR= 0
Std Step Tol= 0.01
Critical Tol= 0.01
Num of Std Step Trials= 20
Max Error Tol= 0.3
Flow Tol Ratio= 0.001
Split Flow NTrial= 30
Split Flow Tol= 0.02
Split Flow Ratio= 0.02
Log Output Level= 0
Friction Slope Method= 1
Unsteady Friction Slope Method= 2
Unsteady Bridges Friction Slope Method= 1
Parabolic Critical Depth
Global Vel Dist=  1 , 1 , 1
Global Log Level= 0
CheckData=True
Encroach Param= -1, 0, 0, 0
BEGIN DESCRIPTION:
Multiple Run
END DESCRIPTION:

--- UNT 148 in Running Cr Watershed.f01 (steady flow) ---

Flow Title=Multiple
Number of Profiles=7
Profile Names=10-year,25-year,50-year,1pct_min,100-year,1pct_plu,500-year
River Rch & RM= UNT 148 in Runni,Reach-1,5022
     470     617     734     434     866    1729    1207
Boundary for River Rch & Prof#=UNT 148 in Runni,Reach-1,1
Up Type=0
Dn Type=3
Dn Slope=0.005
Boundary for River Rch & Prof#=UNT 148 in Runni,Reach-1,2
Up Type=0
Dn Type=3
Dn Slope=0.005
Boundary for River Rch & Prof#=UNT 148 in Runni,Reach-1,3
Up Type=0
Dn Type=3
Dn Slope=0.005
Boundary for River Rch & Prof#=UNT 148 in Runni,Reach-1,4
Up Type=0
Dn Type=3
Dn Slope=0.005
Boundary for River Rch & Prof#=UNT 148 in Runni,Reach-1,5
Up Type=0
Dn Type=3
Dn Slope=0.005
Boundary for River Rch & Prof#=UNT 148 in Runni,Reach-1,6
Up Type=0
Dn Type=3
Dn Slope=0.005
Boundary for River Rch & Prof#=UNT 148 in Runni,Reach-1,7
Up Type=0
Dn Type=3
Dn Slope=0.005

--- UNT 148 in Running Cr Watershed.g01 (geometry) ---

Geom Title=Existing Conditions

River Reach=UNT 148 in Runni,Reach-1
Reach XY= 30
      2828689.86      7006592.43      2828841.03      7006760.40
      2828835.43      7006816.39      2828928.75      7006785.60
      2828994.07      7006876.11      2829071.53      7006849.99
      2829150.84      7006962.90      2829282.42      7007027.29
      2829475.59      7006970.71      2829557.00      7006891.81
      2829521.41      7006830.52      2829697.24      7006745.72
      2829713.15      7006924.20      2829785.30      7006954.60
      2829898.30      7006764.02      2829881.87      7006667.69
      2829961.53      7006613.00      2830144.41      7006634.37
      2830339.57      7006788.08      2830545.94      7006680.26
      2830559.68      7006577.61      2830646.61      7006524.15
      2830889.88      7006548.90      2831124.92      7006441.63
      2831195.17      7006452.54      2831192.21      7006523.50
      2831255.62      7006567.96      2831538.43      7006486.18
      2831923.11      7006193.02      2832167.25      7005885.20

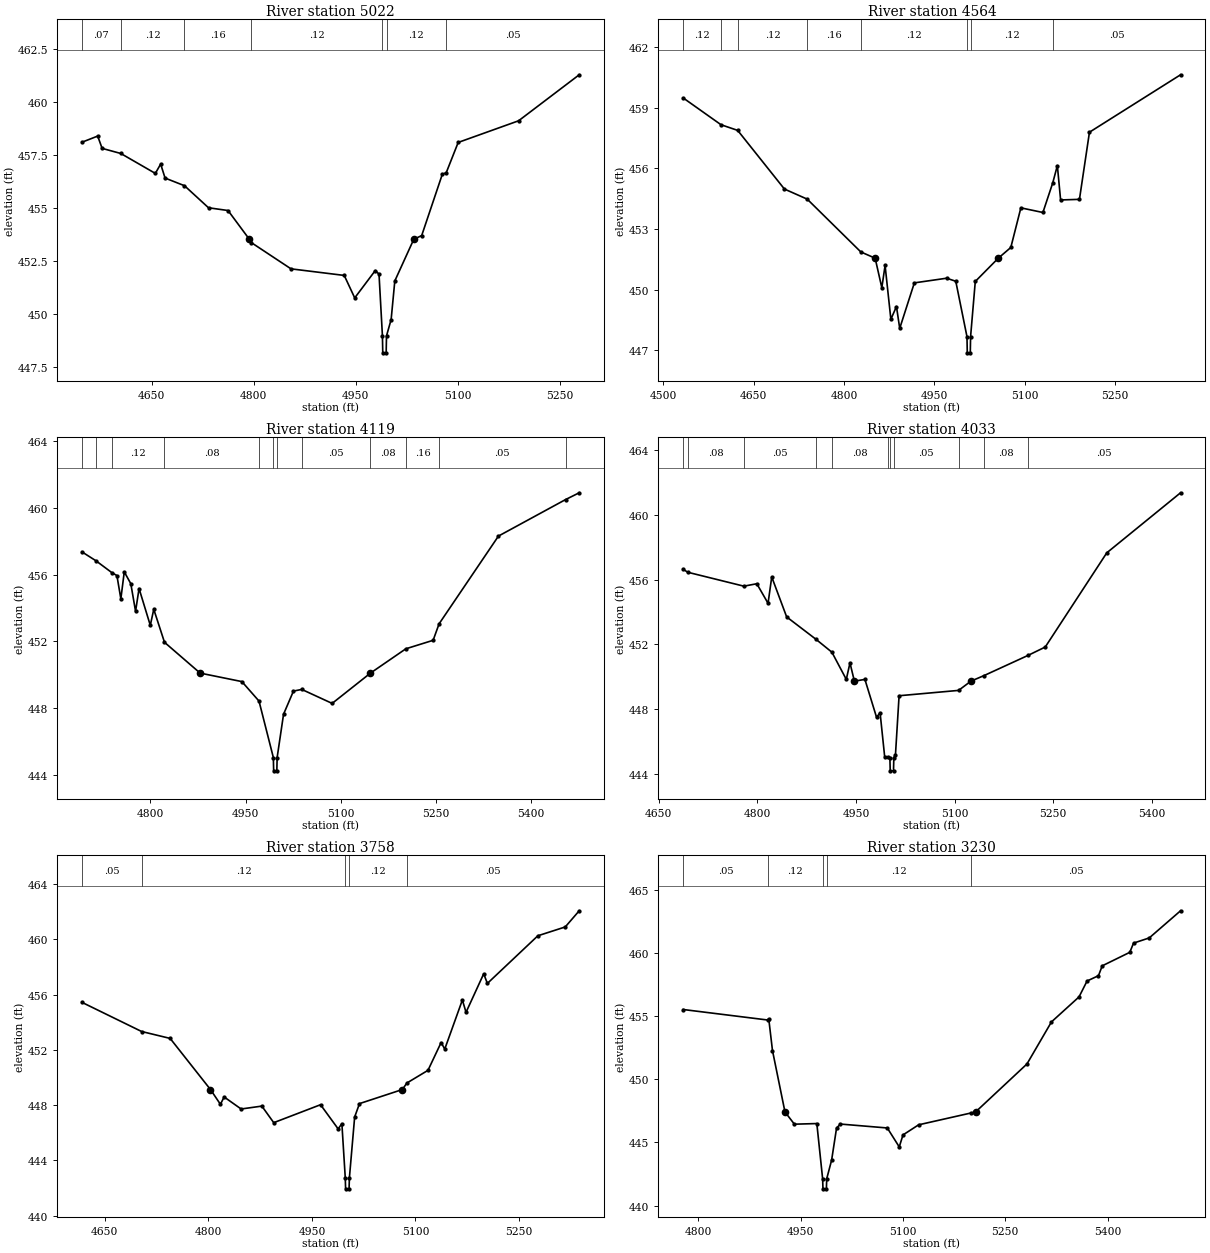
Type RM Length L Ch R = 1,5022,458,458,458
BEGIN DESCRIPTION:
UNT 148 in Running Cr Watershed 12.0
END DESCRIPTION:
XS GIS Cut Line= 3
      2828522.68      7007104.68      2828774.19      7006800.41
      2828910.34      7006493.52
#Sta/Elev= 30
  4547.7  458.10  4570.8  458.39  4577.3  457.81  4604.7  457.57  4655.5  456.63
  4663.3  457.07  4669.8  456.41  4698.3  456.05  4733.6  455.01  4762.3  454.88
  4793.7  453.52  4796.4  453.37  4854.8  452.13  4933.0  451.82  4948.4  450.76
  4978.6  452.05  4984.1  451.88  4989.1  448.97  4989.6  448.17  4994.6  448.17
  4995.1  448.97  5001.9  449.74  5007.3  451.56  5035.1  453.52  5046.8  453.70
  5077.1  456.59  5082.8  456.66  5100.4  458.09  5189.1  459.11  5278.2  461.28
#Mann=7,-1,0
  4547.7    0.07       0  4604.7    0.12       0  4698.3    0.16       0
  4796.4    0.12       0  4989.1    0.07       0  4995.1    0.12       0
  5082.8    0.05       0
Bank Sta=4793.7,5035.1
Exp/Cntr=0.3,0.1

Type RM Length L Ch R = 1,4564,445,445,445
BEGIN DESCRIPTION:
UNT 148 in Running Cr Watershed 11.0
END DESCRIPTION:
XS GIS Cut Line= 3
      2828927.62      7007305.23      2829079.97      7006922.39
      2829237.45      7006539.77
#Sta/Elev= 30
  4532.9  459.48  4595.5  458.16  4623.2  457.88  4700.8  454.98  4738.7  454.48
  4827.7  451.87  4851.5  451.56  4862.6  450.10  4868.0  451.20  4877.6  448.54
  4886.9  449.17  4892.3  448.09  4916.6  450.34  4970.2  450.57  4985.4  450.42
  5004.0  447.68  5004.5  446.88  5009.5  446.88  5010.0  447.68  5017.8  450.41
  5056.0  451.56  5076.8  452.09  5093.5  454.05  5130.1  453.82  5146.5  455.29
  5154.1  456.14  5159.5  454.44  5190.8  454.47  5207.4  457.79  5358.7  460.63
#Mann=8,-1,0
  4532.9    0.12       0  4595.5    0.16       0  4623.2    0.12       0
  4738.7    0.16       0  4827.7    0.12       0  5004.0    0.07       0
  5010.0    0.12       0  5146.5    0.05       0
Bank Sta=4851.5,5056
Exp/Cntr=0.3,0.1

Type RM Length L Ch R = 1,4119,86,86,86
BEGIN DESCRIPTION:
UNT 148 in Running Cr Watershed 10.0
END DESCRIPTION:
XS GIS Cut Line= 3
      2829565.17      7007255.34      2829332.14      7006731.42
      2829301.77      7006523.13
#Sta/Elev= 30
  4692.1  457.37  4714.0  456.84  4739.7  456.11  4747.2  455.95  4753.4  454.55
  4758.8  456.17  4769.1  455.46  4776.6  453.80  4782.1  455.17  4799.8  452.96
  4805.3  453.92  4822.2  451.94  4878.4  450.09  4944.2  449.58  4971.2  448.41
  4993.8  445.02  4994.3  444.22  4999.3  444.22  4999.8  445.02  5009.9  447.62
  5025.5  449.01  5038.6  449.11  5086.5  448.27  5146.9  450.09  5202.7  451.55
  5245.7  452.06  5255.1  453.05  5348.7  458.32  5454.4  460.51  5476.0  460.92
#Mann=12,-1,0
  4692.1    0.05       0  4714.0    0.08       0  4739.7    0.12       0
  4822.2    0.08       0  4971.2    0.12       0  4993.8    0.07       0
  4999.8    0.12       0  5038.6    0.05       0  5146.9    0.08       0
  5202.7    0.16       0  5255.1    0.05       0  5454.4    0.08       0
Bank Sta=4878.4,5146.9
Exp/Cntr=0.3,0.1

Type RM Length L Ch R = 1,4033,275,275,275
BEGIN DESCRIPTION:
Mapping XS fb0f1e51
END DESCRIPTION:
XS GIS Cut Line= 5
      2829647.67      7007221.85      2829526.59      7006967.97
      2829441.95      7006773.96      2829423.72      7006684.11
      2829404.19      7006513.54
#Sta/Elev= 30
  4687.5  456.63  4694.2  456.45  4779.6  455.59  4799.3  455.74  4816.4  454.53
  4822.0  456.16  4844.7  453.69  4889.2  452.31  4913.5  451.51  4935.4  449.83
  4941.0  450.85  4947.7  449.72  4963.7  449.83  4981.4  447.49  4986.8  447.77
  4993.8  445.04  4998.4  445.01  5001.7  444.98  5002.2  444.18  5007.2  444.18
  5007.7  444.98  5010.2  445.18  5015.7  448.82  5106.2  449.15  5124.9  449.72
  5144.6  450.06  5211.7  451.31  5238.0  451.83  5331.6  457.65  5443.8  461.36
#Mann=11,-1,0
  4687.5    0.05       0  4694.2    0.08       0  4779.6    0.05       0
  4889.2    0.12       0  4913.5    0.08       0  4998.4    0.05       0
  5001.7    0.04       0  5007.7    0.05       0  5106.2    0.12       0
  5144.6    0.08       0  5211.7    0.05       0
Bank Sta=4947.7,5124.9
Exp/Cntr=0.3,0.1

Type RM Length L Ch R = 1,3758,528,528,528
BEGIN DESCRIPTION:
UNT 148 in Running Cr Watershed 9.0
END DESCRIPTION:
XS GIS Cut Line= 3
      2829753.14      7007124.18      2829633.79      7006813.89
      2829504.10      7006448.58
#Sta/Elev= 30
  4617.0  455.44  4703.4  453.33  4744.7  452.83  4803.1  449.13  4817.5  448.06
  4822.9  448.59  4847.5  447.72  4877.5  447.93  4894.7  446.73  4962.5  448.03
  4988.0  446.28  4993.4  446.66  4998.3  442.74  4998.8  441.94  5003.8  441.94
  5004.3  442.74  5011.9  447.14  5018.9  448.11  5081.0  449.13  5087.5  449.60
  5118.1  450.52  5137.1  452.53  5142.4  452.06  5167.9  455.61  5173.2  454.72
  5198.8  457.51  5204.1  456.81  5277.2  460.26  5316.9  460.90  5337.1  462.07
#Mann=5,-1,0
  4617.0    0.05       0  4703.4    0.12       0  4998.3    0.07       0
  5004.3    0.12       0  5087.5    0.05       0
Bank Sta=4803.1,5081
Exp/Cntr=0.3,0.1

Type RM Length L Ch R = 1,3230,392,392,392
BEGIN DESCRIPTION:
UNT 148 in Running Cr Watershed 8.0
END DESCRIPTION:
XS GIS Cut Line= 3
      2829948.46      7007035.24      2829875.00      7006859.46
      2829649.71      7006370.58
#Sta/Elev= 30
  4778.2  455.52  4901.8  454.69  4903.5  454.75  4908.9  452.27  4927.2  447.41
  4941.0  446.44  4973.9  446.49  4982.4  442.12  4982.9  441.32  4987.9  441.32
  4988.4  442.12  4995.6  443.60  5002.8  446.13  5008.4  446.45  5077.2  446.14
  5094.7  444.64  5100.2  445.59  5123.1  446.39  5200.1  447.33  5206.6  447.41
  5281.9  451.21  5317.8  454.54  5358.2  456.52  5370.0  457.78  5386.7  458.20
  5392.2  458.98  5432.6  460.05  5438.1  460.78  5461.1  461.19  5507.0  463.34
#Mann=5,-1,0
  4778.2    0.05       0  4901.8    0.12       0  4982.4    0.07       0
  4988.4    0.12       0  5200.1    0.05       0
Bank Sta=4927.2,5206.6
Exp/Cntr=0.3,0.1

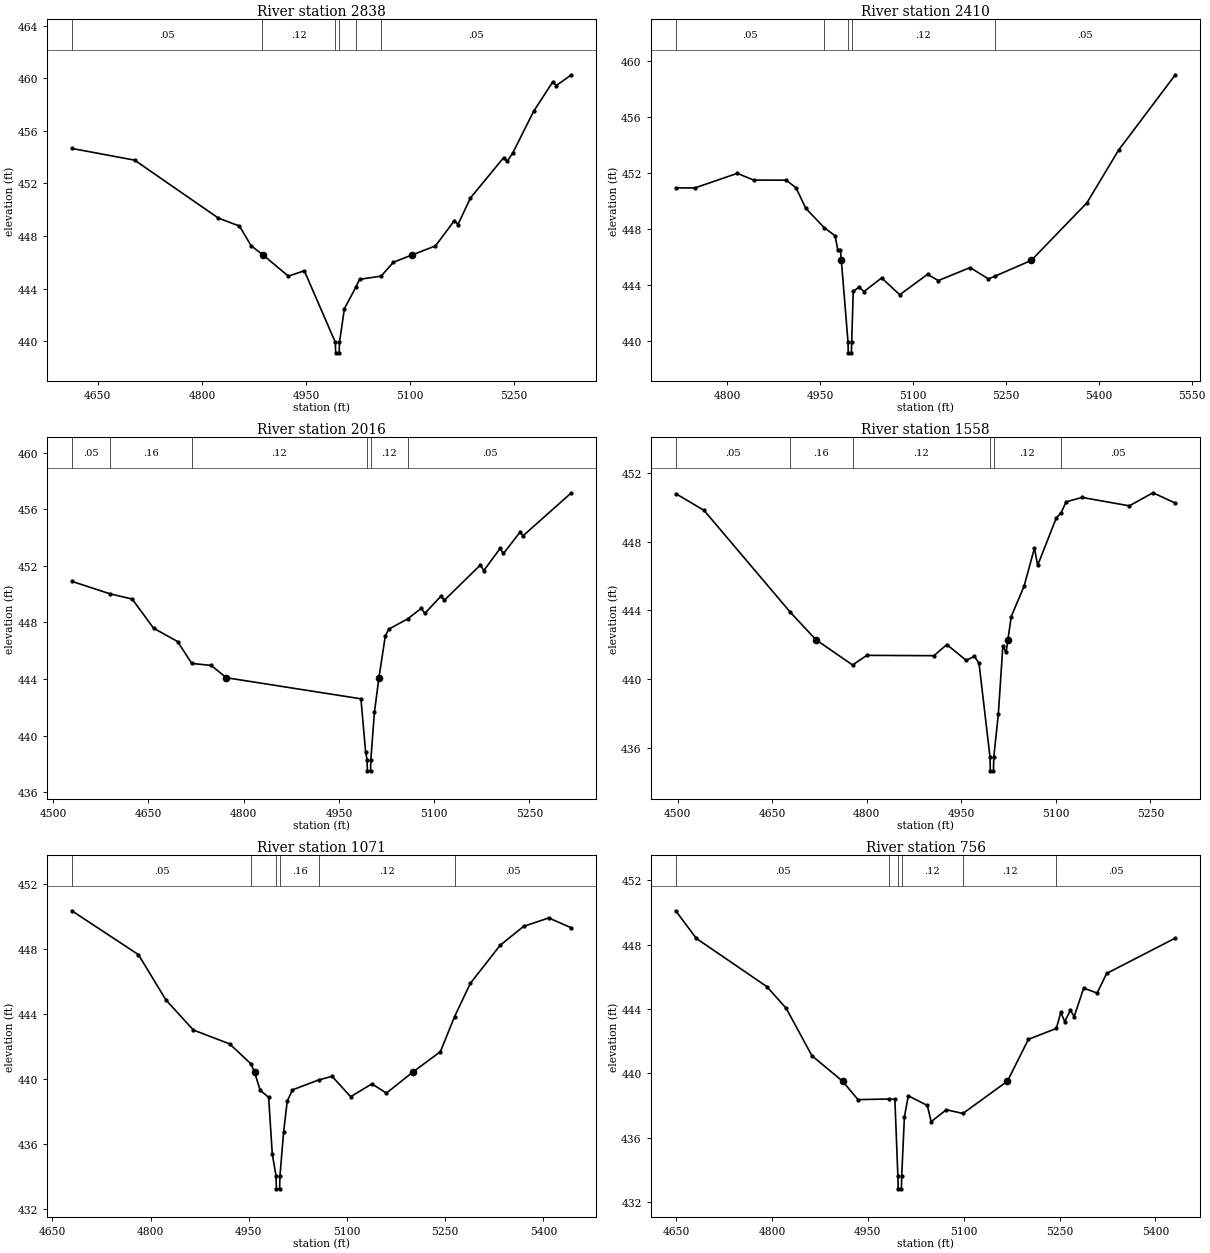
Type RM Length L Ch R = 1,2838,428,428,428
BEGIN DESCRIPTION:
UNT 148 in Running Cr Watershed 7.0
END DESCRIPTION:
XS GIS Cut Line= 3
      2830017.91      7007004.83      2830059.28      7006672.15
      2830113.39      7006290.91
#Sta/Elev= 30
  4612.5  454.66  4703.0  453.77  4823.9  449.36  4854.2  448.76  4870.9  447.27
  4886.7  446.62  4888.5  446.55  4924.7  444.95  4947.7  445.36  4992.4  439.92
  4992.9  439.12  4997.9  439.12  4998.4  439.92  5005.5  442.48  5022.0  444.11
  5027.4  444.71  5058.4  444.95  5076.2  446.01  5102.5  446.55  5136.8  447.25
  5164.2  449.18  5169.2  448.87  5187.3  450.90  5235.1  453.96  5240.2  453.68
  5247.9  454.28  5278.2  457.47  5306.0  459.73  5311.1  459.44  5332.8  460.26
#Mann=6,-1,0
  4612.5    0.05       0  4886.7    0.12       0  4992.4    0.07       0
  4998.4    0.12       0  5022.0    0.16       0  5058.4    0.05       0
Bank Sta=4888.5,5102.5
Exp/Cntr=0.3,0.1

Type RM Length L Ch R = 1,2410,394,394,394
BEGIN DESCRIPTION:
UNT 148 in Running Cr Watershed 6.0
END DESCRIPTION:
XS GIS Cut Line= 3
      2830471.48      7007024.43      2830387.28      7006772.15
      2830159.50      7006281.18
#Sta/Elev= 30
  4716.4  450.92  4747.4  450.92  4815.9  451.96  4842.2  451.48  4895.0  451.47
  4910.7  450.93  4926.6  449.46  4956.1  448.09  4973.9  447.50  4978.2  446.50
  4982.4  446.50  4984.0  445.74  4994.7  439.94  4995.2  439.14  5000.2  439.14
  5000.7  439.94  5003.2  443.53  5012.3  443.83  5020.6  443.52  5049.0  444.49
  5078.4  443.29  5123.3  444.75  5140.6  444.30  5192.0  445.23  5221.7  444.42
  5231.9  444.61  5290.8  445.74  5380.7  449.85  5432.0  453.62  5523.6  459.00
#Mann=5,-1,0
  4716.4    0.05       0  4956.1    0.12       0  4994.7    0.07       0
  5000.7    0.12       0  5231.9    0.05       0
Bank Sta=4984,5290.8
Exp/Cntr=0.3,0.1

Type RM Length L Ch R = 1,2016,458,458,458
BEGIN DESCRIPTION:
UNT 148 in Running Cr Watershed 5.0
END DESCRIPTION:
XS GIS Cut Line= 3
      2830738.40      7006987.54      2830642.91      7006573.00
      2830523.55      7006232.30
#Sta/Elev= 30
  4529.6  450.90  4589.7  450.02  4624.6  449.65  4658.3  447.59  4696.0  446.65
  4718.4  445.10  4749.0  444.96  4772.8  444.09  4984.7  442.60  4992.0  438.87
  4994.3  438.31  4994.8  437.51  4999.8  437.51  5000.3  438.31  5005.9  441.64
  5013.0  444.09  5023.0  447.02  5028.3  447.52  5058.0  448.24  5079.8  449.00
  5085.1  448.63  5110.8  449.86  5116.1  449.57  5172.8  452.06  5178.1  451.66
  5203.8  453.23  5209.1  452.87  5234.8  454.36  5240.1  454.13  5316.0  457.16
#Mann=6,-1,0
  4529.6    0.05       0  4589.7    0.16       0  4718.4    0.12       0
  4994.3    0.07       0  5000.3    0.12       0  5058.0    0.05       0
Bank Sta=4772.8,5013
Exp/Cntr=0.3,0.1

Type RM Length L Ch R = 1,1558,487,487,487
BEGIN DESCRIPTION:
UNT 148 in Running Cr Watershed 4.0
END DESCRIPTION:
XS GIS Cut Line= 3
      2830961.92      7006959.24      2831025.00      7006566.49
      2831105.15      7006180.20
#Sta/Elev= 30
  4497.1  450.80  4541.9  449.83  4678.8  443.90  4719.4  442.30  4777.5  440.83
  4800.2  441.39  4906.6  441.37  4927.0  442.02  4957.7  441.10  4970.9  441.33
  4978.1  440.93  4995.5  435.47  4996.0  434.67  5001.0  434.67  5001.5  435.47
  5008.7  437.96  5015.9  441.94  5021.0  441.56  5023.9  442.30  5029.2  443.65
  5049.6  445.42  5066.0  447.63  5071.1  446.63  5100.7  449.39  5108.2  449.68
  5116.2  450.32  5141.5  450.58  5216.5  450.09  5253.9  450.85  5289.4  450.25
#Mann=6,-1,0
  4497.1    0.05       0  4678.8    0.16       0  4777.5    0.12       0
  4995.5    0.07       0  5001.5    0.12       0  5108.2    0.05       0
Bank Sta=4719.4,5023.9
Exp/Cntr=0.3,0.1

Type RM Length L Ch R = 1,1071,315,315,315
BEGIN DESCRIPTION:
UNT 148 in Running Cr Watershed 3.0
END DESCRIPTION:
XS GIS Cut Line= 3
      2831443.69      7006859.47      2831376.41      7006579.51
      2831175.15      7006148.84
#Sta/Elev= 30
  4679.6  450.34  4781.4  447.64  4823.4  444.85  4865.4  443.00  4920.7  442.15
  4953.3  440.92  4958.8  440.41  4967.3  439.30  4980.3  438.86  4985.9  435.36
  4991.6  434.03  4992.1  433.23  4997.1  433.23  4997.6  434.03  5003.2  436.74
  5008.7  438.63  5016.7  439.32  5057.3  439.94  5077.3  440.15  5105.6  438.90
  5138.1  439.69  5160.2  439.12  5200.5  440.41  5242.7  441.67  5264.3  443.82
  5288.4  445.87  5334.1  448.22  5369.9  449.38  5408.2  449.90  5442.9  449.29
#Mann=6,-1,0
  4679.6    0.05       0  4953.3    0.16       0  4991.6    0.07       0
  4997.6    0.16       0  5057.3    0.12       0  5264.3    0.05       0
Bank Sta=4958.8,5200.5
Exp/Cntr=0.3,0.1

Type RM Length L Ch R = 1,756,258,258,258
BEGIN DESCRIPTION:
Mapping XS 0f416845
END DESCRIPTION:
XS GIS Cut Line= 3
      2831693.25      7006746.57      2831656.36      7006436.28
      2831389.73      7006050.42
#Sta/Elev= 30
  4649.5  450.11  4681.7  448.39  4792.1  445.39  4822.3  444.04  4862.6  441.09
  4910.4  439.51  4934.6  438.36  4983.2  438.40  4992.3  438.38  4997.0  433.61
  4997.5  432.81  5002.5  432.81  5003.0  433.61  5007.2  437.28  5013.3  438.60
  5043.0  438.00  5049.1  436.99  5072.8  437.73  5098.8  437.50  5168.4  439.51
  5201.2  442.11  5244.9  442.79  5251.9  443.79  5258.0  443.21  5266.8  443.92
  5272.8  443.53  5287.7  445.30  5308.7  444.99  5323.5  446.21  5431.0  448.41
#Mann=6,-1,0
  4649.5    0.05       0  4983.2    0.12       0  4997.0    0.07       0
  5003.0    0.12       0  5098.8    0.12       0  5244.9    0.05       0
Bank Sta=4910.4,5168.4
Exp/Cntr=0.3,0.1

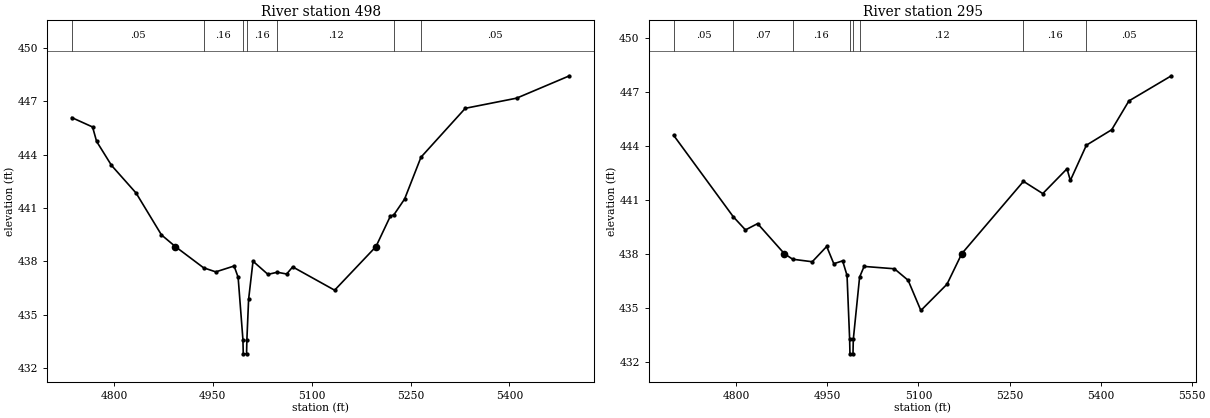
Type RM Length L Ch R = 1,498,203,203,203
BEGIN DESCRIPTION:
UNT 148 in Running Cr Watershed 2.0
END DESCRIPTION:
XS GIS Cut Line= 3
      2831964.51      7006488.35      2831812.61      7006199.74
      2831491.41      7005915.43
#Sta/Elev= 30
  4736.0  446.09  4767.6  445.56  4773.7  444.75  4796.3  443.40  4833.7  441.84
  4872.1  439.49  4893.3  438.83  4936.0  437.64  4954.5  437.41  4982.3  437.74
  4988.4  437.11  4995.7  433.60  4996.2  432.80  5001.2  432.80  5001.7  433.60
  5004.3  435.86  5011.0  438.01  5033.6  437.27  5047.9  437.39  5062.0  437.29
  5071.2  437.69  5134.8  436.38  5197.5  438.83  5219.3  440.54  5224.7  440.62
  5241.0  441.51  5265.8  443.86  5333.0  446.61  5410.8  447.18  5491.1  448.44
#Mann=7,-1,0
  4736.0    0.05       0  4936.0    0.16       0  4995.7    0.07       0
  5001.7    0.16       0  5047.9    0.12       0  5224.7    0.16       0
  5265.8    0.05       0
Bank Sta=4893.3,5197.5
Exp/Cntr=0.3,0.1

Type RM Length L Ch R = 1,295,0,0,0
BEGIN DESCRIPTION:
UNT 148 in Running Cr Watershed 1.0
END DESCRIPTION:
XS GIS Cut Line= 4
      2832023.11      7006413.29      2832026.59      7006163.28
      2831925.89      7006031.33      2831561.33      7005857.73
#Sta/Elev= 30
  4696.8  444.58  4795.1  440.05  4815.1  439.32  4835.1  439.67  4879.1  438.00
  4892.9  437.69  4925.1  437.55  4948.9  438.40  4960.6  437.44  4975.1  437.60
  4982.4  436.79  4986.7  433.23  4987.2  432.43  4992.2  432.43  4992.7  433.23
  5003.1  436.70  5010.5  437.29  5060.4  437.16  5083.0  436.52  5104.0  434.84
  5147.0  436.30  5171.4  438.00  5273.0  442.02  5304.8  441.34  5344.7  442.72
  5350.2  442.07  5376.6  444.03  5418.3  444.89  5446.6  446.49  5516.6  447.89
#Mann=8,-1,0
  4696.8    0.05       0  4795.1    0.07       0  4892.9    0.16       0
  4986.7    0.07       0  4992.7    0.16       0  5003.1    0.12       0
  5273.0    0.16       0  5376.6    0.05       0
Bank Sta=4879.1,5171.4
Exp/Cntr=0.3,0.1

Chan Stop Cuts=-1