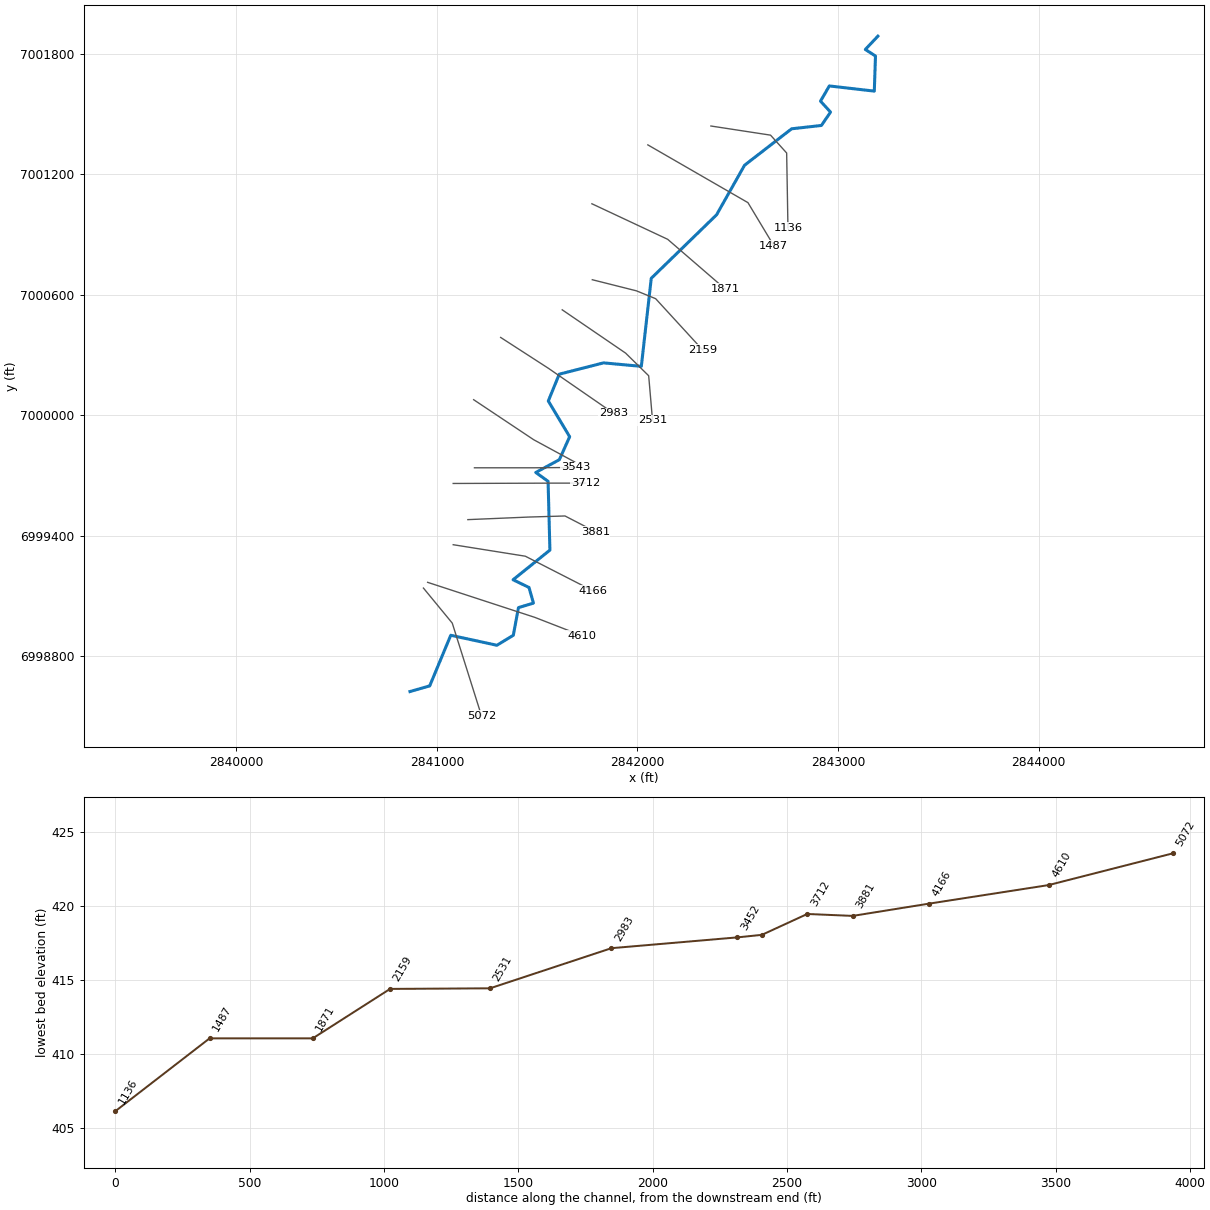
--- UNT 149 in Running Cr Watershed.prj (project) ---

Proj Title=UNT 149 in Running Cr Watershed Base Level Engineering
Current Plan=p01
Default Exp/Contr=0.3,0.1
English Units
Geom File=g01
Flow File=f01
Plan File=p01
BEGIN DESCRIPTION:
UNT 149 in Running Cr Watershed
END DESCRIPTION:

--- UNT 149 in Running Cr Watershed.p01 (plan) ---

Plan Title=Multiple Run
Short Identifier=Multiple
Geom File=g01
Flow File=f01
Subcritical Flow
K Sum by GR= 0
Std Step Tol= 0.01
Critical Tol= 0.01
Num of Std Step Trials= 20
Max Error Tol= 0.3
Flow Tol Ratio= 0.001
Split Flow NTrial= 30
Split Flow Tol= 0.02
Split Flow Ratio= 0.02
Log Output Level= 0
Friction Slope Method= 1
Unsteady Friction Slope Method= 2
Unsteady Bridges Friction Slope Method= 1
Parabolic Critical Depth
Global Vel Dist=  1 , 1 , 1
Global Log Level= 0
CheckData=True
Encroach Param= -1, 0, 0, 0
BEGIN DESCRIPTION:
Multiple Run
END DESCRIPTION:

--- UNT 149 in Running Cr Watershed.f01 (steady flow) ---

Flow Title=Multiple
Number of Profiles=7
Profile Names=10-year,25-year,50-year,1pct_min,100-year,1pct_plu,500-year
River Rch & RM= UNT 149 in Runni,Reach-1,5072
     411     537     637     376     751    1498    1043
River Rch & RM= UNT 149 in Runni,Reach-1,2983
     548     730     876     523    1043    2081    1481
River Rch & RM= UNT 149 in Runni,Reach-1,1871
     575     766     920     549    1096    2187    1558
Boundary for River Rch & Prof#=UNT 149 in Runni,Reach-1,1
Up Type=0
Dn Type=3
Dn Slope=0.005
Boundary for River Rch & Prof#=UNT 149 in Runni,Reach-1,2
Up Type=0
Dn Type=3
Dn Slope=0.005
Boundary for River Rch & Prof#=UNT 149 in Runni,Reach-1,3
Up Type=0
Dn Type=3
Dn Slope=0.005
Boundary for River Rch & Prof#=UNT 149 in Runni,Reach-1,4
Up Type=0
Dn Type=3
Dn Slope=0.005
Boundary for River Rch & Prof#=UNT 149 in Runni,Reach-1,5
Up Type=0
Dn Type=3
Dn Slope=0.005
Boundary for River Rch & Prof#=UNT 149 in Runni,Reach-1,6
Up Type=0
Dn Type=3
Dn Slope=0.005
Boundary for River Rch & Prof#=UNT 149 in Runni,Reach-1,7
Up Type=0
Dn Type=3
Dn Slope=0.005

--- UNT 149 in Running Cr Watershed.g01 (geometry) ---

Geom Title=Existing Conditions

River Reach=UNT 149 in Runni,Reach-1
Reach XY= 30
      2840866.21      6998622.23      2840964.56      6998650.67
      2841069.39      6998902.91      2841299.44      6998853.09
      2841381.21      6998902.89      2841406.80      6999040.75
      2841481.53      6999063.14      2841459.45      6999141.15
      2841380.09      6999179.57      2841563.64      6999327.34
      2841554.47      6999670.16      2841493.12      6999714.33
      2841610.73      6999778.02      2841661.99      6999892.45
      2841555.59      7000070.71      2841610.22      7000204.24
      2841830.88      7000260.59      2842019.31      7000243.22
      2842068.72      7000682.10      2842394.36      7000998.65
      2842533.71      7001245.54      2842768.47      7001427.29
      2842916.91      7001443.95      2842962.35      7001510.60
      2842912.36      7001565.12      2842956.29      7001640.86
      2843180.45      7001615.11      2843186.40      7001789.96
      2843135.71      7001822.71      2843198.43      7001889.04

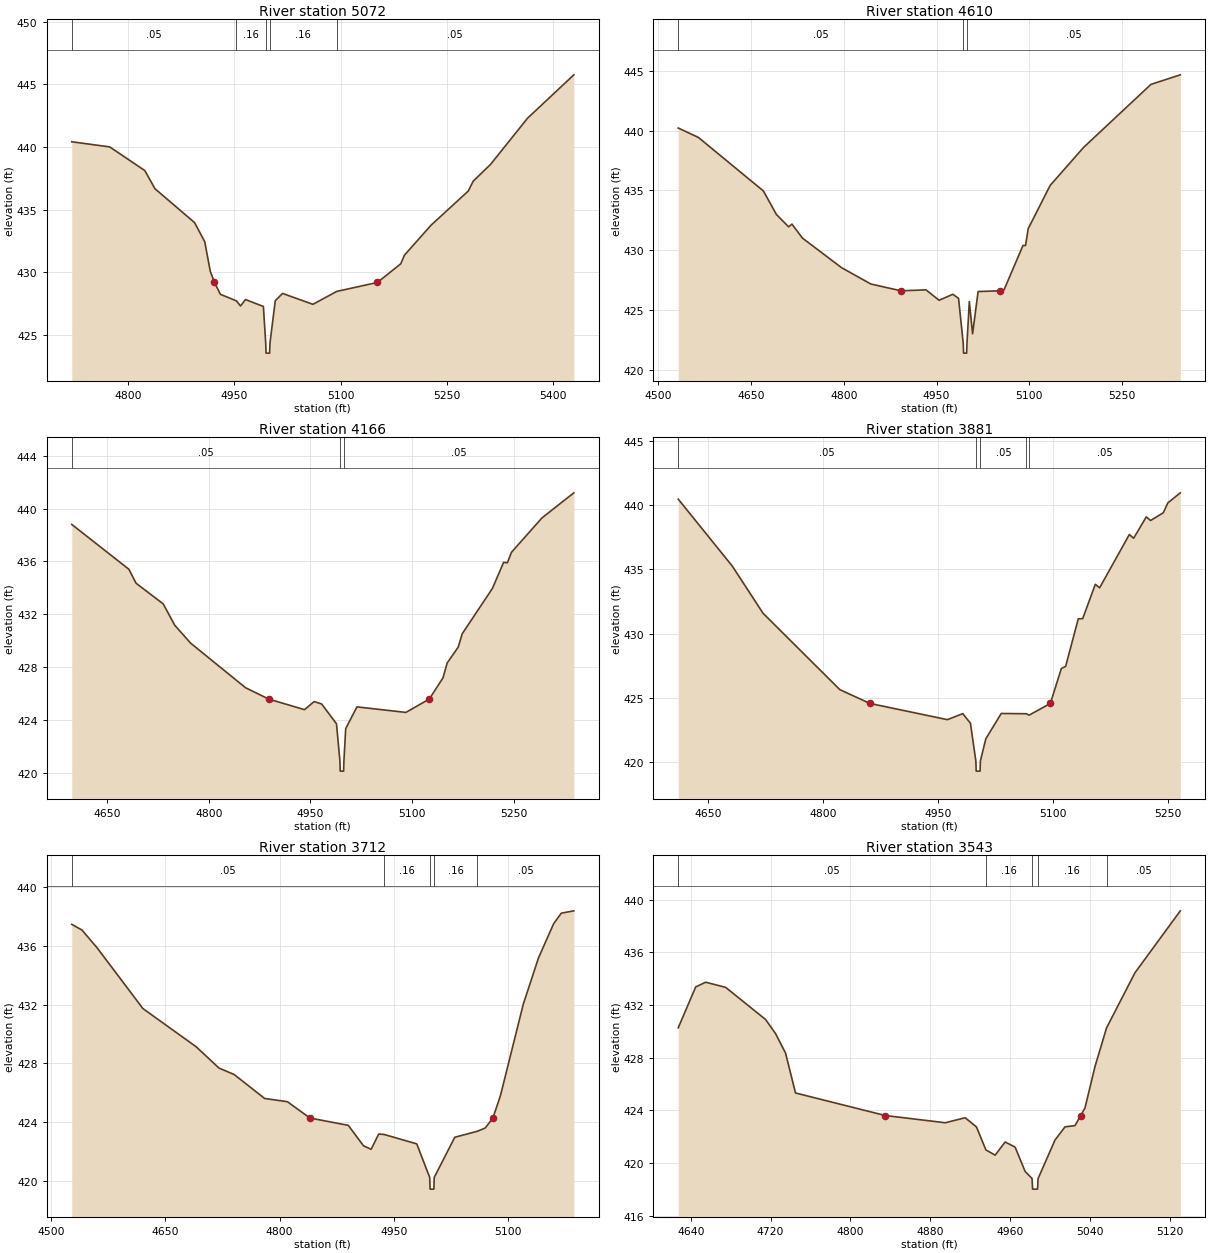
Type RM Length L Ch R = 1,5072,462,462,462
BEGIN DESCRIPTION:
UNT 149 in Running Cr Watershed 11.0
END DESCRIPTION:
XS GIS Cut Line= 3
      2840933.21      6999138.13      2841076.88      6998963.50
      2841222.28      6998502.73
#Sta/Elev= 30
  4720.2  440.42  4773.8  440.01  4823.4  438.12  4837.7  436.67  4893.7  433.96
  4908.0  432.44  4915.9  430.07  4921.8  429.18  4930.2  428.23  4952.7  427.71
  4958.6  427.30  4965.7  427.81  4990.9  427.26  4994.2  424.33  4994.7  423.53
  4999.7  423.53  5000.2  424.33  5007.7  427.72  5018.0  428.30  5060.9  427.43
  5094.5  428.46  5152.1  429.18  5185.0  430.67  5190.2  431.36  5227.9  433.76
  5280.3  436.48  5287.3  437.27  5311.8  438.61  5364.2  442.31  5429.5  445.77
#Mann=5,-1,0
  4720.2    0.05       0  4952.7    0.16       0  4994.2    0.07       0
  5000.2    0.16       0  5094.5    0.05       0
Bank Sta=4921.8,5152.1
Exp/Cntr=0.3,0.1

Type RM Length L Ch R = 1,4610,444,444,444
BEGIN DESCRIPTION:
UNT 149 in Running Cr Watershed 10.0
END DESCRIPTION:
XS GIS Cut Line= 3
      2840954.09      6999166.74      2841487.92      6998992.27
      2841721.18      6998901.56
#Sta/Elev= 30
  4532.2  440.21  4564.7  439.43  4669.9  434.95  4691.0  432.98  4710.8  431.95
  4716.1  432.18  4733.0  431.01  4796.2  428.54  4843.6  427.17  4892.4  426.60
  4932.9  426.68  4954.0  425.81  4976.3  426.31  4985.5  425.97  4993.1  422.19
  4993.6  421.39  4998.6  421.39  4999.1  422.19  5002.9  425.70  5008.2  423.01
  5017.1  426.54  5052.5  426.60  5059.2  426.70  5089.7  430.39  5093.8  430.39
  5098.1  431.79  5133.6  435.41  5187.7  438.59  5296.6  443.86  5344.1  444.66
#Mann=3,-1,0
  4532.2    0.05       0  4993.1    0.03       0  4999.1    0.05       0
Bank Sta=4892.4,5052.5
Exp/Cntr=0.3,0.1

Type RM Length L Ch R = 1,4166,285,285,285
BEGIN DESCRIPTION:
Mapping XS 2feb3da4
END DESCRIPTION:
XS GIS Cut Line= 3
      2841081.70      6999354.25      2841441.05      6999296.96
      2841776.95      6999125.10
#Sta/Elev= 30
  4597.7  438.80  4682.0  435.41  4692.7  434.35  4732.7  432.79  4749.8  431.17
  4773.2  429.82  4854.2  426.45  4888.4  425.59  4941.3  424.79  4955.5  425.40
  4966.6  425.22  4988.5  423.72  4993.5  420.94  4994.0  420.14  4999.0  420.14
  4999.5  420.94  5002.1  423.35  5018.7  425.00  5090.9  424.58  5125.5  425.59
  5145.7  427.19  5151.9  428.32  5168.2  429.52  5174.1  430.53  5218.6  433.95
  5235.2  435.93  5240.8  435.90  5246.8  436.69  5291.8  439.29  5338.9  441.19
#Mann=3,-1,0
  4597.7    0.05       0  4993.5    0.03       0  4999.5    0.05       0
Bank Sta=4888.4,5125.5
Exp/Cntr=0.3,0.1

Type RM Length L Ch R = 1,3881,169,169,169
BEGIN DESCRIPTION:
UNT 149 in Running Cr Watershed 9.0
END DESCRIPTION:
XS GIS Cut Line= 4
      2841154.57      6999479.25      2841461.88      6999492.27
      2841638.96      6999497.48      2841789.39      6999419.67
#Sta/Elev= 30
  4611.5  440.45  4682.0  435.24  4722.0  431.58  4822.1  425.64  4861.3  424.57
  4962.2  423.31  4982.2  423.78  4992.2  423.03  4999.2  420.11  4999.7  419.31
  5004.7  419.31  5005.2  420.11  5012.2  421.82  5032.3  423.79  5065.2  423.77
  5068.6  423.66  5096.3  424.57  5110.6  427.28  5116.2  427.45  5132.7  431.15
  5138.4  431.16  5154.9  433.83  5160.5  433.56  5199.2  437.70  5204.8  437.41
  5221.3  439.07  5226.9  438.79  5243.4  439.39  5249.4  440.16  5265.6  440.94
#Mann=5,-1,0
  4611.5    0.05       0  4999.2    0.03       0  5005.2    0.05       0
  5065.2    0.16       0  5068.6    0.05       0
Bank Sta=4861.3,5096.3
Exp/Cntr=0.3,0.1

Type RM Length L Ch R = 1,3712,169,169,169
BEGIN DESCRIPTION:
UNT 149 in Running Cr Watershed 8.0
END DESCRIPTION:
XS GIS Cut Line= 3
      2841081.53      6999659.52      2841598.89      6999661.25
      2841741.53      6999661.25
#Sta/Elev= 30
  4526.9  437.46  4540.4  437.07  4560.4  435.85  4620.4  431.73  4690.4  429.13
  4720.4  427.68  4740.4  427.24  4780.4  425.61  4810.4  425.39  4839.9  424.28
  4890.4  423.78  4910.4  422.39  4920.4  422.15  4930.4  423.19  4937.5  423.16
  4980.4  422.52  4997.4  420.24  4997.9  419.44  5002.9  419.44  5003.4  420.24
  5030.4  422.97  5060.2  423.38  5070.4  423.60  5080.5  424.28  5090.4  425.80
  5120.4  432.02  5140.4  435.17  5160.4  437.51  5170.4  438.22  5186.9  438.38
#Mann=5,-1,0
  4526.9    0.05       0  4937.5    0.16       0  4997.4    0.07       0
  5003.4    0.16       0  5060.2    0.05       0
Bank Sta=4839.9,5080.5
Exp/Cntr=0.3,0.1

Type RM Length L Ch R = 1,3543,91,91,91
BEGIN DESCRIPTION:
Mapping XS 8bb46118
END DESCRIPTION:
XS GIS Cut Line= 3
      2841187.45      6999737.64      2841482.57      6999737.64
      2841690.45      6999739.37
#Sta/Elev= 30
  4627.5  430.28  4645.0  433.38  4655.0  433.74  4675.0  433.35  4715.0  430.91
  4725.0  429.84  4735.0  428.36  4745.0  425.33  4834.8  423.62  4895.0  423.07
  4915.0  423.45  4926.3  422.75  4935.7  421.01  4945.0  420.61  4955.0  421.61
  4965.0  421.22  4975.0  419.38  4982.0  418.83  4982.5  418.03  4987.5  418.03
  4988.0  418.83  5005.0  421.76  5015.0  422.76  5025.0  422.85  5030.7  423.62
  5035.0  424.19  5045.0  427.33  5056.6  430.27  5085.1  434.46  5130.5  439.16
#Mann=5,-1,0
  4627.5    0.05       0  4935.7    0.16       0  4982.0    0.07       0
  4988.0    0.16       0  5056.6    0.05       0
Bank Sta=4834.8,5030.7
Exp/Cntr=0.3,0.1

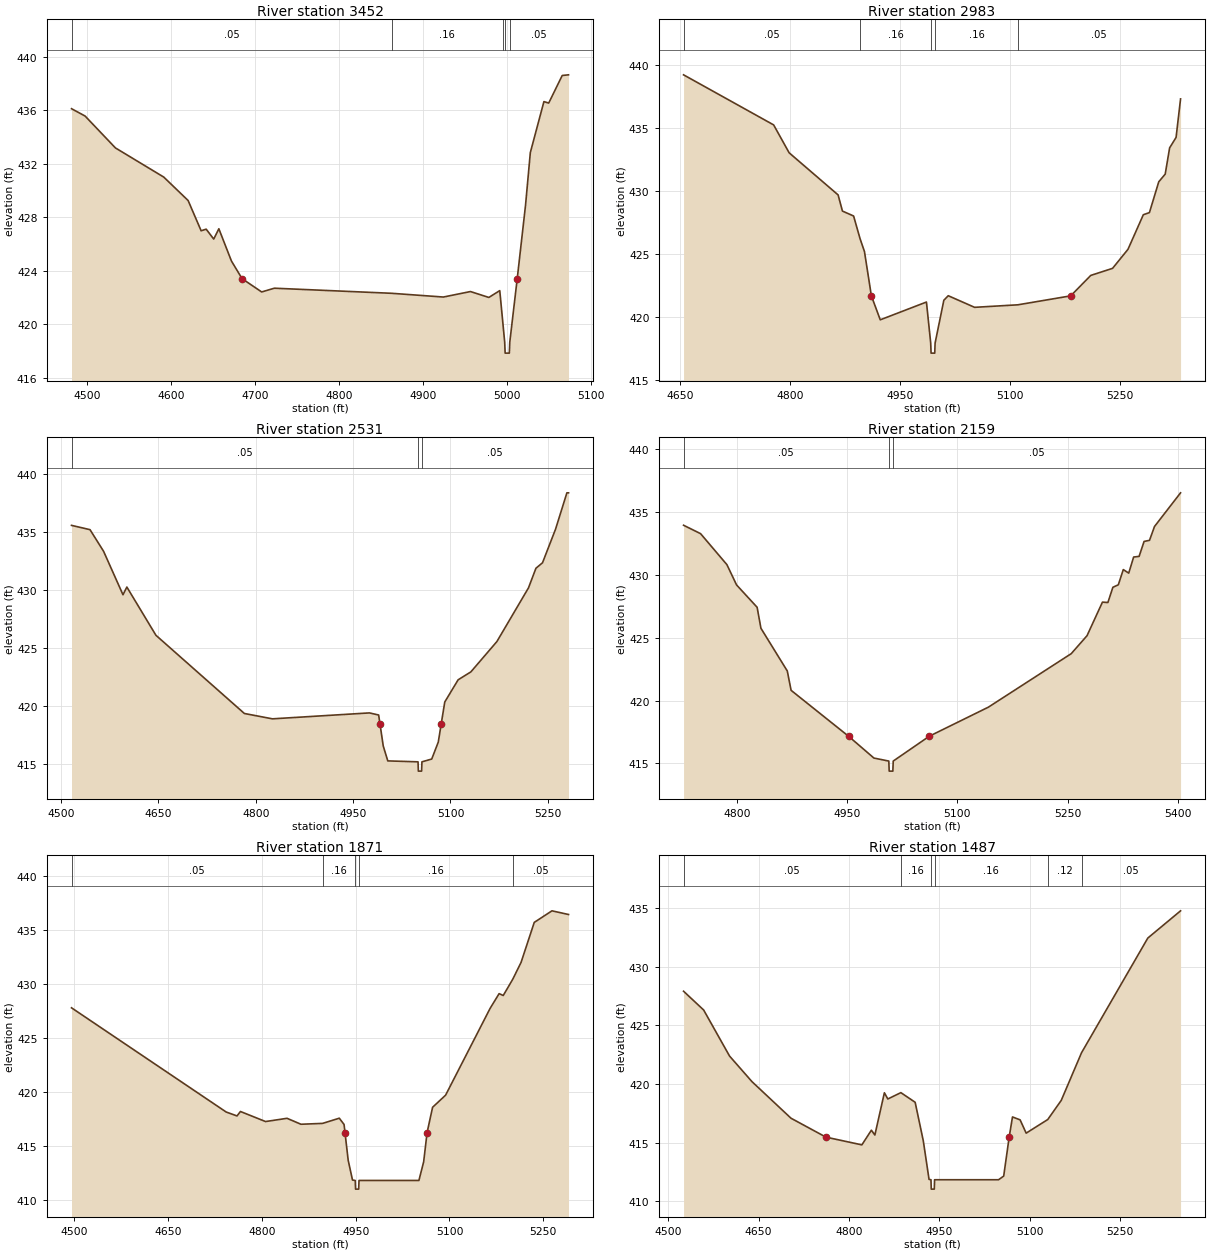
Type RM Length L Ch R = 1,3452,469,469,469
BEGIN DESCRIPTION:
UNT 149 in Running Cr Watershed 7.0
END DESCRIPTION:
XS GIS Cut Line= 3
      2841183.56      7000077.02      2841483.00      6999877.40
      2841687.03      6999766.70
#Sta/Elev= 30
  4481.5  436.12  4497.7  435.57  4533.8  433.19  4591.4  431.01  4620.4  429.26
  4635.9  427.00  4641.9  427.12  4650.9  426.38  4657.0  427.15  4672.0  424.74
  4684.7  423.42  4708.0  422.43  4723.1  422.71  4862.7  422.33  4924.4  422.05
  4956.7  422.46  4978.6  422.02  4991.6  422.53  4994.9  420.37  4997.5  418.66
  4998.0  417.86  5003.0  417.86  5003.5  418.66  5012.4  423.42  5022.3  428.91
  5028.0  432.84  5044.2  436.65  5049.9  436.54  5066.0  438.60  5073.5  438.65
#Mann=5,-1,0
  4481.5    0.05       0  4862.7    0.16       0  4994.9    0.05       0
  4997.5    0.03       0  5003.5    0.05       0
Bank Sta=4684.7,5012.4
Exp/Cntr=0.3,0.1

Type RM Length L Ch R = 1,2983,452,452,452
BEGIN DESCRIPTION:
UNT 149 in Running Cr Watershed 6.0
END DESCRIPTION:
XS GIS Cut Line= 3
      2841318.09      7000387.37      2841557.00      7000232.98
      2841879.90      7000009.94
#Sta/Elev= 30
  4655.1  439.19  4777.8  435.22  4798.9  433.01  4865.6  429.67  4871.5  428.39
  4886.7  428.00  4895.5  426.20  4901.5  425.18  4910.9  421.67  4923.0  419.77
  4985.9  421.18  4991.7  417.93  4992.2  417.13  4997.2  417.13  4997.7  417.93
  5009.6  421.32  5015.6  421.68  5051.5  420.76  5110.5  420.96  5182.4  421.67
  5209.7  423.29  5239.4  423.85  5260.4  425.36  5281.3  428.10  5289.6  428.27
  5302.3  430.71  5311.1  431.32  5317.1  433.40  5325.9  434.23  5332.0  437.28
#Mann=5,-1,0
  4655.1    0.05       0  4895.5    0.16       0  4991.7    0.07       0
  4997.7    0.16       0  5110.5    0.05       0
Bank Sta=4910.9,5182.4
Exp/Cntr=0.3,0.1

Type RM Length L Ch R = 1,2531,372,372,372
BEGIN DESCRIPTION:
UNT 149 in Running Cr Watershed 5.0
END DESCRIPTION:
XS GIS Cut Line= 4
      2841624.98      7000525.01      2841940.90      7000309.26
      2842055.92      7000196.41      2842075.00      6999975.03
#Sta/Elev= 30
  4516.0  435.57  4544.5  435.20  4565.4  433.34  4595.3  429.60  4601.3  430.26
  4646.1  426.11  4782.4  419.38  4825.6  418.92  4975.1  419.43  4989.3  419.25
  4991.3  418.51  4996.4  416.58  5003.4  415.30  5050.0  415.22  5050.5  414.42
  5055.5  414.42  5056.0  415.22  5071.1  415.46  5081.2  416.92  5085.8  418.51
  5091.2  420.37  5111.8  422.28  5131.4  422.96  5171.5  425.57  5220.2  430.19
  5231.7  431.88  5241.8  432.35  5261.9  435.24  5279.4  438.37  5281.9  438.37
#Mann=3,-1,0
  4516.0    0.05       0  5050.0    0.03       0  5056.0    0.05       0
Bank Sta=4991.3,5085.8
Exp/Cntr=0.3,0.1

Type RM Length L Ch R = 1,2159,288,288,288
BEGIN DESCRIPTION:
UNT 149 in Running Cr Watershed 4.0
END DESCRIPTION:
XS GIS Cut Line= 4
      2841774.95      7000675.01      2841995.16      7000619.59
      2842090.64      7000580.52      2842325.03      7000324.97
#Sta/Elev= 30
  4727.0  433.95  4750.2  433.28  4786.1  430.81  4799.2  429.20  4827.2  427.42
  4832.4  425.75  4868.3  422.35  4873.5  420.81  4951.7  417.16  4986.3  415.42
  5006.6  415.18  5007.1  414.38  5012.1  414.38  5012.6  415.18  5061.8  417.16
  5142.2  419.47  5255.1  423.73  5276.6  425.16  5297.6  427.83  5305.0  427.80
  5311.8  429.01  5319.2  429.21  5326.0  430.42  5333.4  430.14  5340.1  431.42
  5347.5  431.47  5354.3  432.66  5361.7  432.75  5368.5  433.85  5404.0  436.53
#Mann=3,-1,0
  4727.0    0.05       0  5006.6    0.03       0  5012.6    0.05       0
Bank Sta=4951.7,5061.8
Exp/Cntr=0.3,0.1

Type RM Length L Ch R = 1,1871,384,384,384
BEGIN DESCRIPTION:
UNT 149 in Running Cr Watershed 3.0
END DESCRIPTION:
XS GIS Cut Line= 3
      2841772.96      7001053.60      2842150.54      7000876.53
      2842436.51      7000629.56
#Sta/Elev= 30
  4495.5  427.81  4742.9  418.17  4760.2  417.81  4765.7  418.22  4805.8  417.29
  4840.2  417.59  4862.5  417.04  4897.1  417.12  4923.8  417.60  4931.4  417.02
  4932.9  416.27  4938.0  413.71  4944.9  411.88  4949.3  411.84  4949.8  411.04
  4954.8  411.04  4955.3  411.84  5051.1  411.84  5058.7  413.56  5064.2  416.27
  5073.0  418.61  5093.8  419.73  5165.1  427.77  5179.4  429.12  5186.0  428.95
  5201.1  430.44  5214.5  432.01  5235.6  435.71  5263.9  436.78  5290.4  436.44
#Mann=5,-1,0
  4495.5    0.05       0  4897.1    0.16       0  4949.3    0.07       0
  4955.3    0.16       0  5201.1    0.05       0
Bank Sta=4932.9,5064.2
Exp/Cntr=0.3,0.1

Type RM Length L Ch R = 1,1487,351,351,351
BEGIN DESCRIPTION:
UNT 149 in Running Cr Watershed 2.0
END DESCRIPTION:
XS GIS Cut Line= 3
      2842051.75      7001347.09      2842550.73      7001059.21
      2842679.18      7000845.29
#Sta/Elev= 30
  4525.3  427.90  4558.7  426.30  4601.8  422.37  4639.1  420.19  4703.8  417.08
  4761.8  415.47  4821.5  414.81  4837.3  416.06  4843.1  415.65  4858.9  419.25
  4864.6  418.72  4886.3  419.26  4910.0  418.44  4923.5  415.17  4933.1  411.87
  4936.3  411.84  4936.8  411.04  4941.8  411.04  4942.3  411.84  5048.6  411.84
  5057.1  412.15  5066.2  415.47  5071.7  417.19  5084.4  416.94  5094.4  415.81
  5130.3  416.97  5152.7  418.60  5186.4  422.66  5296.5  432.43  5350.9  434.75
#Mann=6,-1,0
  4525.3    0.05       0  4886.3    0.16       0  4936.3    0.07       0
  4942.3    0.16       0  5130.3    0.12       0  5186.4    0.05       0
Bank Sta=4761.8,5066.2
Exp/Cntr=0.3,0.1

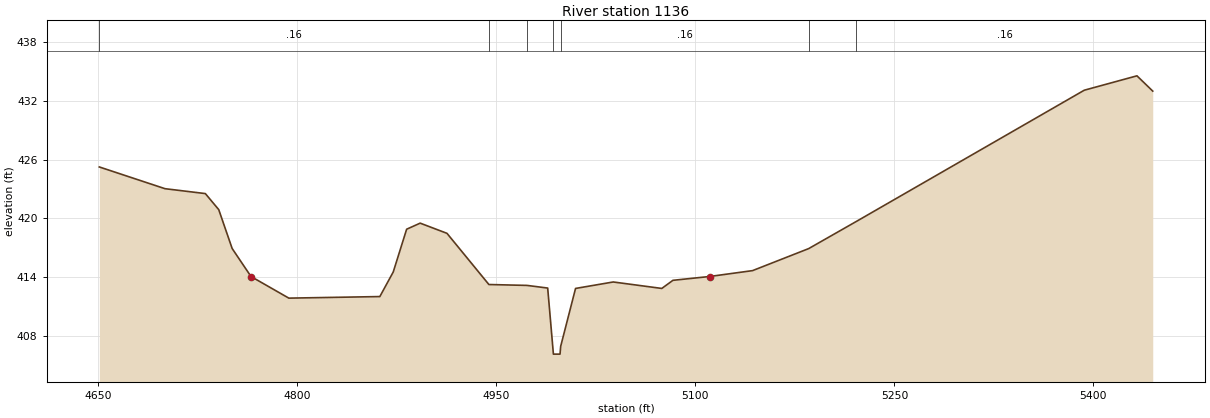
Type RM Length L Ch R = 1,1136,0,0,0
BEGIN DESCRIPTION:
UNT 149 in Running Cr Watershed 1.0
END DESCRIPTION:
XS GIS Cut Line= 4
      2842366.03      7001441.21      2842663.32      7001395.64
      2842743.62      7001306.67      2842750.13      7000933.44
#Sta/Elev= 30
  4650.8  425.24  4700.3  423.02  4730.7  422.52  4740.8  420.88  4750.9  416.91
  4765.1  414.05  4793.6  411.84  4862.2  412.00  4872.3  414.51  4882.4  418.88
  4892.6  419.50  4912.8  418.46  4944.4  413.23  4973.1  413.14  4988.7  412.87
  4992.5  406.92  4993.0  406.12  4998.0  406.12  4998.5  406.92  5009.7  412.83
  5038.1  413.49  5074.7  412.83  5083.1  413.66  5110.7  414.05  5143.1  414.65
  5185.4  416.90  5221.4  419.68  5393.1  433.08  5432.8  434.55  5444.7  432.99
#Mann=7,-1,0
  4650.8    0.16       0  4944.4    0.12       0  4973.1    0.16       0
  4992.5    0.07       0  4998.5    0.16       0  5185.4    0.12       0
  5221.4    0.16       0
Bank Sta=4765.1,5110.7
Exp/Cntr=0.3,0.1

Chan Stop Cuts=-1