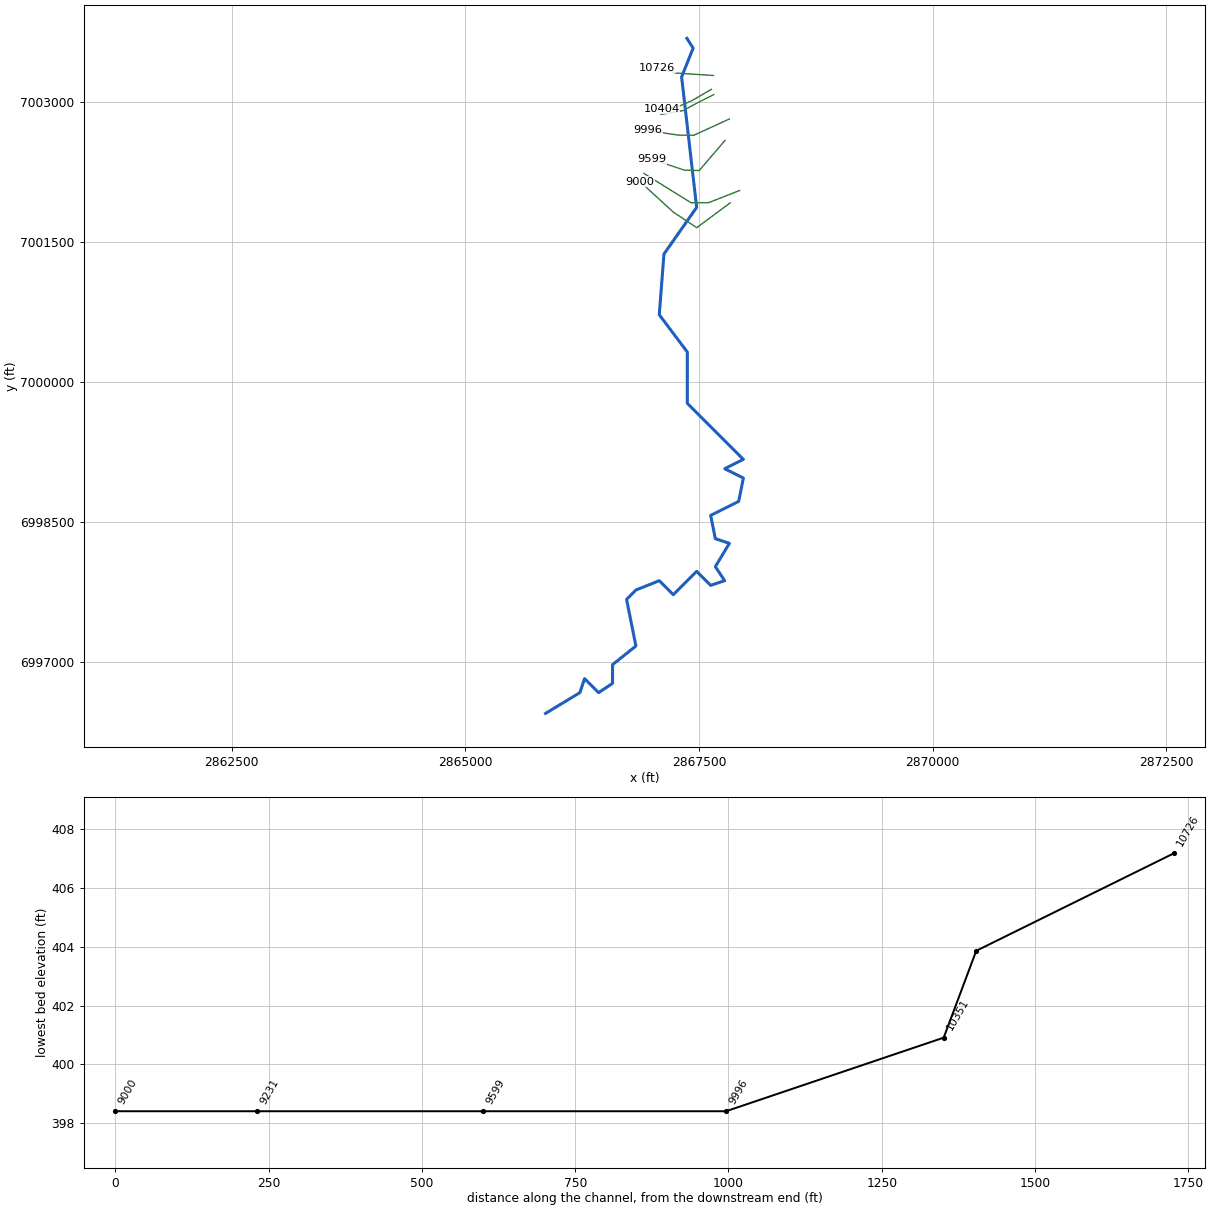
--- UNT 150 in Running Cr Watershed.prj (project) ---

Proj Title=UNT 150 in Running Cr Watershed Base Level Engineering
Current Plan=p01
Default Exp/Contr=0.3,0.1
English Units
Geom File=g01
Flow File=f01
Plan File=p01
BEGIN DESCRIPTION:
UNT 150 in Running Cr Watershed
END DESCRIPTION:

--- UNT 150 in Running Cr Watershed.p01 (plan) ---

Plan Title=Multiple Run
Short Identifier=Multiple
Geom File=g01
Flow File=f01
Subcritical Flow
K Sum by GR= 0
Std Step Tol= 0.01
Critical Tol= 0.01
Num of Std Step Trials= 20
Max Error Tol= 0.3
Flow Tol Ratio= 0.001
Split Flow NTrial= 30
Split Flow Tol= 0.02
Split Flow Ratio= 0.02
Log Output Level= 0
Friction Slope Method= 1
Unsteady Friction Slope Method= 2
Unsteady Bridges Friction Slope Method= 1
Parabolic Critical Depth
Global Vel Dist=  1 , 1 , 1
Global Log Level= 0
CheckData=True
Encroach Param= -1, 0, 0, 0
BEGIN DESCRIPTION:
Multiple Run
END DESCRIPTION:

--- UNT 150 in Running Cr Watershed.f01 (steady flow) ---

Flow Title=Multiple
Number of Profiles=7
Profile Names=10-year,25-year,50-year,1pct_min,100-year,1pct_plu,500-year
River Rch & RM= UNT 150 in Runni,Reach-1,10726
     184     224     253     143     285     568     360
Boundary for River Rch & Prof#=UNT 150 in Runni,Reach-1,1
Up Type=0
Dn Type=3
Dn Slope=0.005
Boundary for River Rch & Prof#=UNT 150 in Runni,Reach-1,2
Up Type=0
Dn Type=3
Dn Slope=0.005
Boundary for River Rch & Prof#=UNT 150 in Runni,Reach-1,3
Up Type=0
Dn Type=3
Dn Slope=0.005
Boundary for River Rch & Prof#=UNT 150 in Runni,Reach-1,4
Up Type=0
Dn Type=3
Dn Slope=0.005
Boundary for River Rch & Prof#=UNT 150 in Runni,Reach-1,5
Up Type=0
Dn Type=3
Dn Slope=0.005
Boundary for River Rch & Prof#=UNT 150 in Runni,Reach-1,6
Up Type=0
Dn Type=3
Dn Slope=0.005
Boundary for River Rch & Prof#=UNT 150 in Runni,Reach-1,7
Up Type=0
Dn Type=3
Dn Slope=0.005

--- UNT 150 in Running Cr Watershed.g01 (geometry) ---

Geom Title=Existing Conditions

River Reach=UNT 150 in Runni,Reach-1
Reach XY= 30
      2867370.49      7003686.75      2867437.33      7003581.72
      2867314.07      7003272.91      2867475.00      7001875.00
      2867125.00      7001375.00      2867075.00      7000725.00
      2867375.00      7000325.00      2867375.00      6999775.00
      2867975.00      6999175.00      2867775.00      6999075.00
      2867975.00      6998975.00      2867925.00      6998725.00
      2867625.00      6998575.00      2867675.00      6998325.00
      2867825.00      6998275.00      2867675.00      6998025.00
      2867775.00      6997875.00      2867625.00      6997825.00
      2867475.00      6997975.00      2867225.00      6997725.00
      2867075.00      6997875.00      2866825.00      6997775.00
      2866725.00      6997675.00      2866825.00      6997175.00
      2866575.00      6996975.00      2866575.00      6996775.00
      2866425.00      6996675.00      2866275.00      6996825.00
      2866225.00      6996675.00      2865858.29      6996452.98

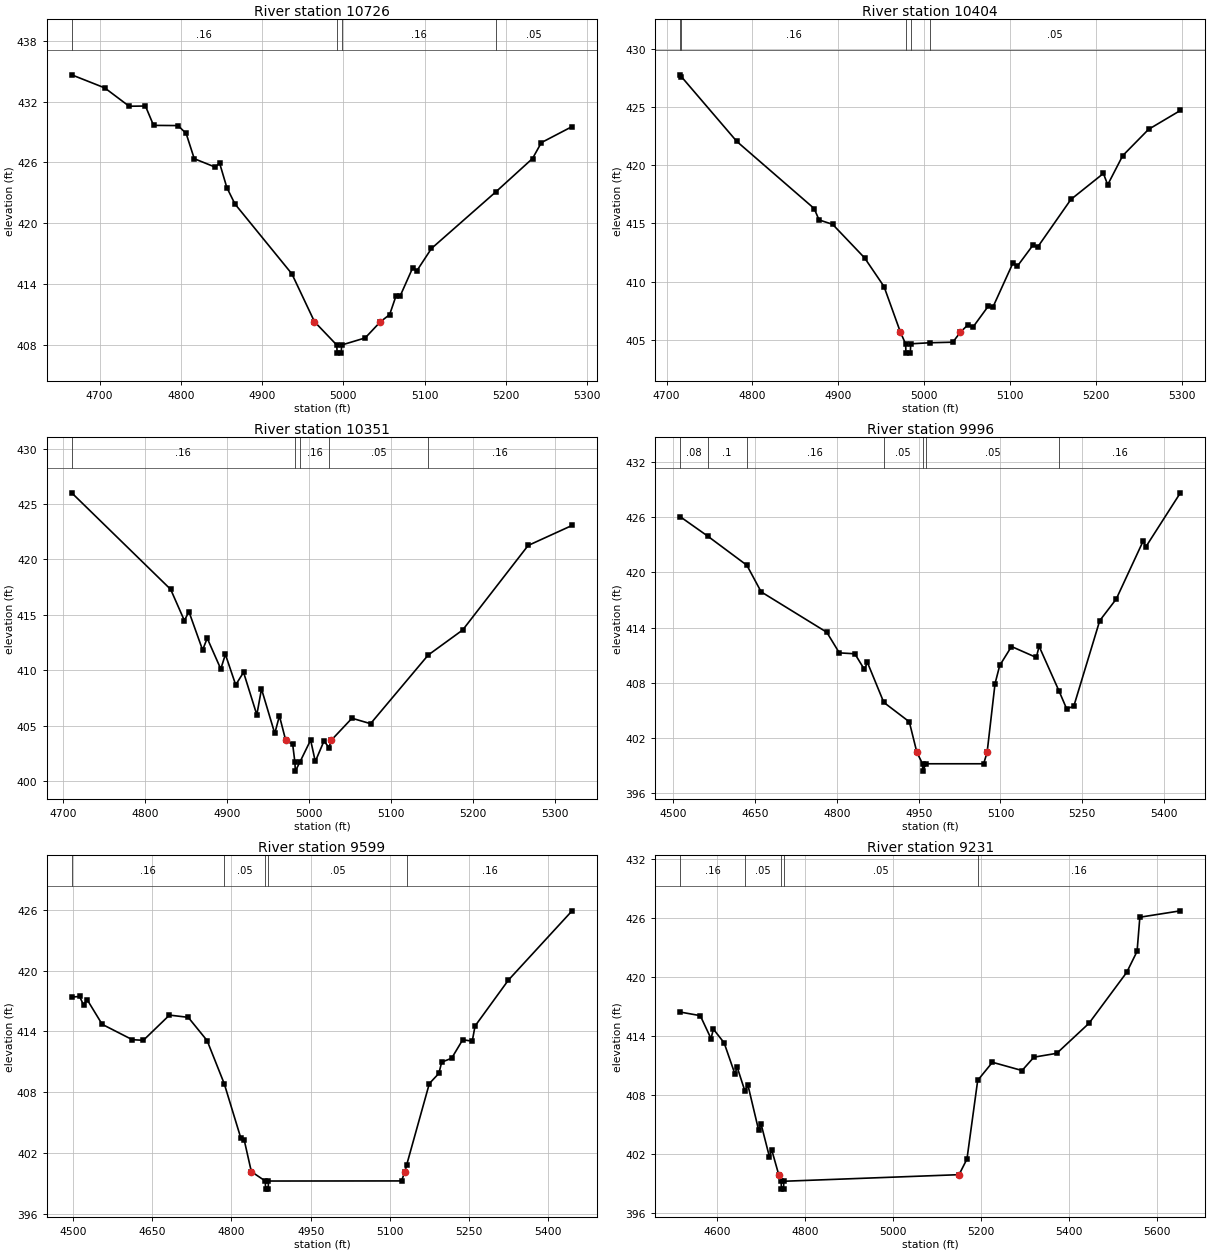
Type RM Length L Ch R = 1,10726,322,322,322
BEGIN DESCRIPTION:
UNT 150 in Running Cr Watershed 16.0
END DESCRIPTION:
XS GIS Cut Line= 3
      2867655.58      7003288.46      2867254.57      7003314.50
      2867048.09      7003371.28
#Sta/Elev= 30
  4665.6  434.64  4706.3  433.35  4736.3  431.54  4756.4  431.56  4766.4  429.65
  4796.5  429.63  4806.5  428.85  4816.5  426.36  4842.6  425.52  4847.6  425.95
  4856.6  423.51  4866.6  421.89  4936.7  414.99  4964.5  410.27  4991.9  407.97
  4992.4  407.17  4997.4  407.17  4997.9  407.97  5026.9  408.67  5045.7  410.27
  5057.0  410.97  5064.7  412.78  5069.8  412.78  5085.4  415.59  5090.6  415.31
  5108.5  417.50  5188.2  423.12  5232.9  426.38  5243.8  427.95  5281.6  429.53
#Mann=4,-1,0
  4665.6    0.16       0  4991.9    0.07       0  4997.9    0.16       0
  5188.2    0.05       0
Bank Sta=4964.5,5045.7
Exp/Cntr=0.3,0.1

Type RM Length L Ch R = 1,10404,53,53,53
BEGIN DESCRIPTION:
Mapping XS 3ee22d48
END DESCRIPTION:
XS GIS Cut Line= 4
      2867632.16      7003140.02      2867429.05      7003021.97
      2867263.25      7002948.18      2867098.25      7002931.00
#Sta/Elev= 30
  4715.7  427.76  4717.2  427.61  4781.8  422.04  4871.8  416.28  4877.5  415.30
  4893.3  414.92  4930.5  412.04  4953.1  409.58  4972.2  405.66  4978.2  404.66
  4978.7  403.86  4983.7  403.86  4984.2  404.66  5006.3  404.75  5033.2  404.80
  5042.0  405.66  5051.0  406.31  5056.4  406.07  5074.2  407.87  5079.7  407.79
  5102.9  411.56  5108.4  411.34  5126.2  413.11  5132.1  412.99  5170.6  417.06
  5208.4  419.29  5213.4  418.32  5230.9  420.82  5261.0  423.08  5298.0  424.70
#Mann=5,-1,0
  4715.7    0.05       0  4717.2    0.16       0  4978.2    0.07       0
  4984.2    0.16       0  5006.3    0.05       0
Bank Sta=4972.2,5042
Exp/Cntr=0.3,0.1

Type RM Length L Ch R = 1,10351,355,355,355
BEGIN DESCRIPTION:
UNT 150 in Running Cr Watershed 15.0
END DESCRIPTION:
XS GIS Cut Line= 4
      2867658.67      7003084.26      2867479.96      7002993.70
      2867327.70      7002911.72      2867093.28      7002871.57
#Sta/Elev= 30
  4710.2  426.01  4831.1  417.30  4847.8  414.49  4853.4  415.29  4870.1  411.83
  4875.7  412.90  4892.3  410.12  4897.9  411.44  4910.5  408.69  4920.1  409.82
  4936.3  405.99  4942.0  408.32  4958.2  404.31  4963.9  405.89  4971.6  403.68
  4980.1  403.32  4982.8  401.71  4983.3  400.91  4988.8  401.71  5002.0  403.71
  5007.7  401.78  5018.3  403.62  5024.5  403.03  5027.0  403.68  5052.5  405.68
  5075.2  405.19  5145.6  411.38  5187.7  413.64  5267.6  421.26  5321.3  423.07
#Mann=5,-1,0
  4710.2    0.16       0  4982.8    0.07       0  4988.8    0.16       0
  5024.5    0.05       0  5145.6    0.16       0
Bank Sta=4971.6,5027
Exp/Cntr=0.3,0.1

Type RM Length L Ch R = 1,9996,397,397,397
BEGIN DESCRIPTION:
Mapping XS a9d8e710
END DESCRIPTION:
XS GIS Cut Line= 4
      2867824.87      7002822.31      2867444.67      7002647.84
      2867272.80      7002650.44      2866948.64      7002699.71
#Sta/Elev= 30
  4512.0  426.07  4562.5  423.96  4634.7  420.78  4660.9  417.89  4781.3  413.50
  4804.3  411.26  4832.8  411.16  4850.3  409.46  4855.8  410.23  4885.9  405.88
  4932.7  403.77  4946.6  400.45  4957.0  399.21  4957.5  398.41  4963.0  399.21
  5069.1  399.21  5075.5  400.45  5090.0  407.91  5098.6  409.89  5120.2  411.95
  5165.8  410.76  5170.8  411.98  5207.6  407.09  5221.4  405.18  5234.5  405.46
  5282.1  414.76  5312.4  417.11  5361.7  423.40  5366.7  422.78  5430.1  428.65
#Mann=7,-1,0
  4512.0    0.08       0  4562.5     0.1       0  4634.7    0.16       0
  4885.9    0.05       0  4957.0   0.033       0  4963.0    0.05       0
  5207.6    0.16       0
Bank Sta=4946.6,5075.5
Exp/Cntr=0.3,0.1

Type RM Length L Ch R = 1,9599,368,368,368
BEGIN DESCRIPTION:
UNT 150 in Running Cr Watershed 14.0
END DESCRIPTION:
XS GIS Cut Line= 4
      2867778.58      7002592.65      2867502.53      7002269.73
      2867341.07      7002274.94      2866998.67      7002389.07
#Sta/Elev= 30
  4497.6  417.38  4512.5  417.44  4520.2  416.59  4526.8  417.13  4555.3  414.69
  4612.4  413.17  4633.3  413.11  4682.7  415.60  4718.2  415.38  4754.0  413.08
  4786.5  408.81  4817.7  403.47  4824.3  403.24  4837.7  400.14  4864.1  399.21
  4864.6  398.41  4869.6  398.41  4870.1  399.21  5122.0  399.22  5128.4  400.14
  5131.8  400.81  5174.7  408.84  5192.7  409.84  5198.0  410.95  5216.9  411.34
  5237.9  413.17  5255.9  413.02  5261.2  414.52  5324.4  419.06  5444.9  425.90
#Mann=5,-1,0
  4497.6    0.16       0  4786.5    0.05       0  4864.1   0.033       0
  4870.1    0.05       0  5131.8    0.16       0
Bank Sta=4837.7,5128.4
Exp/Cntr=0.3,0.1

Type RM Length L Ch R = 1,9231,231,231,231
BEGIN DESCRIPTION:
UNT 150 in Running Cr Watershed 13.0
END DESCRIPTION:
XS GIS Cut Line= 4
      2867934.79      7002056.18      2867604.09      7001925.98
      2867415.12      7001924.89      2866911.34      7002238.50
#Sta/Elev= 30
  4515.5  416.42  4561.6  416.05  4586.0  413.72  4591.4  414.68  4615.8  413.29
  4640.2  410.14  4645.6  410.80  4662.9  408.41  4670.0  408.98  4694.4  404.38
  4699.7  405.06  4718.8  401.70  4724.1  402.39  4740.0  399.88  4745.5  399.21
  4746.0  398.41  4751.0  398.41  4751.5  399.21  5150.0  399.88  5168.0  401.47
  5192.4  409.47  5225.9  411.31  5293.2  410.47  5320.3  411.83  5372.2  412.22
  5445.4  415.27  5531.2  420.45  5554.8  422.59  5561.1  426.06  5653.3  426.71
#Mann=5,-1,0
  4515.5    0.16       0  4662.9    0.05       0  4745.5   0.033       0
  4751.5    0.05       0  5192.4    0.16       0
Bank Sta=4740,5150
Exp/Cntr=0.3,0.1

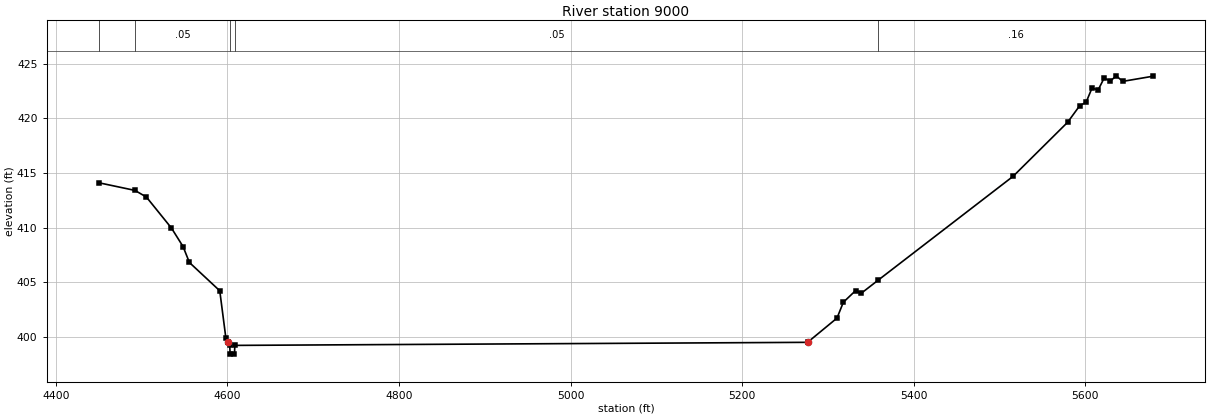
Type RM Length L Ch R = 1,9000,0,0,0
BEGIN DESCRIPTION:
UNT 150 in Running Cr Watershed 12.0
END DESCRIPTION:
XS GIS Cut Line= 4
      2867833.27      7001923.39      2867476.49      7001657.75
      2867225.00      7001825.00      2866869.98      7002149.92
#Sta/Elev= 30
  4450.6  414.09  4492.1  413.40  4505.5  412.79  4534.7  409.95  4548.2  408.26
  4555.6  406.80  4591.0  404.21  4598.1  399.89  4600.8  399.49  4602.6  399.21
  4603.1  398.41  4608.1  398.41  4608.6  399.21  5276.3  399.49  5310.6  401.71
  5318.0  403.16  5332.2  404.22  5339.0  403.99  5358.9  405.20  5515.9  414.69
  5579.5  419.64  5593.6  421.16  5601.0  421.47  5607.8  422.75  5615.2  422.62
  5622.0  423.68  5629.4  423.42  5636.2  423.89  5643.6  423.38  5678.7  423.85
#Mann=5,-1,0
  4450.6    0.16       0  4492.1    0.05       0  4602.6   0.033       0
  4608.6    0.05       0  5358.9    0.16       0
Bank Sta=4600.8,5276.3
Exp/Cntr=0.3,0.1

Chan Stop Cuts=-1