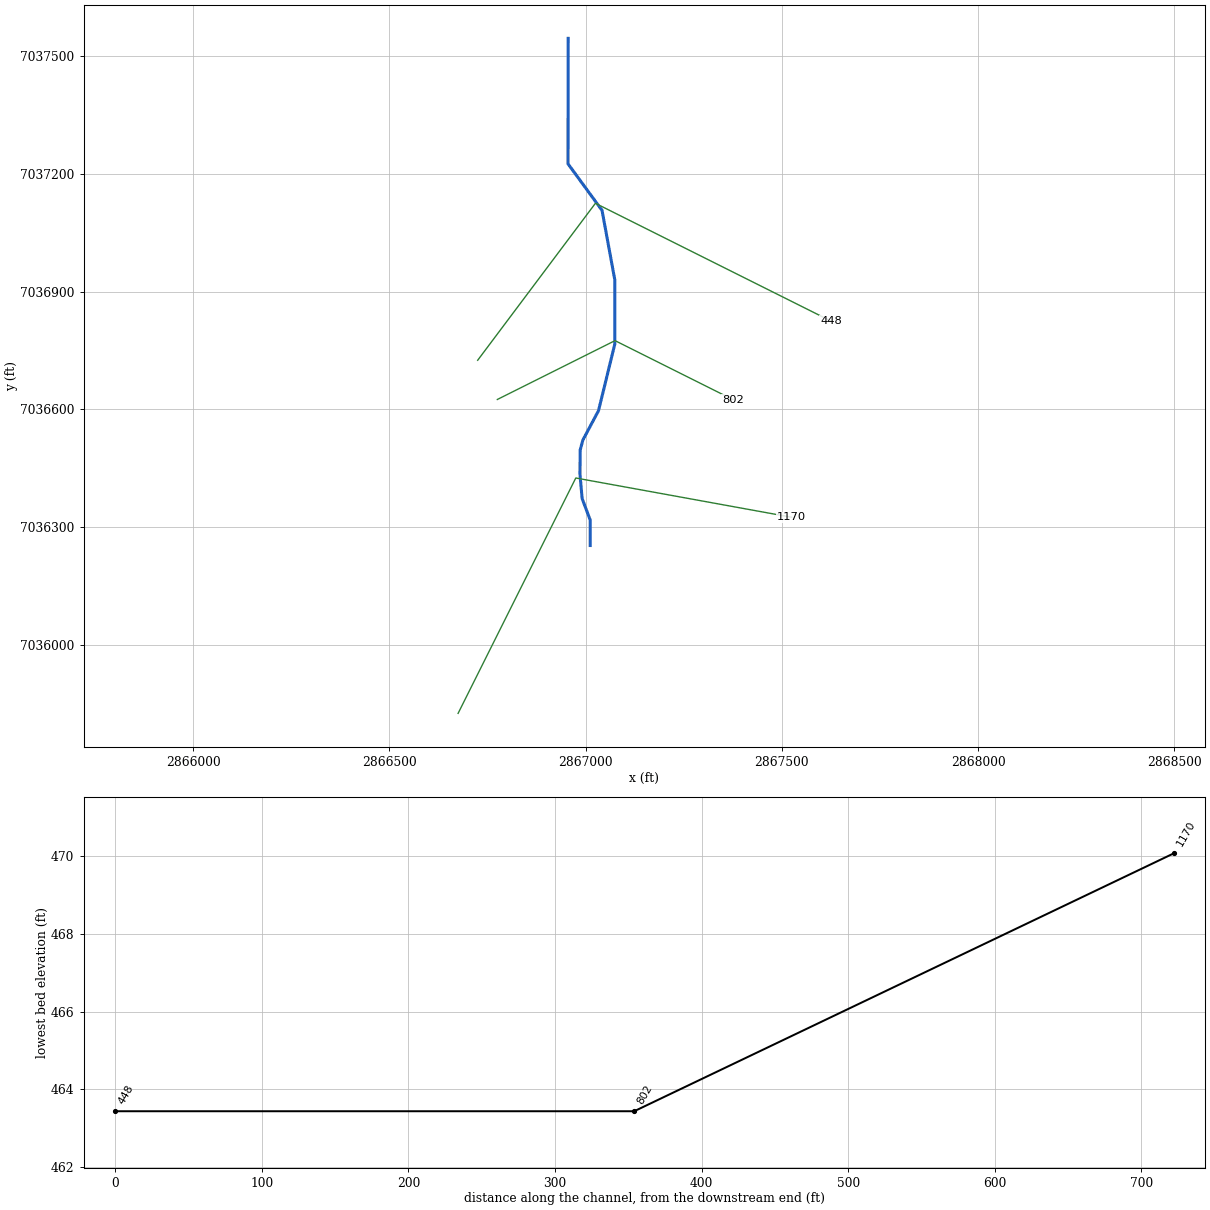
--- UNT 151 in Running Cr Watershed.prj (project) ---

Proj Title=UNT 151 in Running Cr Watershed Base Level Engineering
Current Plan=p01
Default Exp/Contr=0.3,0.1
English Units
Geom File=g01
Flow File=f01
Plan File=p01
BEGIN DESCRIPTION:
UNT 151 in Running Cr Watershed
END DESCRIPTION:

--- UNT 151 in Running Cr Watershed.p01 (plan) ---

Plan Title=Multiple Run
Short Identifier=Multiple
Geom File=g01
Flow File=f01
Subcritical Flow
K Sum by GR= 0
Std Step Tol= 0.01
Critical Tol= 0.01
Num of Std Step Trials= 20
Max Error Tol= 0.3
Flow Tol Ratio= 0.001
Split Flow NTrial= 30
Split Flow Tol= 0.02
Split Flow Ratio= 0.02
Log Output Level= 0
Friction Slope Method= 1
Unsteady Friction Slope Method= 2
Unsteady Bridges Friction Slope Method= 1
Parabolic Critical Depth
Global Vel Dist=  1 , 1 , 1
Global Log Level= 0
CheckData=True
Encroach Param= -1, 0, 0, 0
BEGIN DESCRIPTION:
Multiple Run
END DESCRIPTION:

--- UNT 151 in Running Cr Watershed.f01 (steady flow) ---

Flow Title=Multiple
Number of Profiles=7
Profile Names=10-year,25-year,50-year,1pct_min,100-year,1pct_plu,500-year
River Rch & RM= UNT 151 in Runni,Reach-1,1170
     118     142     159      89     178     354     221
Boundary for River Rch & Prof#=UNT 151 in Runni,Reach-1,1
Up Type=0
Dn Type=3
Dn Slope=0.005
Boundary for River Rch & Prof#=UNT 151 in Runni,Reach-1,2
Up Type=0
Dn Type=3
Dn Slope=0.005
Boundary for River Rch & Prof#=UNT 151 in Runni,Reach-1,3
Up Type=0
Dn Type=3
Dn Slope=0.005
Boundary for River Rch & Prof#=UNT 151 in Runni,Reach-1,4
Up Type=0
Dn Type=3
Dn Slope=0.005
Boundary for River Rch & Prof#=UNT 151 in Runni,Reach-1,5
Up Type=0
Dn Type=3
Dn Slope=0.005
Boundary for River Rch & Prof#=UNT 151 in Runni,Reach-1,6
Up Type=0
Dn Type=3
Dn Slope=0.005
Boundary for River Rch & Prof#=UNT 151 in Runni,Reach-1,7
Up Type=0
Dn Type=3
Dn Slope=0.005

--- UNT 151 in Running Cr Watershed.g01 (geometry) ---

Geom Title=Existing Conditions

River Reach=UNT 151 in Runni,Reach-1
Reach XY= 12
      2867011.94      7036252.97      2867011.94      7036317.21
      2866991.11      7036372.76      2866985.59      7036435.71
      2866986.21      7036496.39      2866993.07      7036521.75
      2867032.88      7036596.45      2867074.37      7036766.01
      2867074.37      7036930.16      2867041.90      7037106.94
      2866955.17      7037225.54      2866955.59      7037545.36

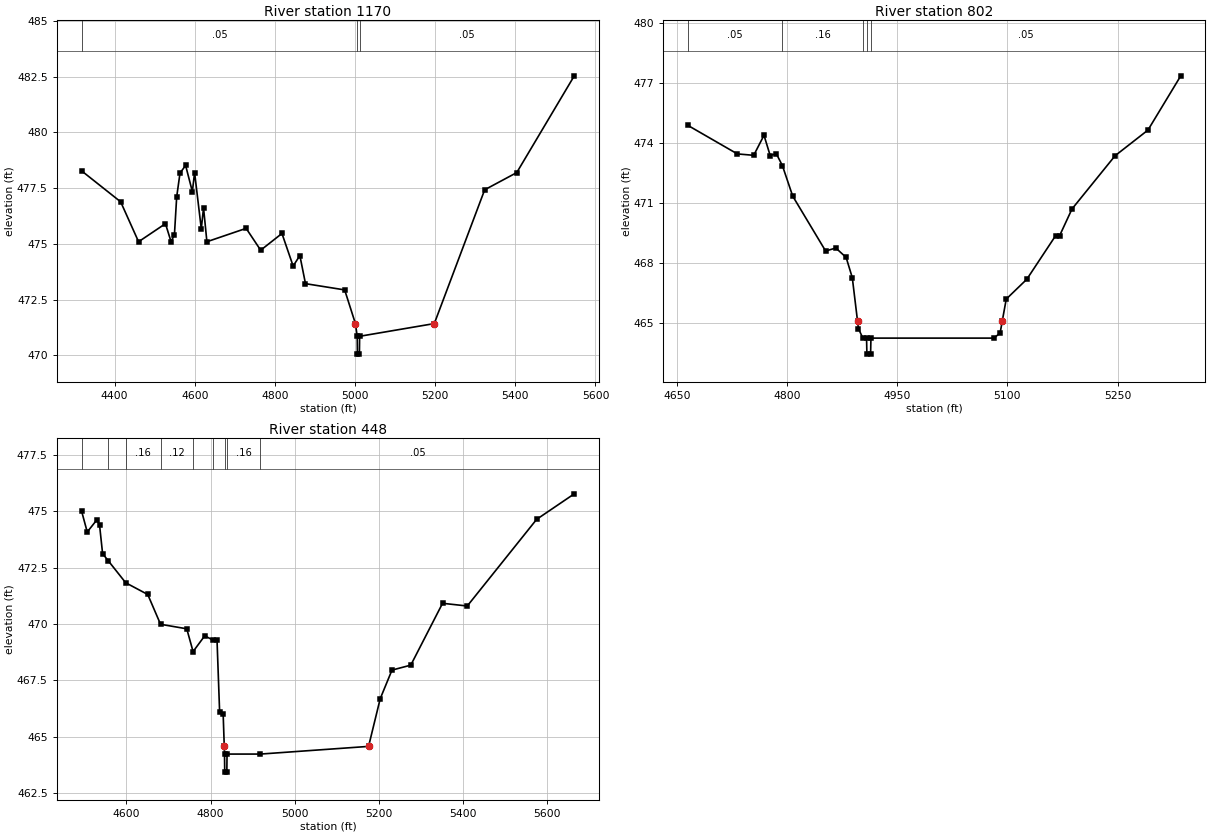
Type RM Length L Ch R = 1,1170,368,368,368
BEGIN DESCRIPTION:
UNT 151 in Running Cr Watershed 3.0
END DESCRIPTION:
XS GIS Cut Line= 3
      2866675.10      7035825.20      2866975.00      7036425.00
      2867524.99      7036325.00
#Sta/Elev= 30
  4317.5  478.28  4415.1  476.89  4459.8  475.10  4526.9  475.91  4540.9  475.10
  4549.3  475.42  4554.9  477.11  4563.2  478.18  4577.2  478.52  4594.0  477.35
  4599.6  478.20  4616.3  475.68  4621.9  476.62  4630.3  475.10  4728.2  475.70
  4764.5  474.72  4817.6  475.47  4845.5  474.01  4862.3  474.48  4876.3  473.22
  4974.1  472.94  5000.9  471.43  5005.4  470.86  5005.9  470.06  5010.9  470.06
  5011.4  470.86  5197.8  471.43  5323.5  477.43  5403.5  478.20  5547.1  482.54
#Mann=3,-1,0
  4317.5    0.05       0  5005.4    0.03       0  5011.4    0.05       0
Bank Sta=5000.9,5197.8
Exp/Cntr=0.3,0.1

Type RM Length L Ch R = 1,802,354,354,354
BEGIN DESCRIPTION:
UNT 151 in Running Cr Watershed 2.0
END DESCRIPTION:
XS GIS Cut Line= 3
      2866775.00      7036625.00      2867075.00      7036775.00
      2867374.98      7036625.01
#Sta/Elev= 30
  4665.3  474.86  4732.4  473.44  4754.7  473.37  4768.7  474.37  4777.1  473.36
  4785.5  473.45  4793.8  472.85  4807.8  471.33  4852.6  468.59  4866.5  468.74
  4880.5  468.27  4888.9  467.26  4896.0  465.10  4897.3  464.71  4903.3  464.24
  4908.3  464.24  4908.8  463.44  4913.8  463.44  4914.3  464.24  5081.8  464.24
  5090.2  464.50  5093.1  465.10  5098.5  466.19  5126.5  467.18  5165.6  469.35
  5171.2  469.36  5188.0  470.69  5246.7  473.35  5291.4  474.63  5336.1  477.34
#Mann=5,-1,0
  4665.3    0.05       0  4793.8    0.16       0  4903.3    0.05       0
  4908.3   0.033       0  4914.3    0.05       0
Bank Sta=4896,5093.1
Exp/Cntr=0.3,0.1

Type RM Length L Ch R = 1,448,0,0,0
BEGIN DESCRIPTION:
UNT 151 in Running Cr Watershed 1.0
END DESCRIPTION:
XS GIS Cut Line= 3
      2866725.00      7036725.00      2867025.00      7037125.00
      2867624.98      7036825.01
#Sta/Elev= 30
  4493.5  475.01  4507.0  474.08  4530.0  474.62  4536.2  474.40  4543.5  473.12
  4556.7  472.81  4598.4  471.83  4650.8  471.31  4681.2  469.99  4743.5  469.79
  4758.5  468.78  4786.2  469.48  4805.7  469.29  4815.4  469.29  4821.6  466.09
  4830.0  466.01  4832.6  464.58  4833.2  464.24  4833.7  463.44  4838.7  463.44
  4839.2  464.24  4918.6  464.24  5175.5  464.58  5203.1  466.69  5231.1  467.96
  5275.8  468.18  5351.3  470.92  5410.0  470.80  5574.9  474.64  5664.3  475.77
#Mann=9,-1,0
  4493.5    0.05       0  4556.7    0.12       0  4598.4    0.16       0
  4681.2    0.12       0  4758.5    0.05       0  4805.7    0.16       0
  4833.2   0.033       0  4839.2    0.16       0  4918.6    0.05       0
Bank Sta=4832.6,5175.5
Exp/Cntr=0.3,0.1

Chan Stop Cuts=-1