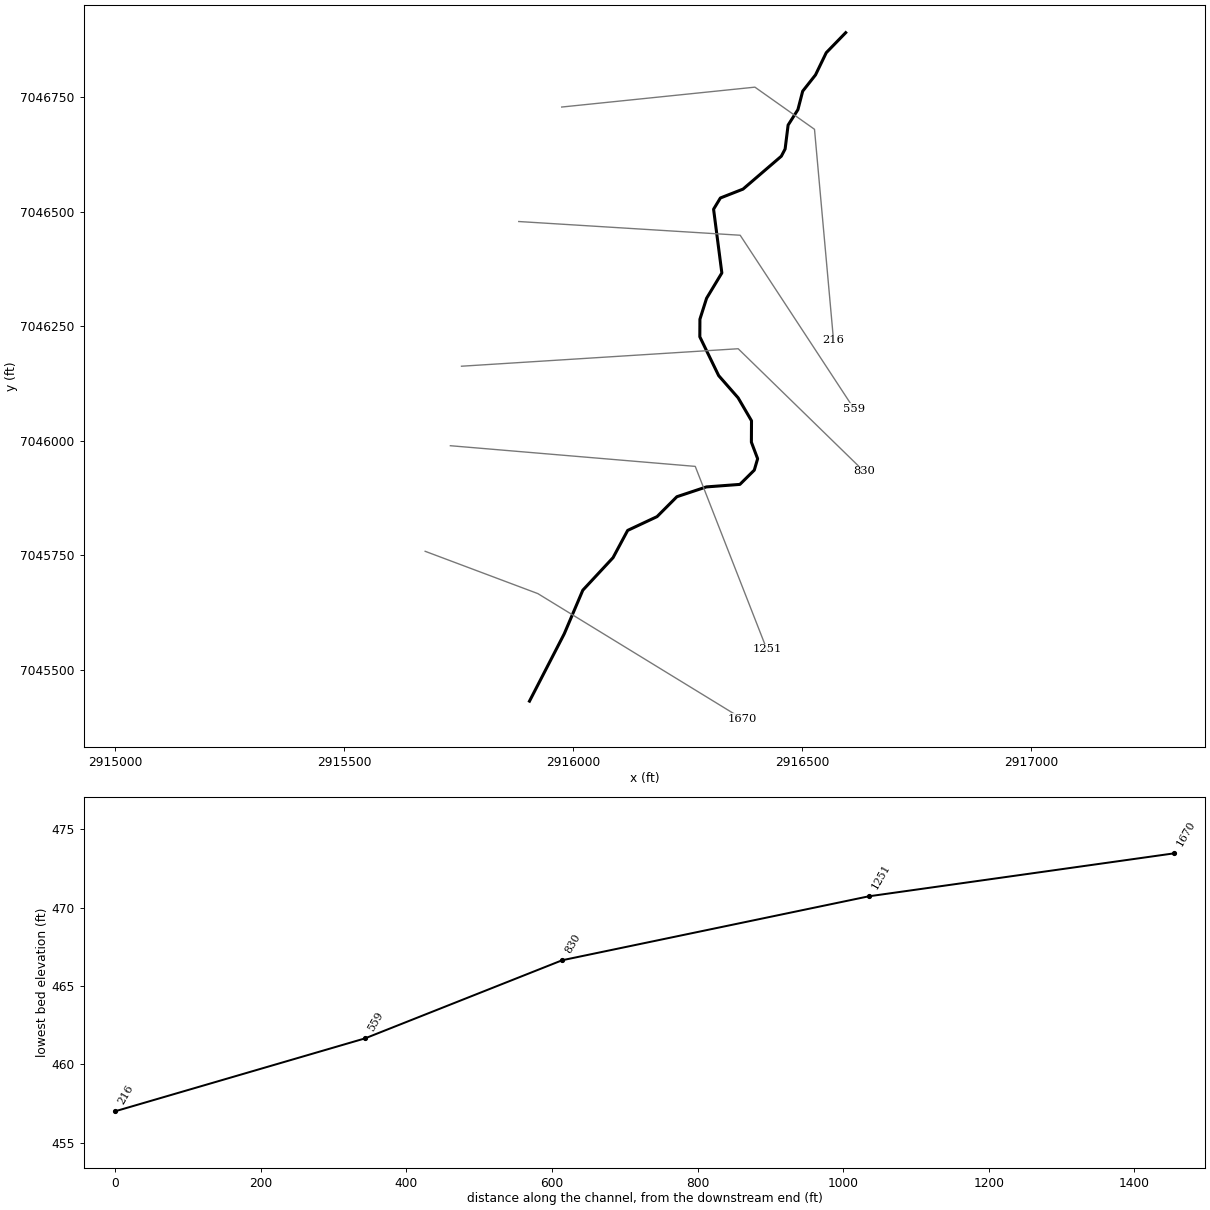
--- UNT 152 in Running Cr Watershed.prj (project) ---

Proj Title=UNT 152 in Running Cr Watershed Base Level Engineering
Current Plan=p01
Default Exp/Contr=0.3,0.1
English Units
Geom File=g01
Flow File=f01
Plan File=p01
BEGIN DESCRIPTION:
UNT 152 in Running Cr Watershed
END DESCRIPTION:

--- UNT 152 in Running Cr Watershed.p01 (plan) ---

Plan Title=Multiple Run
Short Identifier=Multiple
Geom File=g01
Flow File=f01
Subcritical Flow
K Sum by GR= 0
Std Step Tol= 0.01
Critical Tol= 0.01
Num of Std Step Trials= 20
Max Error Tol= 0.3
Flow Tol Ratio= 0.001
Split Flow NTrial= 30
Split Flow Tol= 0.02
Split Flow Ratio= 0.02
Log Output Level= 0
Friction Slope Method= 1
Unsteady Friction Slope Method= 2
Unsteady Bridges Friction Slope Method= 1
Parabolic Critical Depth
Global Vel Dist=  1 , 1 , 1
Global Log Level= 0
CheckData=True
Encroach Param= -1, 0, 0, 0
BEGIN DESCRIPTION:
Multiple Run
END DESCRIPTION:

--- UNT 152 in Running Cr Watershed.f01 (steady flow) ---

Flow Title=Multiple
Number of Profiles=7
Profile Names=10-year,25-year,50-year,1pct_min,100-year,1pct_plu,500-year
River Rch & RM= UNT 152 in Runni,Reach-1,1670
     200     251     290     168     334     667     443
Boundary for River Rch & Prof#=UNT 152 in Runni,Reach-1,1
Up Type=0
Dn Type=3
Dn Slope=0.005
Boundary for River Rch & Prof#=UNT 152 in Runni,Reach-1,2
Up Type=0
Dn Type=3
Dn Slope=0.005
Boundary for River Rch & Prof#=UNT 152 in Runni,Reach-1,3
Up Type=0
Dn Type=3
Dn Slope=0.005
Boundary for River Rch & Prof#=UNT 152 in Runni,Reach-1,4
Up Type=0
Dn Type=3
Dn Slope=0.005
Boundary for River Rch & Prof#=UNT 152 in Runni,Reach-1,5
Up Type=0
Dn Type=3
Dn Slope=0.005
Boundary for River Rch & Prof#=UNT 152 in Runni,Reach-1,6
Up Type=0
Dn Type=3
Dn Slope=0.005
Boundary for River Rch & Prof#=UNT 152 in Runni,Reach-1,7
Up Type=0
Dn Type=3
Dn Slope=0.005

--- UNT 152 in Running Cr Watershed.g01 (geometry) ---

Geom Title=Existing Conditions

River Reach=UNT 152 in Runni,Reach-1
Reach XY= 30
      2915905.08      7045430.92      2915980.94      7045577.92
      2916021.49      7045673.18      2916087.53      7045744.27
      2916119.43      7045803.76      2916183.62      7045833.87
      2916226.92      7045877.34      2916291.41      7045898.76
      2916364.53      7045904.24      2916395.95      7045935.40
      2916403.26      7045960.30      2916389.62      7045996.41
      2916389.88      7046043.19      2916360.62      7046093.31
      2916318.17      7046141.78      2916277.00      7046226.55
      2916277.22      7046264.90      2916291.75      7046310.67
      2916325.11      7046365.96      2916307.05      7046505.16
      2916321.92      7046529.69      2916371.37      7046549.09
      2916454.97      7046620.89      2916463.25      7046636.59
      2916469.82      7046688.95      2916491.19      7046722.53
      2916501.63      7046762.92      2916529.64      7046798.46
      2916553.15      7046847.00      2916595.59      7046890.71

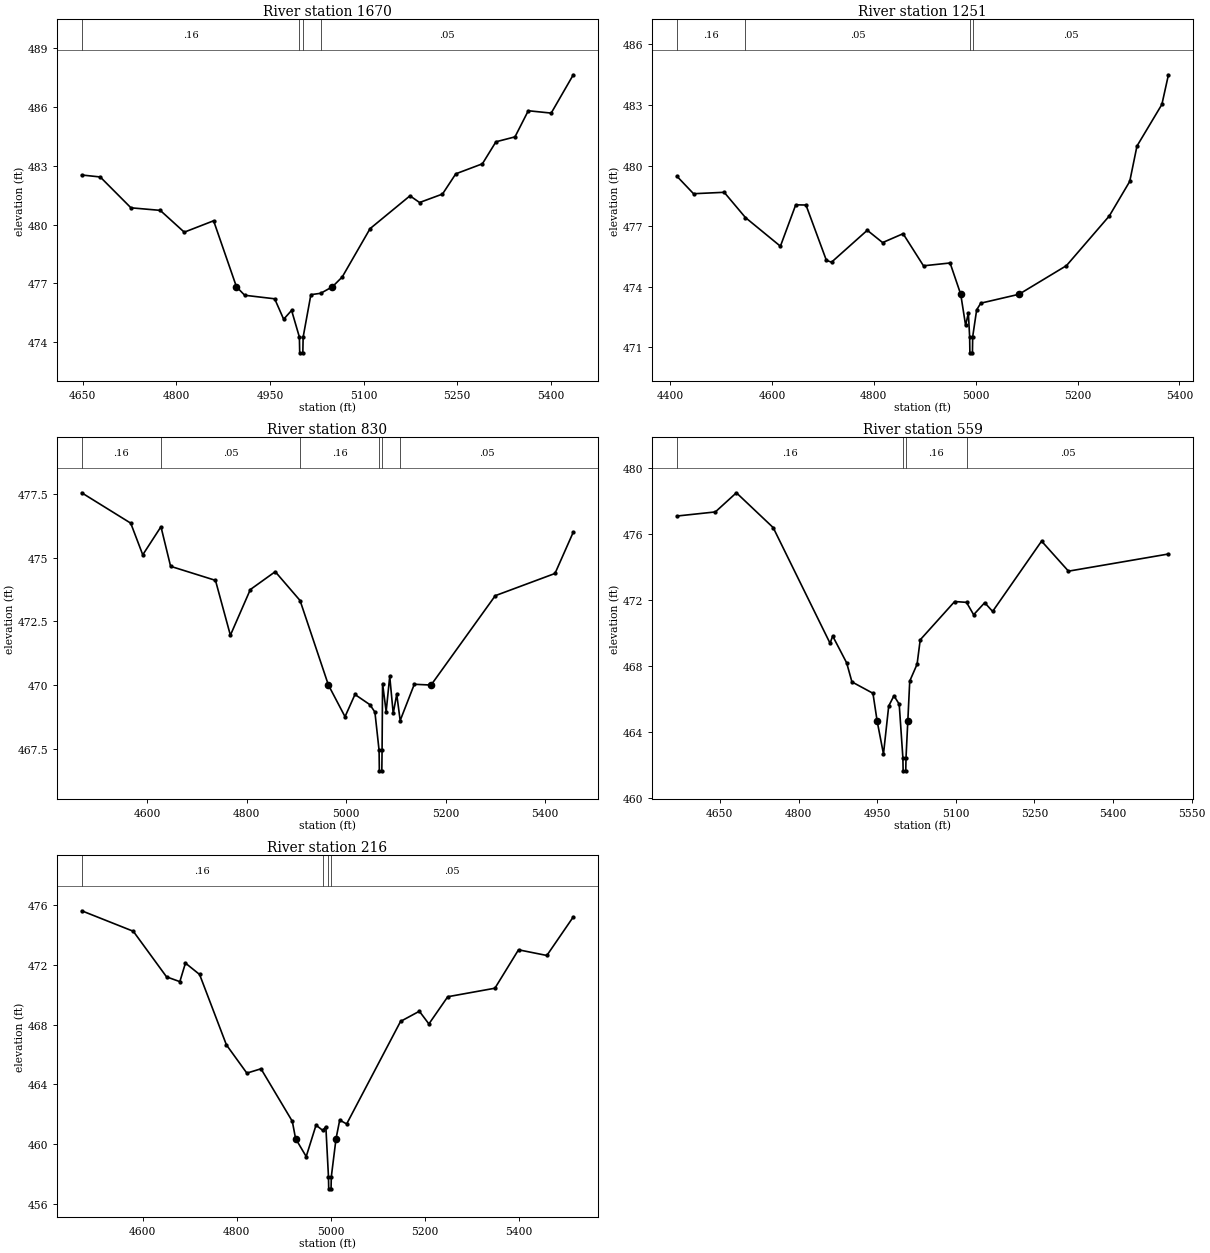
Type RM Length L Ch R = 1,1670,419,419,419
BEGIN DESCRIPTION:
UNT 152 in Running Cr Watershed 3.0
END DESCRIPTION:
XS GIS Cut Line= 3
      2915677.21      7045758.15      2915923.27      7045665.79
      2916370.62      7045391.83
#Sta/Elev= 30
  4648.4  482.52  4678.1  482.42  4727.3  480.85  4774.2  480.72  4812.7  479.61
  4859.7  480.19  4896.3  476.83  4909.5  476.40  4957.5  476.22  4971.9  475.18
  4984.6  475.63  4997.1  474.27  4997.6  473.47  5002.6  473.47  5003.1  474.27
  5015.5  476.43  5031.2  476.50  5049.9  476.83  5065.7  477.33  5110.3  479.79
  5174.2  481.46  5189.6  481.12  5226.3  481.55  5247.6  482.58  5290.2  483.09
  5311.9  484.21  5342.4  484.46  5363.7  485.79  5400.4  485.67  5435.8  487.62
#Mann=4,-1,0
  4648.4    0.16       0  4997.1    0.07       0  5003.1    0.16       0
  5031.2    0.05       0
Bank Sta=4896.3,5049.9
Exp/Cntr=0.3,0.1

Type RM Length L Ch R = 1,1251,421,421,421
BEGIN DESCRIPTION:
Mapping XS 05a37dfb
END DESCRIPTION:
XS GIS Cut Line= 3
      2915732.30      7045988.70      2916267.02      7045943.57
      2916423.26      7045544.27
#Sta/Elev= 30
  4413.1  479.48  4445.9  478.61  4506.1  478.68  4547.8  477.43  4616.5  476.01
  4646.6  478.06  4666.7  478.05  4706.8  475.31  4716.9  475.22  4787.1  476.80
  4817.2  476.19  4857.4  476.63  4897.5  475.04  4949.7  475.18  4970.6  473.63
  4980.2  472.09  4985.6  472.70  4988.1  471.53  4988.6  470.73  4993.6  470.73
  4994.1  471.53  5001.9  472.86  5010.0  473.19  5085.0  473.63  5178.3  475.05
  5262.4  477.51  5302.5  479.22  5316.7  480.97  5365.6  483.03  5378.5  484.50
#Mann=4,-1,0
  4413.1    0.16       0  4547.8    0.05       0  4988.1    0.03       0
  4994.1    0.05       0
Bank Sta=4970.6,5085
Exp/Cntr=0.3,0.1

Type RM Length L Ch R = 1,830,271,271,271
BEGIN DESCRIPTION:
Mapping XS 78411526
END DESCRIPTION:
XS GIS Cut Line= 3
      2915756.57      7046162.31      2916360.77      7046200.51
      2916635.11      7045933.12
#Sta/Elev= 30
  4468.2  477.54  4566.8  476.35  4591.0  475.11  4627.6  476.21  4647.0  474.66
  4737.2  474.11  4767.2  471.96  4807.3  473.75  4857.4  474.45  4907.3  473.32
  4964.3  470.01  4997.7  468.77  5017.7  469.64  5047.8  469.24  5057.8  468.95
  5066.2  467.45  5066.7  466.65  5071.7  466.65  5072.2  467.45  5073.2  470.07
  5080.4  468.97  5087.6  470.35  5094.6  468.90  5101.7  469.65  5108.6  468.62
  5137.0  470.04  5170.7  470.01  5299.8  473.51  5419.9  474.38  5456.7  476.00
#Mann=6,-1,0
  4468.2    0.16       0  4627.6    0.05       0  4907.3    0.16       0
  5066.2    0.07       0  5072.2    0.16       0  5108.6    0.05       0
Bank Sta=4964.3,5170.7
Exp/Cntr=0.3,0.1

Type RM Length L Ch R = 1,559,343,343,343
BEGIN DESCRIPTION:
UNT 152 in Running Cr Watershed 2.0
END DESCRIPTION:
XS GIS Cut Line= 3
      2915881.60      7046478.29      2916365.16      7046448.32
      2916613.78      7046069.27
#Sta/Elev= 30
  4567.9  477.10  4641.4  477.35  4681.5  478.51  4751.7  476.40  4860.2  469.39
  4865.2  469.83  4891.9  468.20  4901.9  467.05  4942.0  466.36  4950.1  464.66
  4962.1  462.68  4972.1  465.59  4982.1  466.21  4992.1  465.70  4999.1  462.46
  4999.6  461.66  5004.6  461.66  5005.1  462.46  5008.5  464.66  5012.2  467.10
  5026.2  468.12  5032.2  469.60  5097.9  471.92  5120.5  471.87  5134.1  471.12
  5155.2  471.85  5170.3  471.32  5263.7  475.58  5315.0  473.76  5505.7  474.80
#Mann=4,-1,0
  4567.9    0.16       0  4999.1    0.07       0  5005.1    0.16       0
  5120.5    0.05       0
Bank Sta=4950.1,5008.5
Exp/Cntr=0.3,0.1

Type RM Length L Ch R = 1,216,0,0,0
BEGIN DESCRIPTION:
UNT 152 in Running Cr Watershed 1.0
END DESCRIPTION:
XS GIS Cut Line= 4
      2915975.38      7046728.29      2916397.31      7046771.72
      2916527.44      7046679.68      2916569.01      7046218.90
#Sta/Elev= 30
  4470.1  475.61  4579.9  474.24  4650.7  471.19  4679.0  470.87  4690.9  472.11
  4721.0  471.35  4778.1  466.64  4821.6  464.75  4851.7  465.04  4918.3  461.53
  4925.3  460.37  4947.9  459.17  4968.8  461.27  4983.1  460.92  4989.7  461.17
  4995.3  457.81  4995.8  457.01  5000.8  457.01  5001.3  457.81  5011.4  460.37
  5019.2  461.61  5034.0  461.35  5148.7  468.21  5188.7  468.89  5209.0  468.04
  5249.1  469.86  5349.5  470.43  5399.7  473.00  5460.0  472.62  5516.3  475.20
#Mann=4,-1,0
  4470.1    0.16       0  4983.1    0.05       0  4995.3    0.03       0
  5001.3    0.05       0
Bank Sta=4925.3,5011.4
Exp/Cntr=0.3,0.1

Chan Stop Cuts=-1