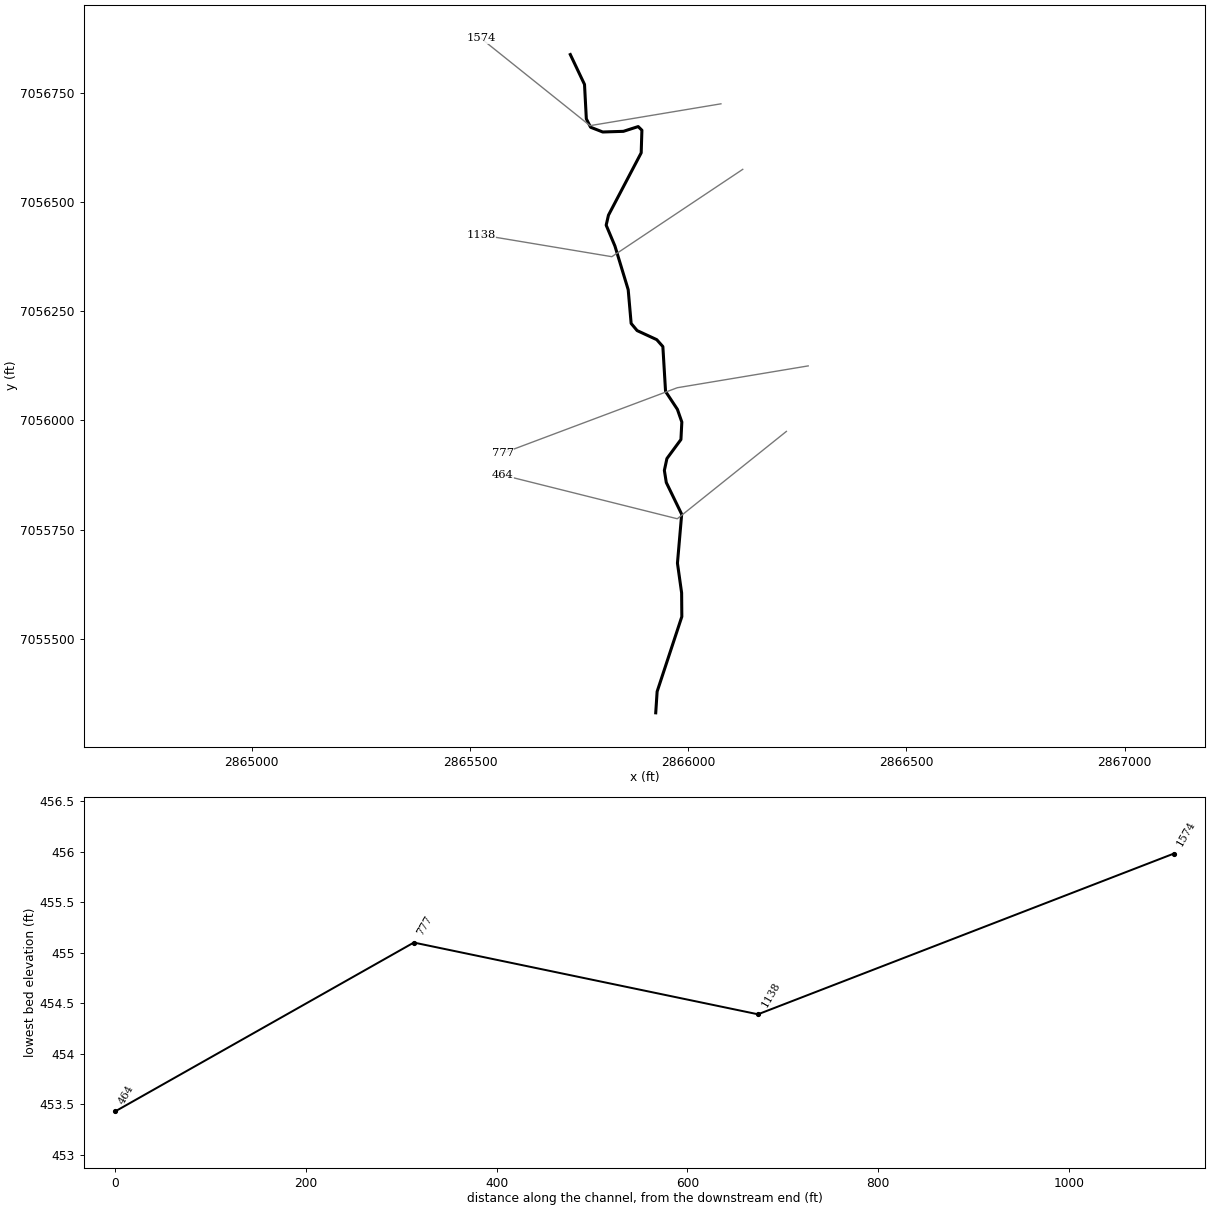
--- UNT 153 in Running Cr Watershed.prj (project) ---

Proj Title=UNT 153 in Running Cr Watershed Base Level Engineering
Current Plan=p01
Default Exp/Contr=0.3,0.1
English Units
Geom File=g01
Flow File=f01
Plan File=p01
BEGIN DESCRIPTION:
UNT 153 in Running Cr Watershed
END DESCRIPTION:

--- UNT 153 in Running Cr Watershed.p01 (plan) ---

Plan Title=Multiple Run
Short Identifier=Multiple
Geom File=g01
Flow File=f01
Subcritical Flow
K Sum by GR= 0
Std Step Tol= 0.01
Critical Tol= 0.01
Num of Std Step Trials= 20
Max Error Tol= 0.3
Flow Tol Ratio= 0.001
Split Flow NTrial= 30
Split Flow Tol= 0.02
Split Flow Ratio= 0.02
Log Output Level= 0
Friction Slope Method= 1
Unsteady Friction Slope Method= 2
Unsteady Bridges Friction Slope Method= 1
Parabolic Critical Depth
Global Vel Dist=  1 , 1 , 1
Global Log Level= 0
CheckData=True
Encroach Param= -1, 0, 0, 0
BEGIN DESCRIPTION:
Multiple Run
END DESCRIPTION:

--- UNT 153 in Running Cr Watershed.f01 (steady flow) ---

Flow Title=Multiple
Number of Profiles=7
Profile Names=10-year,25-year,50-year,1pct_min,100-year,1pct_plu,500-year
River Rch & RM= UNT 153 in Runni,Reach-1,1574
     456     595     704     415     827    1650    1139
Boundary for River Rch & Prof#=UNT 153 in Runni,Reach-1,1
Up Type=0
Dn Type=3
Dn Slope=0.005
Boundary for River Rch & Prof#=UNT 153 in Runni,Reach-1,2
Up Type=0
Dn Type=3
Dn Slope=0.005
Boundary for River Rch & Prof#=UNT 153 in Runni,Reach-1,3
Up Type=0
Dn Type=3
Dn Slope=0.005
Boundary for River Rch & Prof#=UNT 153 in Runni,Reach-1,4
Up Type=0
Dn Type=3
Dn Slope=0.005
Boundary for River Rch & Prof#=UNT 153 in Runni,Reach-1,5
Up Type=0
Dn Type=3
Dn Slope=0.005
Boundary for River Rch & Prof#=UNT 153 in Runni,Reach-1,6
Up Type=0
Dn Type=3
Dn Slope=0.005
Boundary for River Rch & Prof#=UNT 153 in Runni,Reach-1,7
Up Type=0
Dn Type=3
Dn Slope=0.005

--- UNT 153 in Running Cr Watershed.g01 (geometry) ---

Geom Title=Existing Conditions

River Reach=UNT 153 in Runni,Reach-1
Reach XY= 30
      2865729.87      7056837.83      2865762.41      7056769.36
      2865766.57      7056690.68      2865776.37      7056671.36
      2865804.18      7056660.50      2865851.46      7056661.99
      2865885.41      7056672.91      2865893.91      7056664.50
      2865892.28      7056612.74      2865817.28      7056470.00
      2865812.04      7056447.13      2865832.10      7056399.45
      2865862.51      7056299.41      2865869.27      7056222.16
      2865882.98      7056205.80      2865927.97      7056185.03
      2865941.94      7056169.22      2865948.12      7056066.53
      2865975.28      7056025.45      2865985.41      7055996.46
      2865983.35      7055956.46      2865951.25      7055912.89
      2865945.39      7055885.73      2865949.79      7055858.02
      2865985.06      7055785.39      2865975.36      7055673.35
      2865984.93      7055605.32      2865985.39      7055550.87
      2865928.80      7055379.38      2865925.59      7055330.71

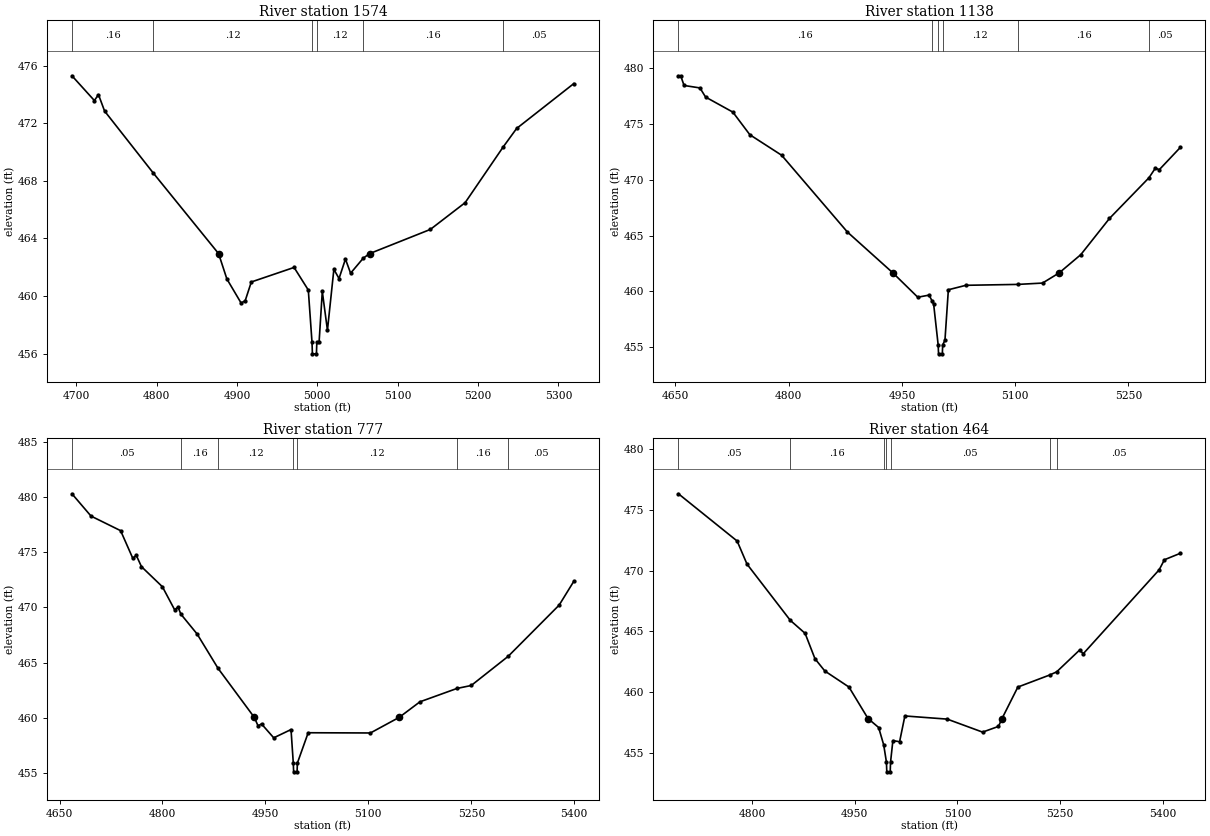
Type RM Length L Ch R = 1,1574,436,436,436
BEGIN DESCRIPTION:
UNT 153 in Running Cr Watershed 4.0
END DESCRIPTION:
XS GIS Cut Line= 3
      2866075.03      7056725.01      2865775.00      7056675.00
      2865525.02      7056874.98
#Sta/Elev= 30
  4694.8  475.29  4722.7  473.57  4727.8  473.98  4735.4  472.84  4795.9  468.54
  4877.2  462.94  4887.5  461.18  4905.2  459.51  4910.3  459.67  4917.9  460.97
  4971.1  461.98  4988.8  460.41  4993.4  456.78  4993.9  455.98  4998.9  455.98
  4999.4  456.78  5002.2  456.78  5006.2  460.31  5012.6  457.62  5020.6  461.85
  5027.0  461.21  5035.0  462.56  5041.4  461.58  5057.1  462.62  5065.0  462.94
  5140.6  464.62  5183.9  466.48  5231.1  470.34  5247.9  471.63  5319.1  474.75
#Mann=6,-1,0
  4694.8    0.16       0  4795.9    0.12       0  4993.4    0.07       0
  4999.4    0.12       0  5057.1    0.16       0  5231.1    0.05       0
Bank Sta=4877.2,5065
Exp/Cntr=0.3,0.1

Type RM Length L Ch R = 1,1138,361,361,361
BEGIN DESCRIPTION:
UNT 153 in Running Cr Watershed 3.0
END DESCRIPTION:
XS GIS Cut Line= 3
      2866124.97      7056574.98      2865825.00      7056375.00
      2865524.96      7056425.01
#Sta/Elev= 30
  4654.0  479.34  4657.0  479.34  4661.5  478.47  4682.5  478.25  4690.0  477.43
  4726.1  476.08  4748.6  474.05  4790.7  472.21  4877.8  465.32  4938.1  461.65
  4971.0  459.47  4986.0  459.66  4990.2  459.10  4992.0  458.86  4998.0  455.19
  4998.5  454.39  5003.5  454.39  5004.0  455.19  5007.0  455.62  5011.5  460.14
  5034.8  460.54  5103.6  460.62  5136.2  460.74  5158.2  461.65  5186.9  463.29
  5224.9  466.54  5277.2  470.19  5285.7  471.06  5290.8  470.91  5318.7  472.91
#Mann=6,-1,0
  4654.0    0.16       0  4990.2    0.12       0  4998.0    0.07       0
  5004.0    0.12       0  5103.6    0.16       0  5277.2    0.05       0
Bank Sta=4938.1,5158.2
Exp/Cntr=0.3,0.1

Type RM Length L Ch R = 1,777,313,313,313
BEGIN DESCRIPTION:
UNT 153 in Running Cr Watershed 2.0
END DESCRIPTION:
XS GIS Cut Line= 3
      2866274.96      7056124.99      2865975.00      7056075.00
      2865575.00      7055925.00
#Sta/Elev= 30
  4668.1  480.28  4695.9  478.26  4739.0  476.94  4756.8  474.43  4761.8  474.71
  4769.4  473.68  4799.9  471.86  4817.6  469.79  4822.7  470.01  4826.8  469.38
  4850.5  467.58  4881.0  464.47  4933.7  460.04  4939.3  459.26  4944.3  459.44
  4962.1  458.18  4987.3  458.93  4990.6  455.90  4991.1  455.10  4996.1  455.10
  4996.6  455.90  5012.3  458.64  5103.0  458.62  5145.1  460.04  5175.1  461.44
  5229.0  462.65  5249.9  462.92  5303.7  465.56  5378.0  470.20  5399.4  472.36
#Mann=7,-1,0
  4668.1    0.05       0  4826.8    0.16       0  4881.0    0.12       0
  4990.6    0.07       0  4996.6    0.12       0  5229.0    0.16       0
  5303.7    0.05       0
Bank Sta=4933.7,5145.1
Exp/Cntr=0.3,0.1

Type RM Length L Ch R = 1,464,0,0,0
BEGIN DESCRIPTION:
UNT 153 in Running Cr Watershed 1.0
END DESCRIPTION:
XS GIS Cut Line= 3
      2866225.02      7055975.02      2865975.00      7055775.00
      2865574.99      7055875.00
#Sta/Elev= 30
  4692.7  476.32  4778.4  472.43  4792.8  470.53  4856.0  465.90  4877.6  464.83
  4892.0  462.74  4906.4  461.73  4941.6  460.41  4969.4  457.82  4984.9  457.08
  4992.3  455.65  4996.3  454.23  4996.8  453.43  5001.8  453.43  5002.3  454.23
  5005.7  456.00  5015.5  455.91  5023.2  458.03  5085.0  457.77  5136.6  456.70
  5159.8  457.17  5165.0  457.82  5188.1  460.41  5234.5  461.40  5244.7  461.66
  5278.3  463.46  5283.5  463.15  5394.3  470.06  5402.0  470.89  5425.2  471.42
#Mann=7,-1,0
  4692.7    0.05       0  4856.0    0.16       0  4992.3    0.05       0
  4996.3    0.03       0  5002.3    0.05       0  5234.5    0.12       0
  5244.7    0.05       0
Bank Sta=4969.4,5165
Exp/Cntr=0.3,0.1

Chan Stop Cuts=-1