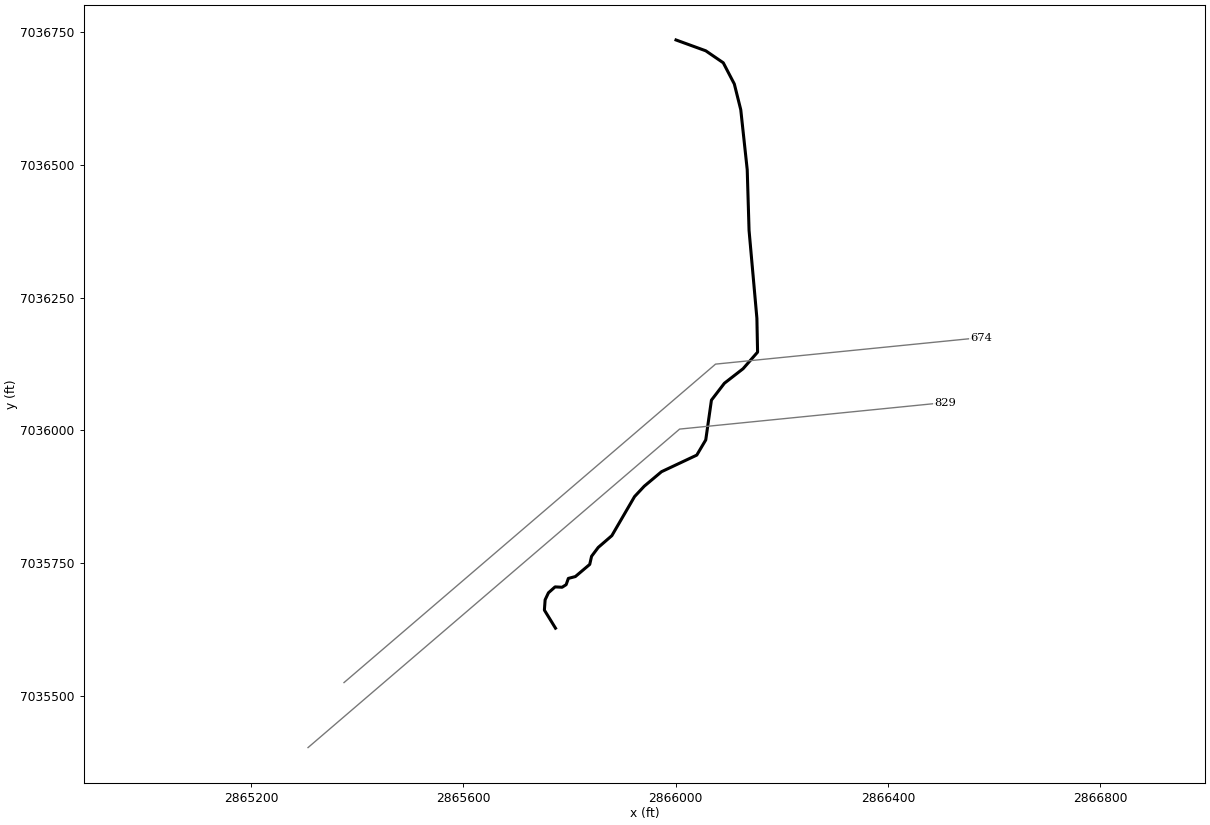
--- UNT 154 in Running Cr Watershed.prj (project) ---

Proj Title=UNT 154 in Running Cr Watershed Base Level Engineering
Current Plan=p01
Default Exp/Contr=0.3,0.1
English Units
Geom File=g01
Flow File=f01
Plan File=p01
BEGIN DESCRIPTION:
UNT 154 in Running Cr Watershed
END DESCRIPTION:

--- UNT 154 in Running Cr Watershed.p01 (plan) ---

Plan Title=Multiple Run
Short Identifier=Multiple
Geom File=g01
Flow File=f01
Subcritical Flow
K Sum by GR= 0
Std Step Tol= 0.01
Critical Tol= 0.01
Num of Std Step Trials= 20
Max Error Tol= 0.3
Flow Tol Ratio= 0.001
Split Flow NTrial= 30
Split Flow Tol= 0.02
Split Flow Ratio= 0.02
Log Output Level= 0
Friction Slope Method= 1
Unsteady Friction Slope Method= 2
Unsteady Bridges Friction Slope Method= 1
Parabolic Critical Depth
Global Vel Dist=  1 , 1 , 1
Global Log Level= 0
CheckData=True
Encroach Param= -1, 0, 0, 0
BEGIN DESCRIPTION:
Multiple Run
END DESCRIPTION:

--- UNT 154 in Running Cr Watershed.f01 (steady flow) ---

Flow Title=Multiple
Number of Profiles=7
Profile Names=10-year,25-year,50-year,1pct_min,100-year,1pct_plu,500-year
River Rch & RM= UNT 154 in Runni,Reach-1,829
      84      98     107      59     118     235     141
Boundary for River Rch & Prof#=UNT 154 in Runni,Reach-1,1
Up Type=0
Dn Type=3
Dn Slope=0.005
Boundary for River Rch & Prof#=UNT 154 in Runni,Reach-1,2
Up Type=0
Dn Type=3
Dn Slope=0.005
Boundary for River Rch & Prof#=UNT 154 in Runni,Reach-1,3
Up Type=0
Dn Type=3
Dn Slope=0.005
Boundary for River Rch & Prof#=UNT 154 in Runni,Reach-1,4
Up Type=0
Dn Type=3
Dn Slope=0.005
Boundary for River Rch & Prof#=UNT 154 in Runni,Reach-1,5
Up Type=0
Dn Type=3
Dn Slope=0.005
Boundary for River Rch & Prof#=UNT 154 in Runni,Reach-1,6
Up Type=0
Dn Type=3
Dn Slope=0.005
Boundary for River Rch & Prof#=UNT 154 in Runni,Reach-1,7
Up Type=0
Dn Type=3
Dn Slope=0.005

--- UNT 154 in Running Cr Watershed.g01 (geometry) ---

Geom Title=Existing Conditions

River Reach=UNT 154 in Runni,Reach-1
Reach XY= 30
      2865773.49      7035627.54      2865752.56      7035661.57
      2865753.95      7035681.01      2865760.20      7035694.21
      2865772.70      7035705.32      2865785.90      7035704.62
      2865793.54      7035709.48      2865797.70      7035721.29
      2865810.90      7035724.76      2865837.98      7035747.68
      2865841.45      7035762.96      2865853.95      7035779.62
      2865879.65      7035801.84      2865922.44      7035875.46
      2865940.67      7035894.99      2865973.22      7035922.33
      2866039.63      7035953.58      2866056.56      7035982.23
      2866067.27      7036057.15      2866091.71      7036089.00
      2866126.87      7036116.34      2866154.21      7036147.59
      2866152.91      7036211.39      2866138.16      7036376.76
      2866134.68      7036491.34      2866122.53      7036604.19
      2866110.38      7036652.80      2866089.54      7036692.73
      2866056.56      7036715.30      2866000.51      7036735.71

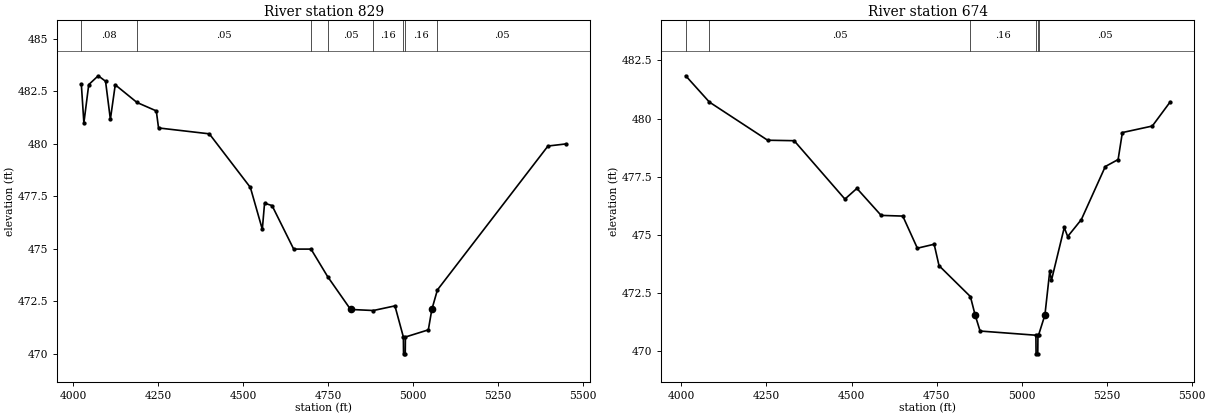
Type RM Length L Ch R = 1,829,155,155,155
BEGIN DESCRIPTION:
UNT 154 in Running Cr Watershed 2.0
END DESCRIPTION:
XS GIS Cut Line= 3
      2865307.26      7035402.58      2866007.29      7036002.60
      2866507.30      7036052.61
#Sta/Elev= 30
  4024.8  482.83  4032.3  480.99  4046.6  482.81  4074.5  483.23  4096.0  482.97
  4110.2  481.16  4124.5  482.80  4188.5  481.96  4245.2  481.56  4251.8  480.75
  4401.1  480.47  4521.8  477.92  4556.9  475.93  4563.5  477.17  4585.5  477.06
  4649.1  474.99  4700.1  474.99  4749.0  473.68  4816.4  472.12  4883.3  472.07
  4946.8  472.29  4971.6  470.81  4972.1  470.01  4977.1  470.01  4977.6  470.81
  5045.0  471.15  5055.3  472.12  5071.7  473.05  5396.7  479.89  5449.3  479.99
#Mann=8,-1,0
  4024.8    0.08       0  4188.5    0.05       0  4700.1    0.16       0
  4749.0    0.05       0  4883.3    0.16       0  4971.6    0.07       0
  4977.6    0.16       0  5071.7    0.05       0
Bank Sta=4816.4,5055.3
Exp/Cntr=0.3,0.1

Type RM Length L Ch R = 1,674,0,0,0
BEGIN DESCRIPTION:
UNT 154 in Running Cr Watershed 1.0
END DESCRIPTION:
XS GIS Cut Line= 3
      2865375.02      7035525.02      2866075.00      7036125.00
      2866574.98      7036175.00
#Sta/Elev= 30
  4012.6  481.84  4082.2  480.71  4253.5  479.07  4331.4  479.05  4480.7  476.54
  4515.8  477.00  4587.1  475.84  4650.8  475.81  4693.6  474.43  4743.0  474.60
  4757.3  473.68  4849.6  472.35  4863.4  471.56  4878.0  470.87  5042.1  470.69
  5042.6  469.89  5047.6  469.89  5048.1  470.69  5049.8  470.69  5068.6  471.56
  5082.8  473.44  5087.8  473.05  5125.5  475.32  5135.5  474.93  5175.7  475.66
  5246.1  477.94  5283.8  478.24  5296.3  479.40  5384.3  479.68  5437.0  480.72
#Mann=6,-1,0
  4012.6    0.08       0  4082.2    0.05       0  4849.6    0.16       0
  5042.1    0.07       0  5048.1    0.16       0  5049.8    0.05       0
Bank Sta=4863.4,5068.6
Exp/Cntr=0.3,0.1

Chan Stop Cuts=-1