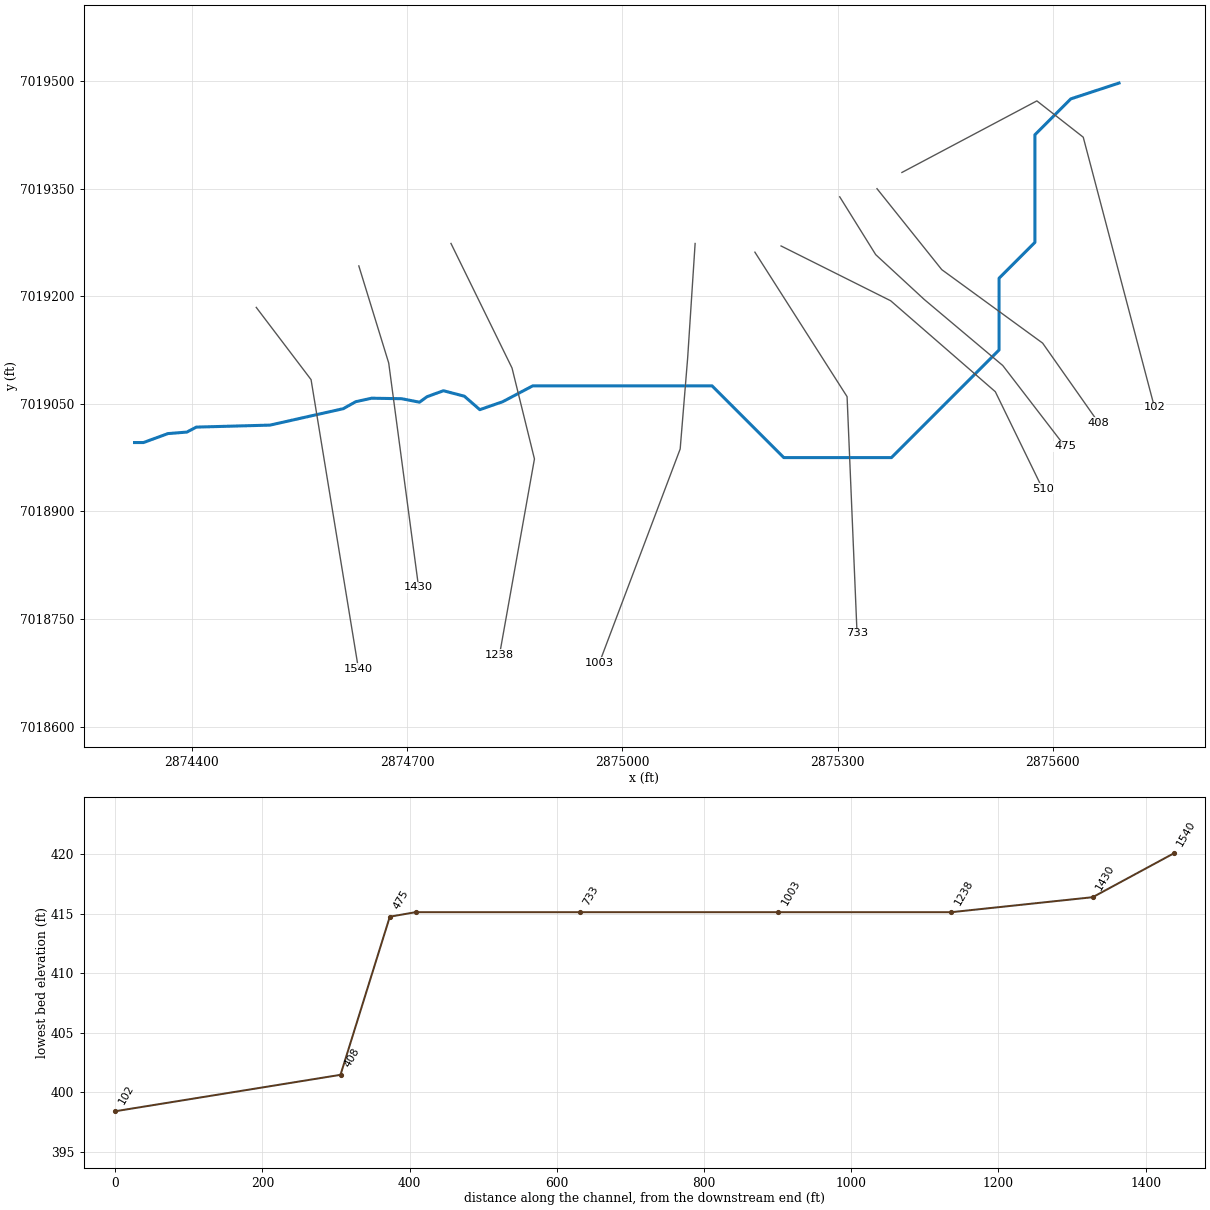
--- UNT 155 in Running Cr Watershed.prj (project) ---

Proj Title=UNT 155 in Running Cr Watershed Base Level Engineering
Current Plan=p01
Default Exp/Contr=0.3,0.1
English Units
Geom File=g01
Flow File=f01
Plan File=p01
BEGIN DESCRIPTION:
UNT 155 in Running Cr Watershed
END DESCRIPTION:

--- UNT 155 in Running Cr Watershed.p01 (plan) ---

Plan Title=Multiple Run
Short Identifier=Multiple
Geom File=g01
Flow File=f01
Subcritical Flow
K Sum by GR= 0
Std Step Tol= 0.01
Critical Tol= 0.01
Num of Std Step Trials= 20
Max Error Tol= 0.3
Flow Tol Ratio= 0.001
Split Flow NTrial= 30
Split Flow Tol= 0.02
Split Flow Ratio= 0.02
Log Output Level= 0
Friction Slope Method= 1
Unsteady Friction Slope Method= 2
Unsteady Bridges Friction Slope Method= 1
Parabolic Critical Depth
Global Vel Dist=  1 , 1 , 1
Global Log Level= 0
CheckData=True
Encroach Param= -1, 0, 0, 0
BEGIN DESCRIPTION:
Multiple Run
END DESCRIPTION:

--- UNT 155 in Running Cr Watershed.f01 (steady flow) ---

Flow Title=Multiple
Number of Profiles=7
Profile Names=10-year,25-year,50-year,1pct_min,100-year,1pct_plu,500-year
River Rch & RM= UNT 155 in Runni,Reach-1,1540
      73      85      93      51     102     203     122
Boundary for River Rch & Prof#=UNT 155 in Runni,Reach-1,1
Up Type=0
Dn Type=3
Dn Slope=0.005
Boundary for River Rch & Prof#=UNT 155 in Runni,Reach-1,2
Up Type=0
Dn Type=3
Dn Slope=0.005
Boundary for River Rch & Prof#=UNT 155 in Runni,Reach-1,3
Up Type=0
Dn Type=3
Dn Slope=0.005
Boundary for River Rch & Prof#=UNT 155 in Runni,Reach-1,4
Up Type=0
Dn Type=3
Dn Slope=0.005
Boundary for River Rch & Prof#=UNT 155 in Runni,Reach-1,5
Up Type=0
Dn Type=3
Dn Slope=0.005
Boundary for River Rch & Prof#=UNT 155 in Runni,Reach-1,6
Up Type=0
Dn Type=3
Dn Slope=0.005
Boundary for River Rch & Prof#=UNT 155 in Runni,Reach-1,7
Up Type=0
Dn Type=3
Dn Slope=0.005

--- UNT 155 in Running Cr Watershed.g01 (geometry) ---

Geom Title=Existing Conditions

River Reach=UNT 155 in Runni,Reach-1
Reach XY= 26
      2874320.02      7018995.98      2874332.52      7018995.98
      2874366.55      7019008.48      2874392.94      7019010.57
      2874406.13      7019017.51      2874508.91      7019020.29
      2874610.99      7019043.21      2874628.35      7019052.93
      2874650.58      7019057.79      2874692.24      7019057.09
      2874717.24      7019052.23      2874727.66      7019059.87
      2874750.58      7019068.21      2874779.74      7019060.57
      2874801.27      7019041.82      2874833.22      7019052.93
      2874875.00      7019075.00      2875125.00      7019075.00
      2875225.00      7018975.00      2875375.00      7018975.00
      2875525.00      7019125.00      2875525.00      7019225.00
      2875575.00      7019275.00      2875575.00      7019425.00
      2875625.00      7019475.00      2875692.20      7019497.06

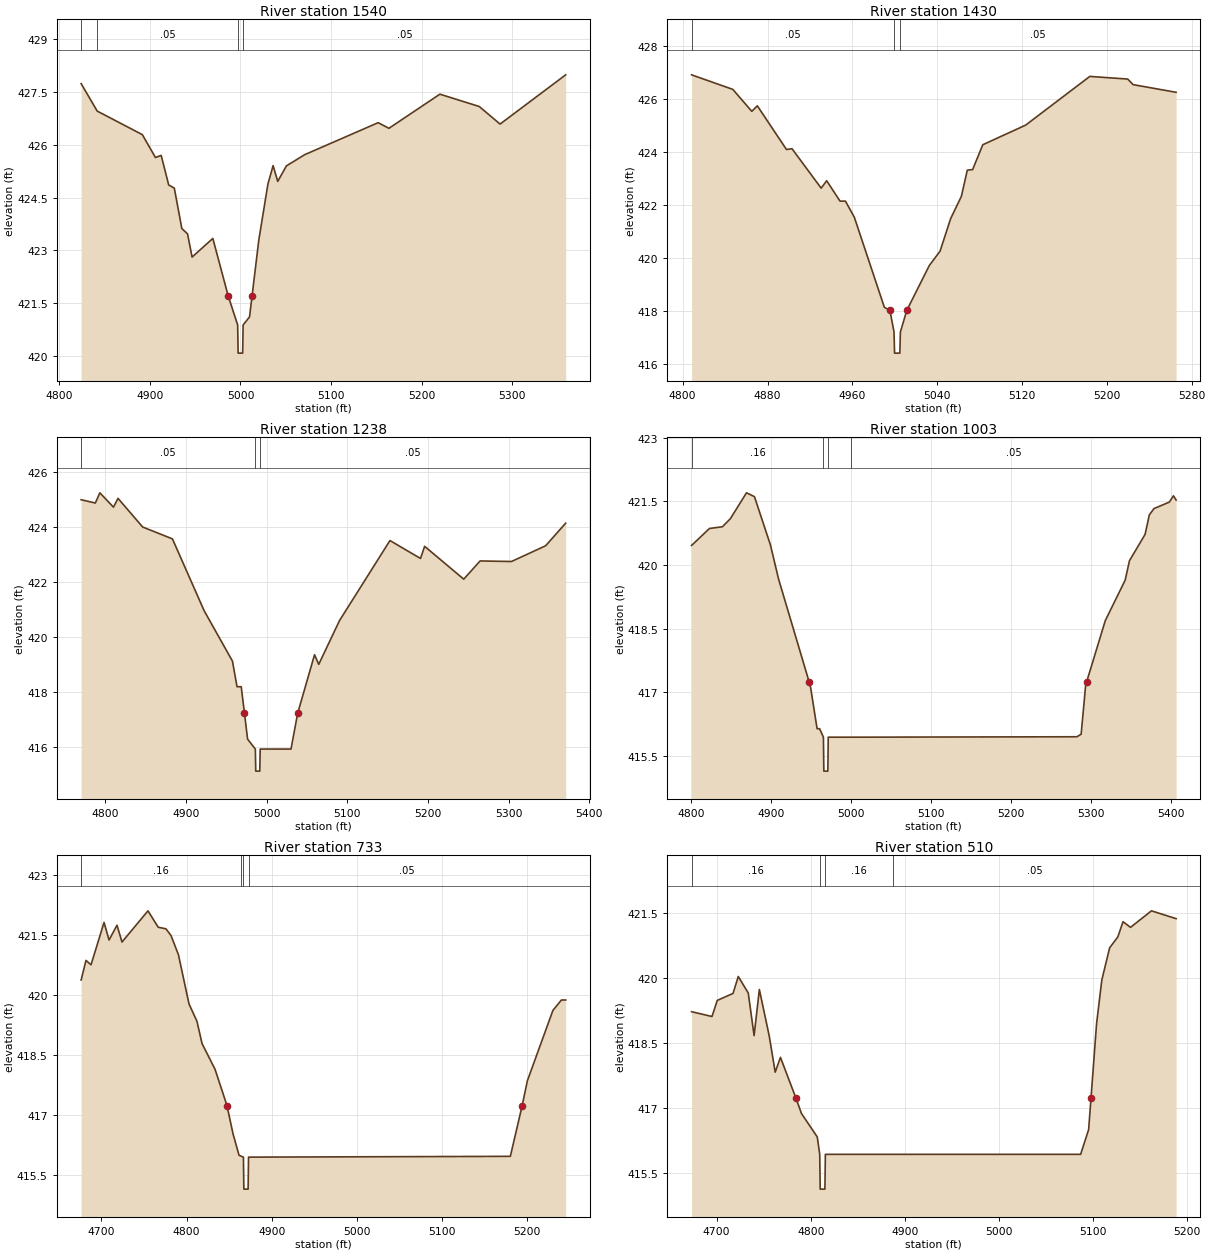
Type RM Length L Ch R = 1,1540,110,110,110
BEGIN DESCRIPTION:
UNT 155 in Running Cr Watershed 2.0
END DESCRIPTION:
XS GIS Cut Line= 3
      2874489.68      7019184.36      2874566.08      7019083.65
      2874632.06      7018680.83
#Sta/Elev= 30
  4824.2  427.74  4841.9  426.96  4891.7  426.29  4906.2  425.64  4912.5  425.70
  4920.8  424.86  4927.0  424.77  4935.3  423.62  4941.6  423.47  4946.6  422.81
  4969.5  423.34  4986.4  421.71  4996.9  420.88  4997.4  420.08  5002.4  420.08
  5002.9  420.88  5010.0  421.11  5012.8  421.71  5020.2  423.29  5030.3  424.89
  5036.0  425.41  5041.1  424.96  5050.6  425.40  5070.8  425.72  5151.9  426.63
  5163.8  426.47  5220.0  427.44  5263.4  427.09  5286.4  426.59  5358.8  427.99
#Mann=4,-1,0
  4824.2    0.08       0  4841.9    0.05       0  4996.9    0.03       0
  5002.9    0.05       0
Bank Sta=4986.4,5012.8
Exp/Cntr=0.3,0.1

Type RM Length L Ch R = 1,1430,192,192,192
BEGIN DESCRIPTION:
Mapping XS 7587b930
END DESCRIPTION:
XS GIS Cut Line= 3
      2874632.64      7019242.18      2874674.30      7019106.80
      2874715.97      7018794.31
#Sta/Elev= 30
  4808.4  426.91  4847.3  426.36  4865.2  425.53  4870.4  425.74  4897.9  424.09
  4903.1  424.12  4930.6  422.63  4935.8  422.91  4948.4  422.14  4953.5  422.14
  4961.9  421.53  4990.2  418.13  4995.4  418.02  4999.3  417.20  4999.8  416.40
  5004.8  416.40  5005.3  417.20  5011.4  418.02  5032.6  419.71  5042.7  420.25
  5052.7  421.48  5062.8  422.32  5068.4  423.31  5073.4  423.33  5083.0  424.27
  5123.4  425.01  5183.9  426.85  5219.7  426.75  5224.7  426.54  5265.3  426.25
#Mann=3,-1,0
  4808.4    0.05       0  4999.3    0.03       0  5005.3    0.05       0
Bank Sta=4995.4,5011.4
Exp/Cntr=0.3,0.1

Type RM Length L Ch R = 1,1238,235,235,235
BEGIN DESCRIPTION:
Mapping XS 85f841e4
END DESCRIPTION:
XS GIS Cut Line= 4
      2874761.09      7019273.50      2874846.18      7019099.86
      2874877.43      7018973.12      2874828.81      7018700.53
#Sta/Elev= 30
  4770.1  424.98  4787.7  424.86  4793.3  425.23  4810.2  424.71  4815.8  425.03
  4846.4  423.99  4883.3  423.56  4922.7  420.95  4957.7  419.13  4963.4  418.20
  4968.6  418.20  4972.6  417.24  4976.5  416.30  4986.1  415.94  4986.6  415.14
  4991.6  415.14  4992.1  415.94  5030.3  415.94  5038.6  417.24  5059.5  419.36
  5064.7  419.01  5090.5  420.60  5153.0  423.50  5190.9  422.85  5196.0  423.29
  5244.5  422.10  5264.8  422.76  5303.7  422.74  5346.0  423.31  5370.9  424.13
#Mann=3,-1,0
  4770.1    0.05       0  4986.1    0.03       0  4992.1    0.05       0
Bank Sta=4972.6,5038.6
Exp/Cntr=0.3,0.1

Type RM Length L Ch R = 1,1003,270,270,270
BEGIN DESCRIPTION:
Mapping XS 767fb96f
END DESCRIPTION:
XS GIS Cut Line= 4
      2875101.38      7019273.43      2875090.97      7019113.74
      2875080.55      7018987.01      2874967.99      7018689.16
#Sta/Elev= 30
  4801.1  420.46  4823.5  420.86  4839.6  420.90  4849.6  421.09  4869.7  421.70
  4879.7  421.61  4899.7  420.47  4909.8  419.67  4948.1  417.24  4949.8  417.12
  4958.0  416.14  4961.1  416.14  4965.9  415.94  4966.4  415.14  4971.4  415.14
  4971.9  415.94  5000.8  415.94  5282.7  415.95  5288.0  416.01  5293.6  417.16
  5294.8  417.24  5318.2  418.69  5343.0  419.64  5348.4  420.10  5367.9  420.72
  5373.2  421.18  5379.1  421.33  5398.1  421.48  5403.4  421.63  5406.7  421.53
#Mann=4,-1,0
  4801.1    0.16       0  4965.9    0.07       0  4971.9    0.16       0
  5000.8    0.05       0
Bank Sta=4948.1,5294.8
Exp/Cntr=0.3,0.1

Type RM Length L Ch R = 1,733,223,223,223
BEGIN DESCRIPTION:
Mapping XS e2768c30
END DESCRIPTION:
XS GIS Cut Line= 3
      2875184.71      7019261.33      2875313.19      7019059.93
      2875327.08      7018730.02
#Sta/Elev= 30
  4676.1  420.37  4681.8  420.86  4687.7  420.75  4703.0  421.81  4708.9  421.37
  4718.2  421.74  4724.1  421.32  4754.6  422.10  4766.6  421.69  4775.7  421.65
  4781.7  421.48  4790.4  421.00  4802.8  419.77  4812.1  419.34  4818.1  418.78
  4833.3  418.14  4847.4  417.23  4854.4  416.53  4861.5  415.99  4863.3  415.97
  4866.7  415.94  4867.2  415.14  4872.2  415.14  4872.7  415.94  5180.2  415.96
  5194.1  417.23  5200.2  417.85  5230.2  419.61  5240.2  419.87  5245.2  419.87
#Mann=4,-1,0
  4676.1    0.16       0  4863.3    0.05       0  4866.7   0.033       0
  4872.7    0.05       0
Bank Sta=4847.4,5194.1
Exp/Cntr=0.3,0.1

Type RM Length L Ch R = 1,510,35,35,35
BEGIN DESCRIPTION:
Mapping XS c98da4fa
END DESCRIPTION:
XS GIS Cut Line= 4
      2875221.18      7019269.99      2875373.95      7019193.61
      2875519.79      7019066.87      2875585.74      7018931.49
#Sta/Elev= 30
  4673.5  419.22  4695.2  419.11  4700.8  419.48  4717.5  419.64  4723.1  420.03
  4733.7  419.65  4739.9  418.67  4745.5  419.73  4756.0  418.66  4762.3  417.83
  4767.9  418.17  4784.4  417.23  4790.2  416.88  4807.0  416.34  4809.6  415.94
  4810.1  415.14  4815.1  415.14  4815.6  415.94  4887.5  415.94  5086.7  415.94
  5095.2  416.51  5097.7  417.23  5103.6  418.94  5109.2  419.95  5117.5  420.69
  5126.2  420.94  5131.7  421.29  5139.7  421.16  5161.9  421.54  5188.1  421.36
#Mann=4,-1,0
  4673.5    0.16       0  4809.6   0.033       0  4815.6    0.16       0
  4887.5    0.05       0
Bank Sta=4784.4,5097.7
Exp/Cntr=0.3,0.1

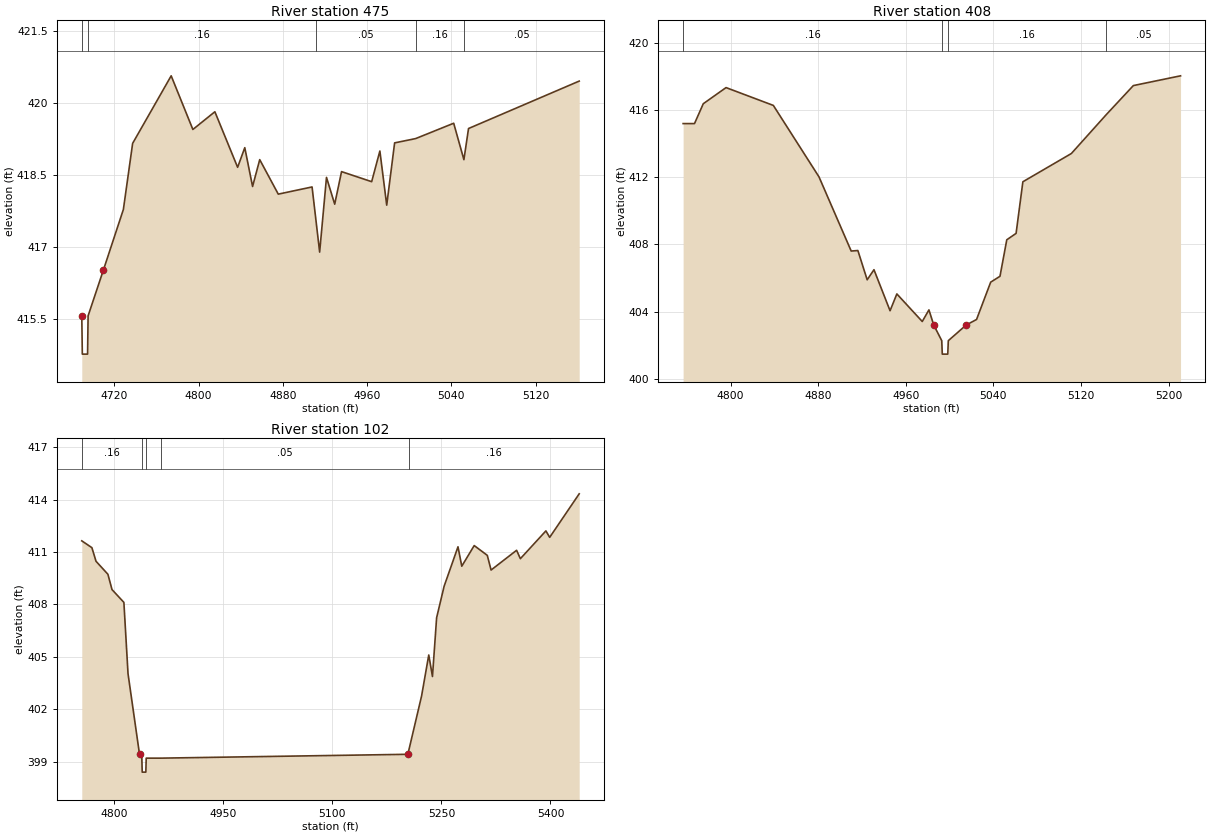
Type RM Length L Ch R = 1,475,67,67,67
BEGIN DESCRIPTION:
Mapping XS 11913b7f
END DESCRIPTION:
XS GIS Cut Line= 5
      2875302.93      7019338.50      2875353.12      7019257.84
      2875420.83      7019195.34      2875530.20      7019103.33
      2875616.98      7018990.52
#Sta/Elev= 30
  4689.0  415.56  4689.5  414.76  4694.5  414.76  4695.0  415.56  4709.6  416.52
  4728.5  417.78  4737.3  419.16  4773.9  420.57  4794.5  419.45  4815.4  419.82
  4837.0  418.66  4843.8  419.07  4851.2  418.26  4858.0  418.82  4875.6  418.10
  4907.7  418.25  4911.2  417.59  4914.9  416.89  4921.4  418.45  4929.2  417.89
  4935.7  418.57  4964.3  418.36  4972.1  419.00  4978.6  417.87  4986.1  419.17
  5006.1  419.26  5042.2  419.58  5051.9  418.82  5056.3  419.47  5161.4  420.46
#Mann=5,-1,0
  4689.0   0.033       0  4695.0    0.16       0  4911.2    0.05       0
  5006.1    0.16       0  5051.9    0.05       0
Bank Sta=4689,4709.6
Exp/Cntr=0.3,0.1

Type RM Length L Ch R = 1,408,306,306,306
BEGIN DESCRIPTION:
Mapping XS 580c7335
END DESCRIPTION:
XS GIS Cut Line= 4
      2875354.87      7019349.84      2875445.13      7019237.01
      2875585.76      7019134.58      2875663.89      7019023.46
#Sta/Elev= 30
  4756.7  415.18  4767.1  415.18  4775.1  416.36  4795.9  417.32  4839.1  416.26
  4880.8  412.01  4910.2  407.60  4916.3  407.63  4924.8  405.89  4931.0  406.49
  4945.7  404.05  4951.9  405.05  4975.1  403.41  4981.2  404.10  4985.6  403.20
  4992.9  402.27  4993.4  401.47  4998.4  401.47  4998.9  402.27  5015.2  403.20
  5024.7  403.53  5037.6  405.75  5046.1  406.10  5052.3  408.27  5060.8  408.65
  5067.0  411.72  5111.3  413.40  5143.0  415.70  5167.9  417.44  5211.0  418.02
#Mann=4,-1,0
  4756.7    0.16       0  4992.9    0.07       0  4998.9    0.16       0
  5143.0    0.05       0
Bank Sta=4985.6,5015.2
Exp/Cntr=0.3,0.1

Type RM Length L Ch R = 1,102,0,0,0
BEGIN DESCRIPTION:
UNT 155 in Running Cr Watershed 1.0
END DESCRIPTION:
XS GIS Cut Line= 4
      2875389.61      7019372.44      2875577.71      7019472.20
      2875642.36      7019421.60      2875741.57      7019045.37
#Sta/Elev= 30
  4755.4  411.64  4769.3  411.25  4775.0  410.47  4791.3  409.73  4797.0  408.85
  4813.3  408.12  4819.0  404.04  4834.8  399.43  4838.0  399.21  4838.5  398.41
  4843.5  398.41  4844.0  399.21  4864.2  399.21  5203.8  399.43  5205.9  399.79
  5222.7  402.76  5232.6  405.11  5237.7  403.88  5243.4  407.24  5253.7  409.04
  5272.8  411.30  5278.0  410.19  5295.1  411.37  5313.1  410.81  5318.3  409.97
  5353.4  411.10  5358.6  410.62  5393.7  412.21  5398.9  411.84  5439.5  414.33
#Mann=5,-1,0
  4755.4    0.16       0  4838.0   0.033       0  4844.0    0.16       0
  4864.2    0.05       0  5205.9    0.16       0
Bank Sta=4834.8,5203.8
Exp/Cntr=0.3,0.1

Chan Stop Cuts=-1