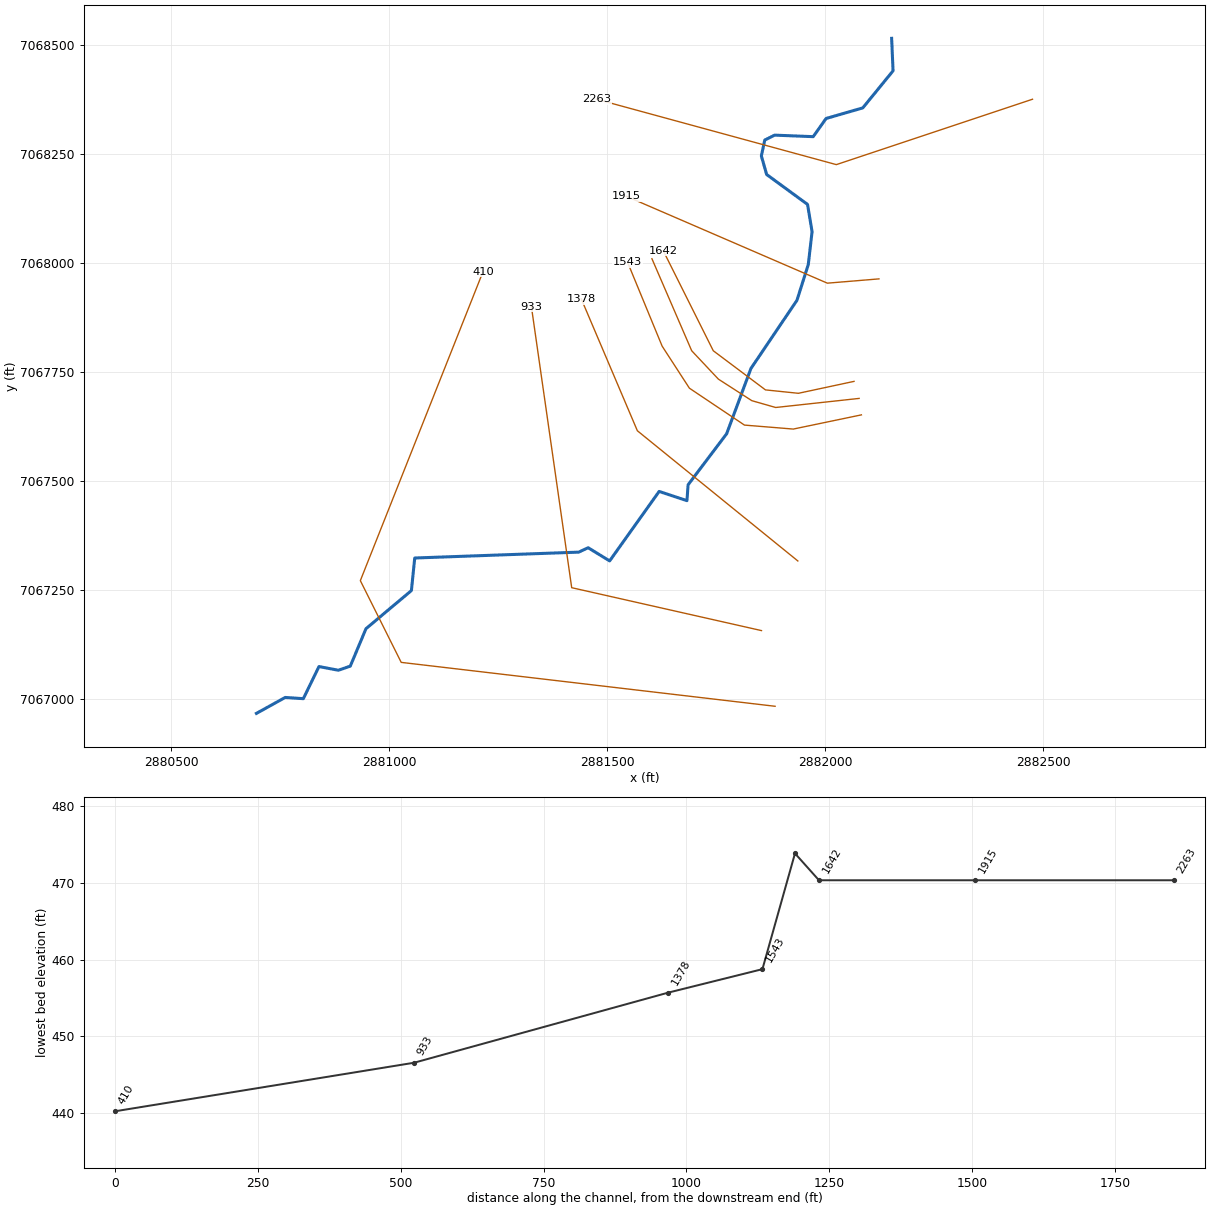
--- UNT 156 in Running Cr Watershed.prj (project) ---

Proj Title=UNT 156 in Running Cr Watershed Base Level Engineering
Current Plan=p01
Default Exp/Contr=0.3,0.1
English Units
Geom File=g01
Flow File=f01
Plan File=p01
BEGIN DESCRIPTION:
UNT 156 in Running Cr Watershed
END DESCRIPTION:

--- UNT 156 in Running Cr Watershed.p01 (plan) ---

Plan Title=Multiple Run
Short Identifier=Multiple
Geom File=g01
Flow File=f01
Subcritical Flow
K Sum by GR= 0
Std Step Tol= 0.01
Critical Tol= 0.01
Num of Std Step Trials= 20
Max Error Tol= 0.3
Flow Tol Ratio= 0.001
Split Flow NTrial= 30
Split Flow Tol= 0.02
Split Flow Ratio= 0.02
Log Output Level= 0
Friction Slope Method= 1
Unsteady Friction Slope Method= 2
Unsteady Bridges Friction Slope Method= 1
Parabolic Critical Depth
Global Vel Dist=  1 , 1 , 1
Global Log Level= 0
CheckData=True
Encroach Param= -1, 0, 0, 0
BEGIN DESCRIPTION:
Multiple Run
END DESCRIPTION:

--- UNT 156 in Running Cr Watershed.f01 (steady flow) ---

Flow Title=Multiple
Number of Profiles=7
Profile Names=10-year,25-year,50-year,1pct_min,100-year,1pct_plu,500-year
River Rch & RM= UNT 156 in Runni,Reach-1,2263
     180     219     248     140     280     559     353
Boundary for River Rch & Prof#=UNT 156 in Runni,Reach-1,1
Up Type=0
Dn Type=3
Dn Slope=0.005
Boundary for River Rch & Prof#=UNT 156 in Runni,Reach-1,2
Up Type=0
Dn Type=3
Dn Slope=0.005
Boundary for River Rch & Prof#=UNT 156 in Runni,Reach-1,3
Up Type=0
Dn Type=3
Dn Slope=0.005
Boundary for River Rch & Prof#=UNT 156 in Runni,Reach-1,4
Up Type=0
Dn Type=3
Dn Slope=0.005
Boundary for River Rch & Prof#=UNT 156 in Runni,Reach-1,5
Up Type=0
Dn Type=3
Dn Slope=0.005
Boundary for River Rch & Prof#=UNT 156 in Runni,Reach-1,6
Up Type=0
Dn Type=3
Dn Slope=0.005
Boundary for River Rch & Prof#=UNT 156 in Runni,Reach-1,7
Up Type=0
Dn Type=3
Dn Slope=0.005

--- UNT 156 in Running Cr Watershed.g01 (geometry) ---

Geom Title=Existing Conditions

River Reach=UNT 156 in Runni,Reach-1
Reach XY= 30
      2882151.82      7068514.67      2882155.11      7068440.19
      2882085.67      7068355.12      2882001.47      7068330.82
      2881971.95      7068289.15      2881883.41      7068292.62
      2881860.84      7068281.34      2881853.03      7068244.88
      2881865.18      7068202.35      2881958.93      7068133.77
      2881969.35      7068071.27      2881960.67      7067995.75
      2881934.63      7067913.72      2881829.16      7067757.47
      2881773.43      7067607.73      2881684.98      7067490.69
      2881682.37      7067454.23      2881618.57      7067475.42
      2881505.03      7067316.04      2881455.72      7067346.25
      2881434.19      7067336.18      2881057.97      7067322.70
      2881050.34      7067248.01      2880946.18      7067160.60
      2880910.17      7067074.70      2880882.77      7067065.25
      2880838.34      7067073.76      2880802.43      7067000.04
      2880760.84      7067002.87      2880694.91      7066966.34

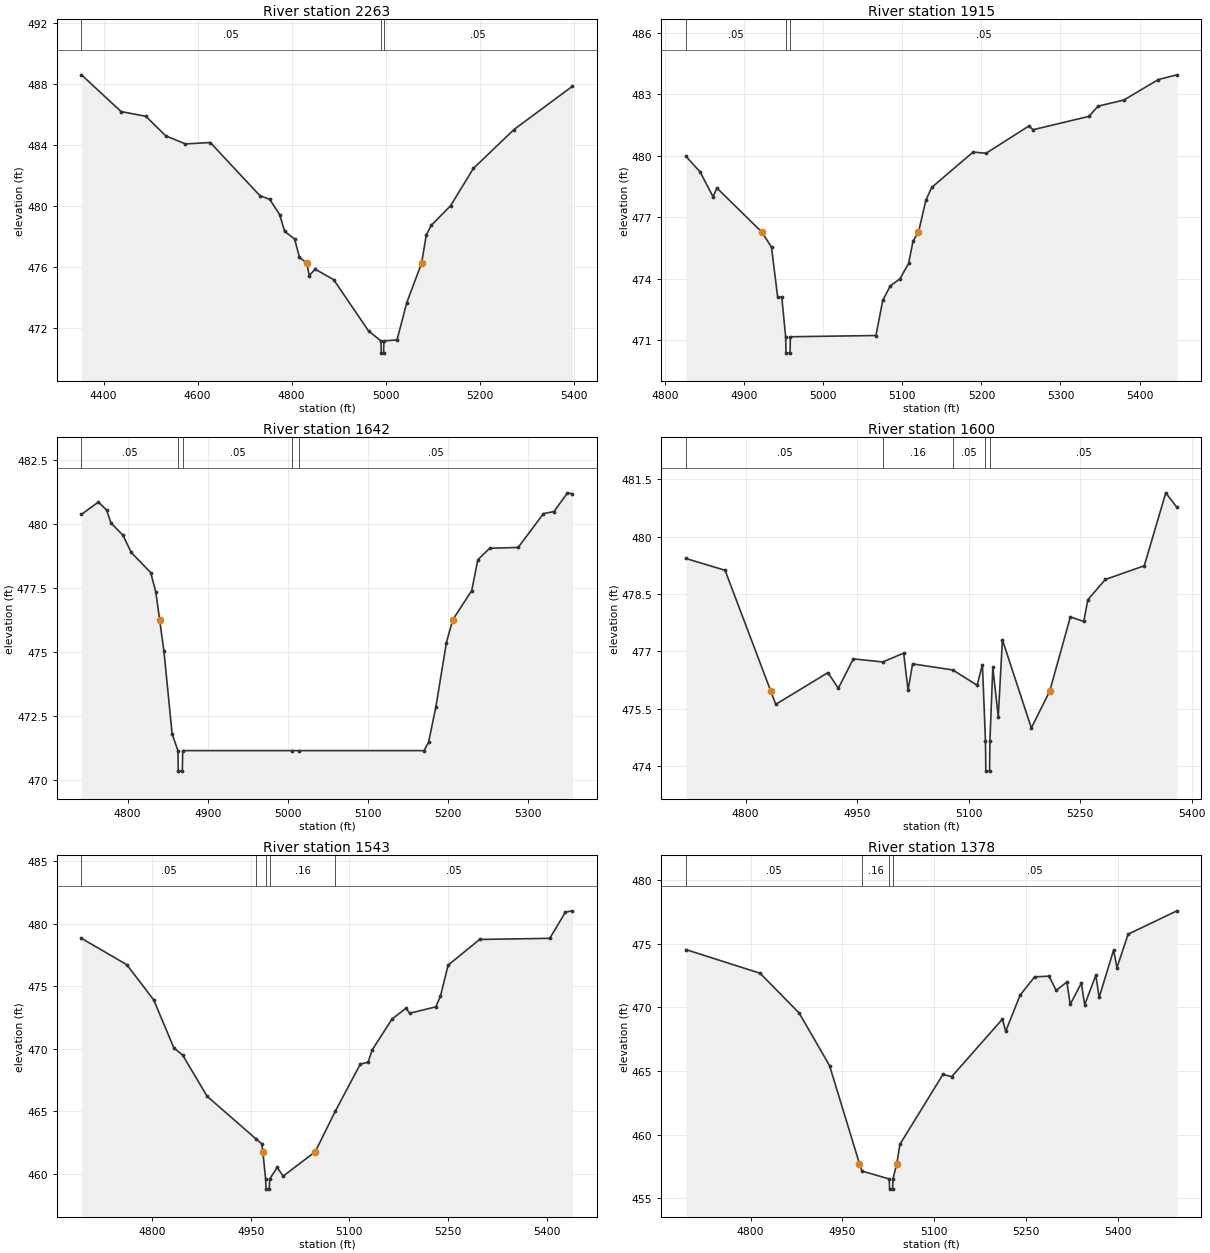
Type RM Length L Ch R = 1,2263,348,348,348
BEGIN DESCRIPTION:
UNT 156 in Running Cr Watershed 5.0
END DESCRIPTION:
XS GIS Cut Line= 3
      2882474.98      7068374.99      2882025.00      7068225.00
      2881475.01      7068375.00
#Sta/Elev= 30
  4353.1  488.61  4437.4  486.20  4490.1  485.89  4532.3  484.61  4574.4  484.08
  4627.1  484.17  4732.6  480.69  4753.6  480.44  4774.7  479.45  4785.3  478.34
  4806.3  477.85  4816.9  476.65  4832.3  476.26  4837.8  475.44  4849.9  475.87
  4889.6  475.18  4963.9  471.81  4990.3  471.16  4990.8  470.36  4995.8  470.36
  4996.3  471.16  5024.4  471.23  5045.1  473.67  5076.6  476.26  5086.6  478.10
  5096.9  478.73  5138.4  480.03  5186.7  482.47  5273.1  485.02  5397.5  487.86
#Mann=3,-1,0
  4353.1    0.05       0  4990.3   0.033       0  4996.3    0.05       0
Bank Sta=4832.3,5076.6
Exp/Cntr=0.3,0.1

Type RM Length L Ch R = 1,1915,273,273,273
BEGIN DESCRIPTION:
UNT 156 in Running Cr Watershed 4.0
END DESCRIPTION:
XS GIS Cut Line= 3
      2882122.83      7067962.93      2882004.40      7067953.10
      2881543.45      7068152.32
#Sta/Elev= 30
  4826.3  479.97  4844.2  479.21  4860.5  478.00  4865.5  478.42  4922.6  476.26
  4934.5  475.53  4942.3  473.09  4947.5  473.09  4952.4  471.16  4952.9  470.36
  4957.9  470.36  4958.4  471.16  5066.6  471.22  5075.2  472.93  5084.6  473.64
  5097.0  473.99  5107.9  474.74  5113.6  475.84  5120.4  476.26  5129.7  477.82
  5137.1  478.45  5189.5  480.18  5205.9  480.12  5260.0  481.45  5265.4  481.27
  5335.9  481.92  5347.6  482.42  5380.2  482.72  5423.8  483.72  5447.3  483.95
#Mann=3,-1,0
  4826.3    0.05       0  4952.4   0.033       0  4958.4    0.05       0
Bank Sta=4922.6,5120.4
Exp/Cntr=0.3,0.1

Type RM Length L Ch R = 1,1642,42,42,42
BEGIN DESCRIPTION:
Mapping XS 5f8b8f44
END DESCRIPTION:
XS GIS Cut Line= 5
      2882065.60      7067727.84      2881937.99      7067700.49
      2881862.47      7067708.30      2881742.68      7067798.15
      2881628.09      7068027.33
#Sta/Elev= 30
  4742.5  480.37  4763.6  480.85  4773.8  480.54  4779.4  480.03  4794.2  479.56
  4804.5  478.89  4828.8  478.10  4835.2  477.35  4840.0  476.26  4845.4  475.03
  4855.6  471.81  4862.8  471.16  4863.3  470.36  4868.3  470.36  4868.8  471.16
  5005.1  471.16  5014.4  471.16  5169.8  471.16  5175.4  471.48  5184.6  472.87
  5197.7  475.37  5205.6  476.26  5229.3  477.40  5236.9  478.60  5251.7  479.05
  5287.2  479.08  5318.8  480.40  5331.9  480.48  5348.7  481.21  5354.9  481.17
#Mann=5,-1,0
  4742.5    0.05       0  4862.8    0.03       0  4868.8    0.05       0
  5005.1    0.16       0  5014.4    0.05       0
Bank Sta=4840,5205.6
Exp/Cntr=0.3,0.1

Type RM Length L Ch R = 1,1600,57,57,57
BEGIN DESCRIPTION:
Mapping XS 52f598c9
END DESCRIPTION:
XS GIS Cut Line= 6
      2882077.31      7067688.77      2881885.91      7067667.94
      2881831.22      7067683.56      2881754.40      7067733.04
      2881693.20      7067798.15      2881602.06      7068009.08
#Sta/Elev= 30
  4719.9  479.43  4772.5  479.12  4834.1  475.95  4840.7  475.61  4910.8  476.44
  4924.8  476.03  4945.0  476.80  4984.6  476.72  5012.7  476.95  5018.6  475.98
  5024.7  476.67  5078.8  476.51  5111.5  476.11  5118.6  476.65  5122.7  474.66
  5123.2  473.86  5128.2  473.86  5128.7  474.66  5132.6  476.58  5139.9  475.28
  5145.5  477.30  5184.4  474.99  5209.0  475.95  5236.9  477.90  5254.9  477.78
  5260.4  478.35  5283.9  478.88  5336.3  479.24  5365.2  481.15  5380.2  480.77
#Mann=5,-1,0
  4719.9    0.05       0  4984.6    0.16       0  5078.8    0.05       0
  5122.7    0.07       0  5128.7    0.05       0
Bank Sta=4834.1,5209
Exp/Cntr=0.3,0.1

Type RM Length L Ch R = 1,1543,165,165,165
BEGIN DESCRIPTION:
Mapping XS 88c55586
END DESCRIPTION:
XS GIS Cut Line= 6
      2882082.51      7067651.01      2881926.28      7067618.46
      2881814.30      7067627.57      2881687.99      7067712.21
      2881625.49      7067808.56      2881546.32      7068000.66
#Sta/Elev= 30
  4692.6  478.83  4761.6  476.72  4802.4  473.91  4833.1  470.07  4846.5  469.49
  4883.6  466.20  4958.6  462.76  4966.7  462.40  4968.4  461.76  4972.7  459.57
  4973.2  458.77  4978.2  458.77  4978.7  459.57  4990.3  460.50  4999.3  459.81
  5048.1  461.76  5078.5  464.99  5116.6  468.77  5128.6  468.93  5134.5  469.89
  5164.8  472.37  5185.9  473.23  5191.9  472.84  5231.4  473.35  5238.4  474.19
  5250.2  476.69  5298.1  478.74  5404.7  478.83  5428.6  480.93  5439.2  481.03
#Mann=5,-1,0
  4692.6    0.05       0  4958.6    0.16       0  4972.7    0.07       0
  4978.7    0.16       0  5078.5    0.05       0
Bank Sta=4968.4,5048.1
Exp/Cntr=0.3,0.1

Type RM Length L Ch R = 1,1378,445,445,445
BEGIN DESCRIPTION:
UNT 156 in Running Cr Watershed 3.0
END DESCRIPTION:
XS GIS Cut Line= 3
      2881936.73      7067315.92      2881568.64      7067614.55
      2881440.15      7067916.67
#Sta/Elev= 30
  4694.4  474.55  4815.5  472.69  4879.4  469.56  4929.0  465.43  4977.9  457.72
  4982.0  457.13  5026.6  456.51  5027.1  455.71  5032.1  455.71  5032.6  456.51
  5039.0  457.72  5044.0  459.23  5114.3  464.73  5128.7  464.56  5211.5  469.08
  5216.9  468.13  5240.5  470.97  5264.2  472.41  5287.8  472.46  5299.3  471.34
  5316.9  472.00  5322.3  470.24  5340.5  471.91  5346.0  470.21  5364.2  472.54
  5369.6  470.79  5393.3  474.53  5398.7  473.13  5416.9  475.76  5496.7  477.60
#Mann=4,-1,0
  4694.4    0.05       0  4982.0    0.16       0  5026.6    0.07       0
  5032.6    0.05       0
Bank Sta=4977.9,5039
Exp/Cntr=0.3,0.1

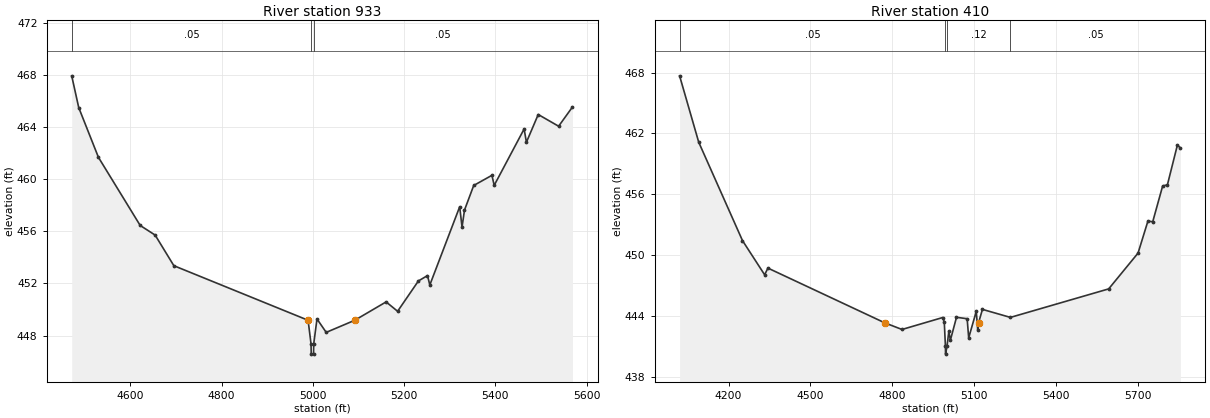
Type RM Length L Ch R = 1,933,523,523,523
BEGIN DESCRIPTION:
UNT 156 in Running Cr Watershed 2.0
END DESCRIPTION:
XS GIS Cut Line= 3
      2881853.35      7067156.22      2881418.02      7067254.63
      2881325.58      7067899.31
#Sta/Elev= 30
  4471.5  467.94  4486.9  465.50  4530.1  461.68  4621.6  456.45  4654.4  455.71
  4695.4  453.36  4989.6  449.17  4996.0  447.37  4996.5  446.57  5001.5  446.57
  5002.0  447.37  5009.1  449.27  5029.3  448.24  5091.9  449.17  5160.6  450.58
  5185.8  449.86  5231.4  452.19  5251.3  452.60  5256.4  451.88  5321.9  457.89
  5327.0  456.32  5332.4  457.63  5352.6  459.52  5392.5  460.30  5397.5  459.53
  5463.1  463.86  5468.1  462.84  5494.0  464.97  5538.7  464.07  5569.1  465.55
#Mann=3,-1,0
  4471.5    0.05       0  4996.0    0.03       0  5002.0    0.05       0
Bank Sta=4989.6,5091.9
Exp/Cntr=0.3,0.1

Type RM Length L Ch R = 1,410,0,0,0
BEGIN DESCRIPTION:
UNT 156 in Running Cr Watershed 1.0
END DESCRIPTION:
XS GIS Cut Line= 4
      2881884.58      7066982.61      2881026.97      7067083.30
      2880933.22      7067270.80      2881214.48      7067979.17
#Sta/Elev= 30
  4020.4  467.68  4090.5  461.14  4250.9  451.44  4332.1  448.07  4344.1  448.73
  4771.9  443.34  4835.5  442.68  4984.9  443.86  4990.5  443.40  4994.6  441.05
  4995.1  440.25  5000.6  441.05  5007.2  442.52  5012.8  441.62  5035.2  443.88
  5074.3  443.74  5079.9  441.85  5107.7  444.47  5113.1  442.61  5116.1  443.34
  5130.3  444.66  5232.8  443.87  5593.0  446.68  5700.6  450.21  5736.7  453.36
  5754.4  453.30  5790.7  456.82  5808.2  456.94  5844.7  460.85  5855.7  460.58
#Mann=4,-1,0
  4020.4    0.05       0  4994.6    0.03       0  5000.6    0.12       0
  5232.8    0.05       0
Bank Sta=4771.9,5116.1
Exp/Cntr=0.3,0.1

Chan Stop Cuts=-1