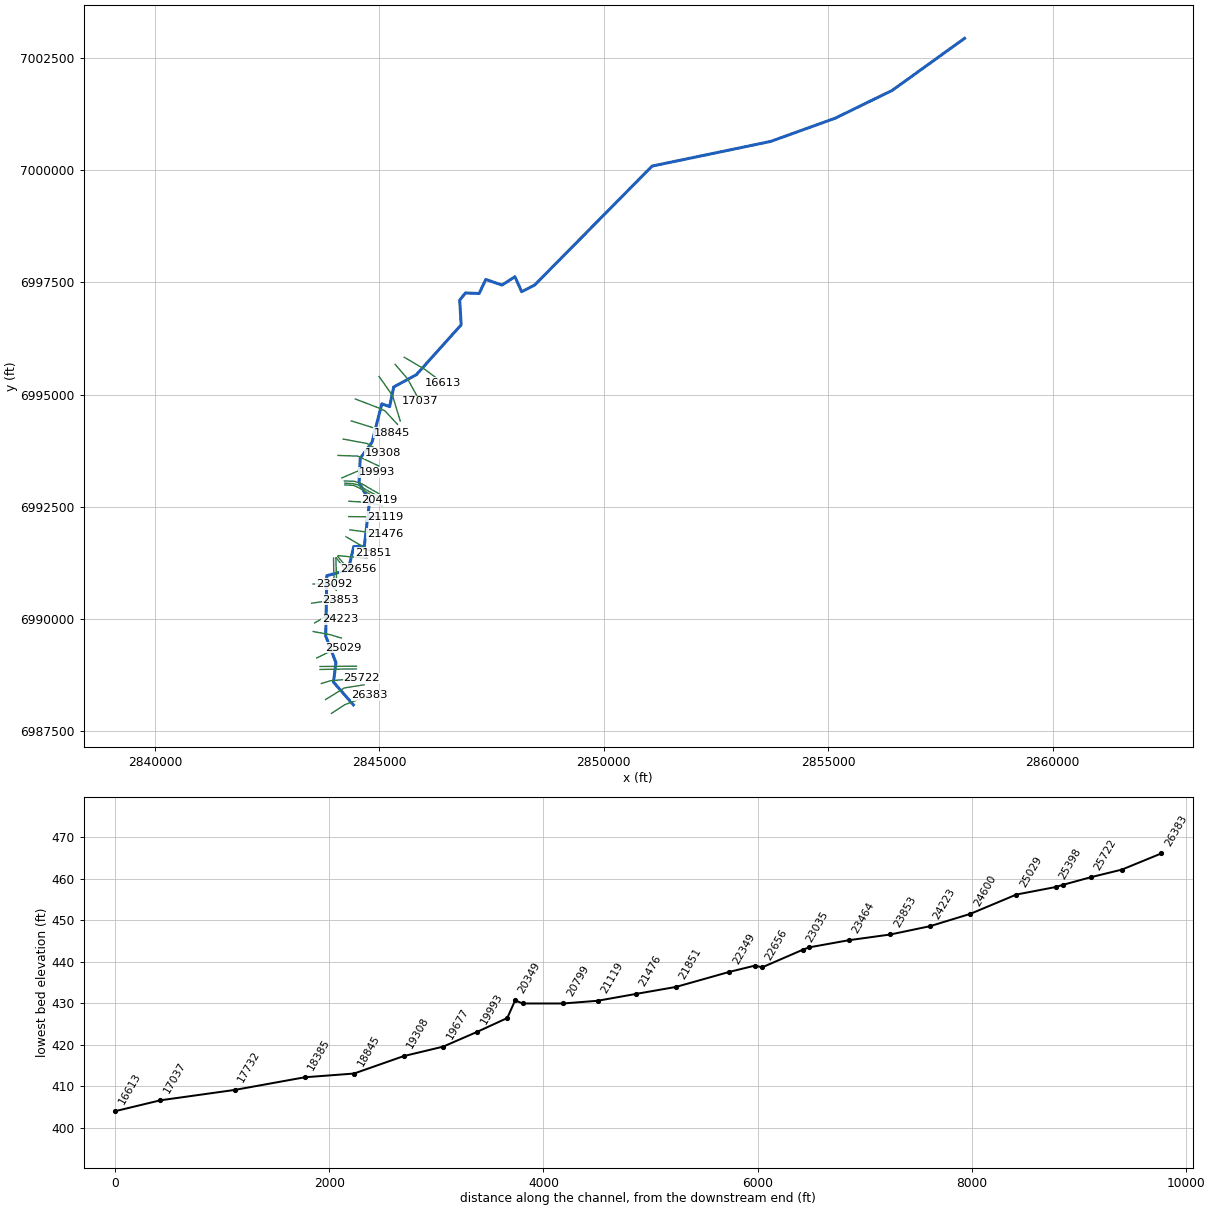
--- WILLIAMS CREEK.prj (project) ---

Proj Title=WILLIAMS CREEK Base Level Engineering
Current Plan=p01
Default Exp/Contr=0.3,0.1
English Units
Geom File=g01
Flow File=f01
Plan File=p01
BEGIN DESCRIPTION:
WILLIAMS CREEK
END DESCRIPTION:

--- WILLIAMS CREEK.p01 (plan) ---

Plan Title=Multiple Run
Short Identifier=Multiple
Geom File=g01
Flow File=f01
Subcritical Flow
K Sum by GR= 0
Std Step Tol= 0.01
Critical Tol= 0.01
Num of Std Step Trials= 20
Max Error Tol= 0.3
Flow Tol Ratio= 0.001
Split Flow NTrial= 30
Split Flow Tol= 0.02
Split Flow Ratio= 0.02
Log Output Level= 0
Friction Slope Method= 1
Unsteady Friction Slope Method= 2
Unsteady Bridges Friction Slope Method= 1
Parabolic Critical Depth
Global Vel Dist=  1 , 1 , 1
Global Log Level= 0
CheckData=True
Encroach Param= -1, 0, 0, 0
BEGIN DESCRIPTION:
Multiple Run
END DESCRIPTION:

--- WILLIAMS CREEK.f01 (steady flow) ---

Flow Title=Multiple
Number of Profiles=7
Profile Names=10-year,25-year,50-year,1pct_min,100-year,1pct_plu,500-year
River Rch & RM= WILLIAMS CREEK,Reach-1,26383
     357     465     550     324     647    1292     896
River Rch & RM= WILLIAMS CREEK,Reach-1,19677
     698     943    1144     689    1376    2744    1992
River Rch & RM= WILLIAMS CREEK,Reach-1,14897
     996    1370    1681    1023    2042    4074    3020
Boundary for River Rch & Prof#=WILLIAMS CREEK,Reach-1,1
Up Type=0
Dn Type=3
Dn Slope=0.005
Boundary for River Rch & Prof#=WILLIAMS CREEK,Reach-1,2
Up Type=0
Dn Type=3
Dn Slope=0.005
Boundary for River Rch & Prof#=WILLIAMS CREEK,Reach-1,3
Up Type=0
Dn Type=3
Dn Slope=0.005
Boundary for River Rch & Prof#=WILLIAMS CREEK,Reach-1,4
Up Type=0
Dn Type=3
Dn Slope=0.005
Boundary for River Rch & Prof#=WILLIAMS CREEK,Reach-1,5
Up Type=0
Dn Type=3
Dn Slope=0.005
Boundary for River Rch & Prof#=WILLIAMS CREEK,Reach-1,6
Up Type=0
Dn Type=3
Dn Slope=0.005
Boundary for River Rch & Prof#=WILLIAMS CREEK,Reach-1,7
Up Type=0
Dn Type=3
Dn Slope=0.005

--- WILLIAMS CREEK.g01 (geometry) ---

Geom Title=Existing Conditions

River Reach=WILLIAMS CREEK,Reach-1
Reach XY= 30
      2844422.00      6988081.23      2843979.29      6988586.87
      2844034.39      6989020.20      2843806.06      6989615.74
      2843830.80      6990961.93      2844307.49      6991085.37
      2844431.27      6991611.94      2844665.85      6991615.63
      2844781.83      6992613.06      2844549.56      6993041.61
      2844575.59      6993580.71      2844838.27      6993937.66
      2845056.07      6994794.61      2845229.72      6994731.04
      2845321.15      6995169.65      2845826.42      6995443.11
      2846823.71      6996555.38      2846791.64      6997107.09
      2846919.90      6997266.30      2847224.50      6997254.14
      2847372.66      6997567.59      2847734.75      6997442.10
      2848022.22      6997628.40      2848172.03      6997293.94
      2848461.07      6997442.23      2851077.47      7000095.25
      2853717.17      7000644.49      2855158.52      7001163.78
      2856428.20      7001783.71      2858039.27      7002944.22

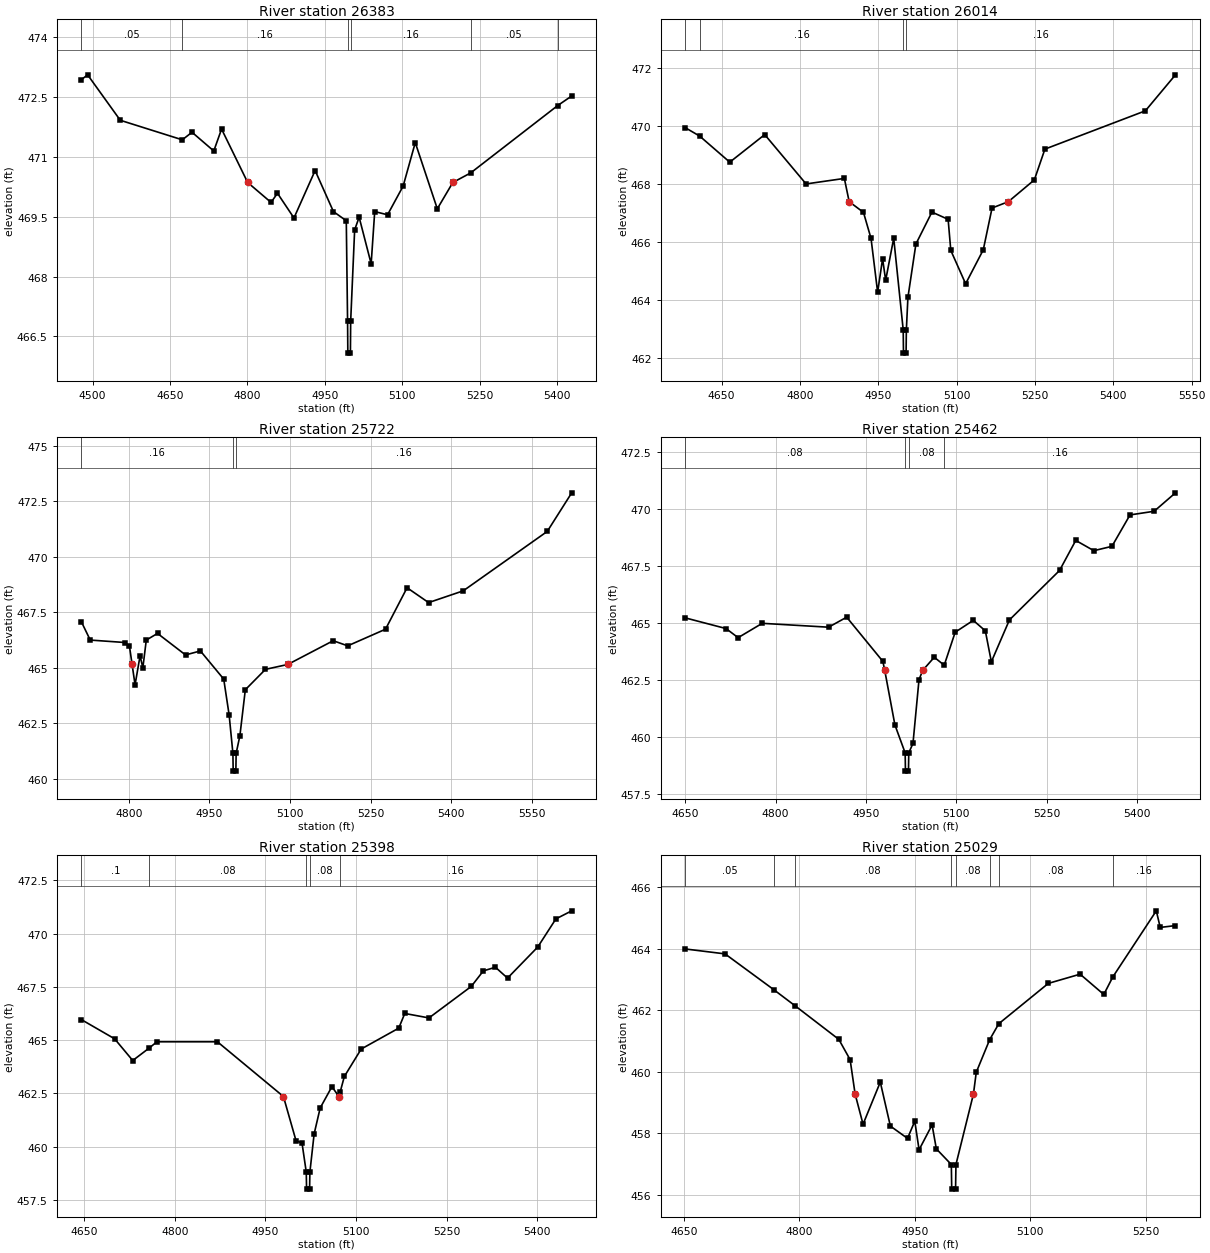
Type RM Length L Ch R = 1,26383,369,369,369
BEGIN DESCRIPTION:
WILLIAMS CREEK 41.0
END DESCRIPTION:
XS GIS Cut Line= 3
      2843934.14      6987890.71      2844231.80      6988084.31
      2844788.79      6988293.90
#Sta/Elev= 30
  4478.2  472.94  4490.2  473.06  4553.5  471.92  4673.7  471.43  4692.5  471.62
  4734.7  471.15  4749.8  471.70  4800.4  470.36  4845.7  469.86  4858.1  470.09
  4890.1  469.47  4931.1  470.66  4966.6  469.63  4991.5  469.40  4994.0  466.88
  4994.5  466.08  4999.5  466.08  5000.0  466.88  5007.7  469.17  5016.4  469.49
  5039.7  468.32  5046.6  469.63  5071.5  469.55  5101.7  470.27  5125.2  471.36
  5167.9  469.70  5198.0  470.36  5232.6  470.60  5401.3  472.29  5428.4  472.53
#Mann=6,-1,0
  4478.2    0.05       0  4673.7    0.16       0  4994.0    0.07       0
  5000.0    0.16       0  5232.6    0.05       0  5401.3    0.16       0
Bank Sta=4800.4,5198
Exp/Cntr=0.3,0.1

Type RM Length L Ch R = 1,26014,292,292,292
BEGIN DESCRIPTION:
WILLIAMS CREEK 40.0
END DESCRIPTION:
XS GIS Cut Line= 3
      2843802.45      6988198.54      2844221.05      6988457.95
      2844661.86      6988527.97
#Sta/Elev= 30
  4580.2  469.95  4607.9  469.66  4665.6  468.76  4732.5  469.71  4811.7  468.01
  4885.0  468.20  4894.2  467.40  4921.6  467.03  4936.1  466.13  4948.7  464.28
  4958.2  465.43  4964.1  464.69  4979.5  466.14  4997.7  462.98  4998.2  462.18
  5003.2  462.18  5003.7  462.98  5006.7  464.10  5022.0  465.94  5052.7  467.04
  5083.7  466.79  5088.8  465.72  5117.2  464.57  5151.0  465.74  5167.8  467.18
  5199.1  467.40  5248.8  468.15  5269.0  469.21  5461.4  470.53  5519.0  471.77
#Mann=4,-1,0
  4580.2    0.05       0  4607.9    0.16       0  4997.7    0.07       0
  5003.7    0.16       0
Bank Sta=4894.2,5199.1
Exp/Cntr=0.3,0.1

Type RM Length L Ch R = 1,25722,260,260,260
BEGIN DESCRIPTION:
WILLIAMS CREEK 39.0
END DESCRIPTION:
XS GIS Cut Line= 3
      2843709.32      6988557.71      2843916.37      6988619.41
      2844610.37      6988676.67
#Sta/Elev= 30
  4712.0  467.07  4728.4  466.25  4793.1  466.14  4801.4  465.97  4806.3  465.15
  4811.8  464.23  4821.1  465.54  4826.3  465.00  4832.7  466.25  4853.6  466.55
  4905.7  465.58  4933.4  465.76  4976.8  464.49  4986.9  462.87  4993.9  461.14
  4994.4  460.34  4999.4  460.34  4999.9  461.14  5006.9  461.94  5017.0  464.01
  5054.5  464.93  5096.0  465.15  5180.5  466.22  5207.6  465.99  5277.9  466.74
  5318.0  468.61  5358.1  467.94  5422.5  468.47  5578.9  471.15  5624.4  472.89
#Mann=3,-1,0
  4712.0    0.16       0  4993.9    0.07       0  4999.9    0.16       0
Bank Sta=4806.3,5096
Exp/Cntr=0.3,0.1

Type RM Length L Ch R = 1,25462,64,64,64
BEGIN DESCRIPTION:
Mapping XS bd23f3f9
END DESCRIPTION:
XS GIS Cut Line= 3
      2843677.18      6988869.41      2844090.63      6988877.01
      2844490.37      6988882.83
#Sta/Elev= 30
  4650.1  465.23  4717.9  464.76  4737.9  464.36  4777.9  464.99  4888.0  464.82
  4918.0  465.26  4978.0  463.32  4981.1  462.93  4998.0  460.53  5015.0  459.30
  5015.5  458.50  5020.5  458.50  5021.0  459.30  5028.0  459.72  5038.0  462.52
  5044.3  462.93  5063.3  463.50  5079.8  463.15  5098.0  464.60  5128.0  465.12
  5148.0  464.66  5158.0  463.30  5188.0  465.14  5271.1  467.31  5298.0  468.63
  5328.0  468.18  5358.0  468.37  5388.0  469.75  5428.0  469.91  5463.4  470.72
#Mann=4,-1,0
  4650.1    0.08       0  5015.0    0.07       0  5021.0    0.08       0
  5079.8    0.16       0
Bank Sta=4981.1,5044.3
Exp/Cntr=0.3,0.1

Type RM Length L Ch R = 1,25398,369,369,369
BEGIN DESCRIPTION:
WILLIAMS CREEK 38.0
END DESCRIPTION:
XS GIS Cut Line= 3
      2843680.05      6988936.25      2844098.87      6988939.51
      2844491.22      6988943.62
#Sta/Elev= 30
  4645.6  465.96  4700.5  465.06  4730.5  464.04  4757.9  464.63  4770.5  464.92
  4870.6  464.92  4979.8  462.35  5000.6  460.28  5010.6  460.16  5017.6  458.80
  5018.1  458.00  5023.1  458.00  5023.6  458.80  5030.6  460.59  5040.6  461.81
  5060.0  462.81  5071.7  462.35  5073.6  462.55  5080.6  463.29  5108.5  464.58
  5170.6  465.56  5180.6  466.25  5220.6  466.04  5290.6  467.52  5310.6  468.25
  5330.6  468.42  5350.6  467.91  5400.6  469.37  5430.6  470.69  5456.8  471.07
#Mann=5,-1,0
  4645.6     0.1       0  4757.9    0.08       0  5017.6    0.07       0
  5023.6    0.08       0  5073.6    0.16       0
Bank Sta=4979.8,5071.7
Exp/Cntr=0.3,0.1

Type RM Length L Ch R = 1,25029,429,429,429
BEGIN DESCRIPTION:
WILLIAMS CREEK 37.0
END DESCRIPTION:
XS GIS Cut Line= 3
      2843606.19      6989125.74      2843963.67      6989303.01
      2844195.88      6989355.09
#Sta/Elev= 30
  4651.8  463.99  4703.6  463.83  4766.7  462.67  4794.7  462.14  4851.4  461.05
  4866.1  460.39  4872.6  459.27  4882.9  458.29  4905.3  459.66  4918.4  458.23
  4940.7  457.83  4950.1  458.39  4955.7  457.46  4972.6  458.27  4978.1  457.49
  4997.6  456.98  4998.1  456.18  5003.1  456.18  5003.6  456.98  5026.3  459.27
  5030.0  459.98  5047.4  461.04  5059.3  461.56  5123.6  462.87  5164.9  463.17
  5195.7  462.51  5207.4  463.08  5263.9  465.23  5269.0  464.69  5288.8  464.75
#Mann=8,-1,0
  4651.8    0.05       0  4766.7    0.16       0  4794.7    0.08       0
  4997.6    0.07       0  5003.6    0.08       0  5047.4     0.1       0
  5059.3    0.08       0  5207.4    0.16       0
Bank Sta=4872.6,5026.3
Exp/Cntr=0.3,0.1

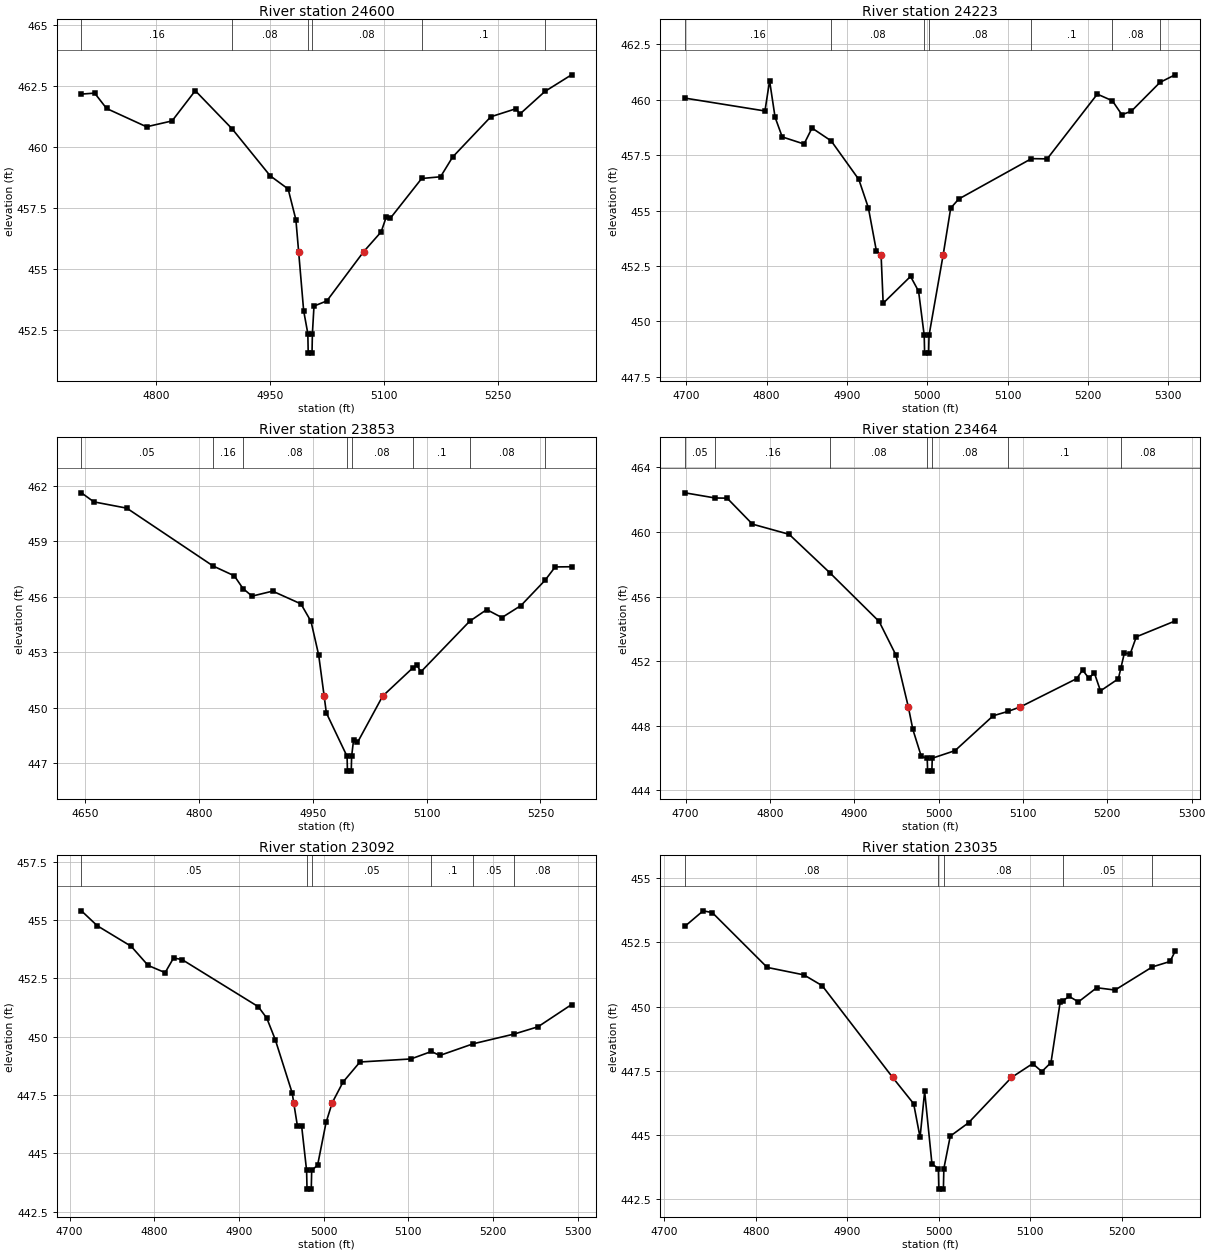
Type RM Length L Ch R = 1,24600,377,377,377
BEGIN DESCRIPTION:
WILLIAMS CREEK 36.0
END DESCRIPTION:
XS GIS Cut Line= 3
      2843527.88      6989716.21      2843906.38      6989645.02
      2844154.66      6989570.36
#Sta/Elev= 30
  4702.1  462.16  4719.5  462.20  4735.2  461.57  4787.7  460.82  4821.3  461.06
  4851.8  462.30  4900.4  460.73  4950.3  458.81  4973.9  458.27  4984.1  457.01
  4987.7  455.70  4994.3  453.28  4999.8  452.34  5000.3  451.54  5005.3  451.54
  5005.8  452.34  5007.9  453.47  5024.8  453.68  5073.2  455.70  5096.2  456.51
  5103.1  457.14  5108.3  457.07  5149.5  458.70  5174.3  458.77  5190.2  459.58
  5240.4  461.23  5273.4  461.56  5278.6  461.34  5311.6  462.27  5346.5  462.95
#Mann=6,-1,0
  4702.1    0.16       0  4900.4    0.08       0  4999.8    0.07       0
  5005.8    0.08       0  5149.5     0.1       0  5311.6    0.16       0
Bank Sta=4987.7,5073.2
Exp/Cntr=0.3,0.1

Type RM Length L Ch R = 1,24223,370,370,370
BEGIN DESCRIPTION:
WILLIAMS CREEK 35.0
END DESCRIPTION:
XS GIS Cut Line= 4
      2843558.26      6989907.15      2843772.17      6990032.73
      2843911.16      6990033.48      2844129.88      6989989.21
#Sta/Elev= 30
  4698.3  460.07  4797.9  459.49  4803.7  460.85  4810.5  459.21  4819.4  458.32
  4846.6  458.00  4856.5  458.72  4880.4  458.14  4914.8  456.40  4926.7  455.12
  4936.6  453.19  4942.5  453.00  4945.1  450.82  4979.2  452.03  4989.2  451.36
  4996.2  449.37  4996.7  448.57  5001.7  448.57  5002.2  449.37  5019.8  453.00
  5029.2  455.11  5039.2  455.52  5129.7  457.34  5149.3  457.33  5211.7  460.25
  5230.5  459.95  5242.3  459.32  5254.1  459.48  5289.8  460.78  5308.5  461.12
#Mann=7,-1,0
  4698.3    0.16       0  4880.4    0.08       0  4996.2    0.07       0
  5002.2    0.08       0  5129.7     0.1       0  5230.5    0.08       0
  5289.8    0.16       0
Bank Sta=4942.5,5019.8
Exp/Cntr=0.3,0.1

Type RM Length L Ch R = 1,23853,389,389,389
BEGIN DESCRIPTION:
WILLIAMS CREEK 34.0
END DESCRIPTION:
XS GIS Cut Line= 3
      2843495.81      6990347.28      2843899.44      6990407.17
      2844136.42      6990425.00
#Sta/Elev= 30
  4645.2  461.63  4661.6  461.14  4705.0  460.80  4818.7  457.67  4846.6  457.14
  4858.1  456.45  4870.0  456.04  4897.1  456.31  4934.4  455.62  4947.7  454.67
  4957.8  452.85  4965.0  450.63  4967.9  449.72  4995.2  447.37  4995.7  446.57
  5000.7  446.57  5001.2  447.37  5003.8  448.27  5008.9  448.12  5042.1  450.63
  5081.9  452.16  5087.4  452.30  5092.4  451.94  5156.7  454.68  5179.2  455.31
  5199.2  454.88  5224.3  455.53  5255.9  456.89  5269.4  457.62  5290.9  457.63
#Mann=8,-1,0
  4645.2    0.05       0  4818.7    0.16       0  4858.1    0.08       0
  4995.2    0.07       0  5001.2    0.08       0  5081.9     0.1       0
  5156.7    0.08       0  5255.9    0.16       0
Bank Sta=4965,5042.1
Exp/Cntr=0.3,0.1

Type RM Length L Ch R = 1,23464,372,372,372
BEGIN DESCRIPTION:
WILLIAMS CREEK 33.0
END DESCRIPTION:
XS GIS Cut Line= 3
      2843525.04      6990775.00      2843890.32      6990789.99
      2844041.34      6990636.38
#Sta/Elev= 30
  4699.3  462.43  4735.1  462.11  4749.3  462.10  4779.3  460.49  4822.8  459.86
  4871.4  457.46  4929.5  454.46  4949.5  452.37  4964.1  449.17  4969.5  447.77
  4979.5  446.10  4986.5  445.99  4987.0  445.19  4992.0  445.19  4992.5  445.99
  5019.5  446.46  5064.7  448.62  5082.3  448.89  5097.0  449.17  5163.7  450.92
  5170.7  451.45  5177.8  450.97  5184.8  451.25  5191.9  450.16  5213.1  450.91
  5216.2  451.60  5220.2  452.50  5227.2  452.46  5234.4  453.51  5280.3  454.49
#Mann=7,-1,0
  4699.3    0.05       0  4735.1    0.16       0  4871.4    0.08       0
  4986.5    0.07       0  4992.5    0.08       0  5082.3     0.1       0
  5216.2    0.08       0
Bank Sta=4964.1,5097
Exp/Cntr=0.3,0.1

Type RM Length L Ch R = 1,23092,57,57,57
BEGIN DESCRIPTION:
WILLIAMS CREEK 32.0
END DESCRIPTION:
XS GIS Cut Line= 3
      2843980.60      6991353.74      2843983.86      6991097.71
      2843995.79      6990775.48
#Sta/Elev= 30
  4714.0  455.39  4732.7  454.75  4772.7  453.87  4792.7  453.05  4812.8  452.74
  4822.8  453.37  4832.8  453.30  4922.8  451.28  4932.8  450.79  4942.8  449.87
  4962.8  447.58  4964.6  447.16  4968.9  446.18  4973.9  446.18  4979.8  444.26
  4980.3  443.46  4985.3  443.46  4985.8  444.26  4992.8  444.49  5002.8  446.32
  5010.0  447.16  5022.8  448.05  5042.8  448.91  5102.9  449.04  5127.1  449.36
  5137.0  449.19  5176.4  449.69  5225.0  450.11  5253.0  450.42  5292.5  451.37
#Mann=6,-1,0
  4714.0    0.05       0  4979.8    0.03       0  4985.8    0.05       0
  5127.1     0.1       0  5176.4    0.05       0  5225.0    0.08       0
Bank Sta=4964.6,5010
Exp/Cntr=0.3,0.1

Type RM Length L Ch R = 1,23035,379,379,379
BEGIN DESCRIPTION:
Mapping XS 6809a430
END DESCRIPTION:
XS GIS Cut Line= 3
      2844032.68      6991354.90      2844039.20      6991118.33
      2844049.98      6990819.49
#Sta/Elev= 30
  4722.4  453.12  4742.3  453.72  4752.3  453.65  4812.3  451.52  4852.4  451.23
  4872.4  450.81  4949.5  447.24  4972.4  446.22  4979.4  444.91  4984.4  446.70
  4992.4  443.88  4999.4  443.70  4999.9  442.90  5004.9  442.90  5005.4  443.70
  5012.4  444.96  5032.4  445.48  5079.3  447.24  5102.5  447.78  5112.5  447.47
  5122.5  447.82  5132.5  450.16  5135.5  450.23  5142.5  450.39  5152.5  450.18
  5172.5  450.73  5192.5  450.64  5233.3  451.54  5252.6  451.75  5258.1  452.14
#Mann=5,-1,0
  4722.4    0.08       0  4999.4    0.07       0  5005.4    0.08       0
  5135.5    0.05       0  5233.3    0.08       0
Bank Sta=4949.5,5079.3
Exp/Cntr=0.3,0.1

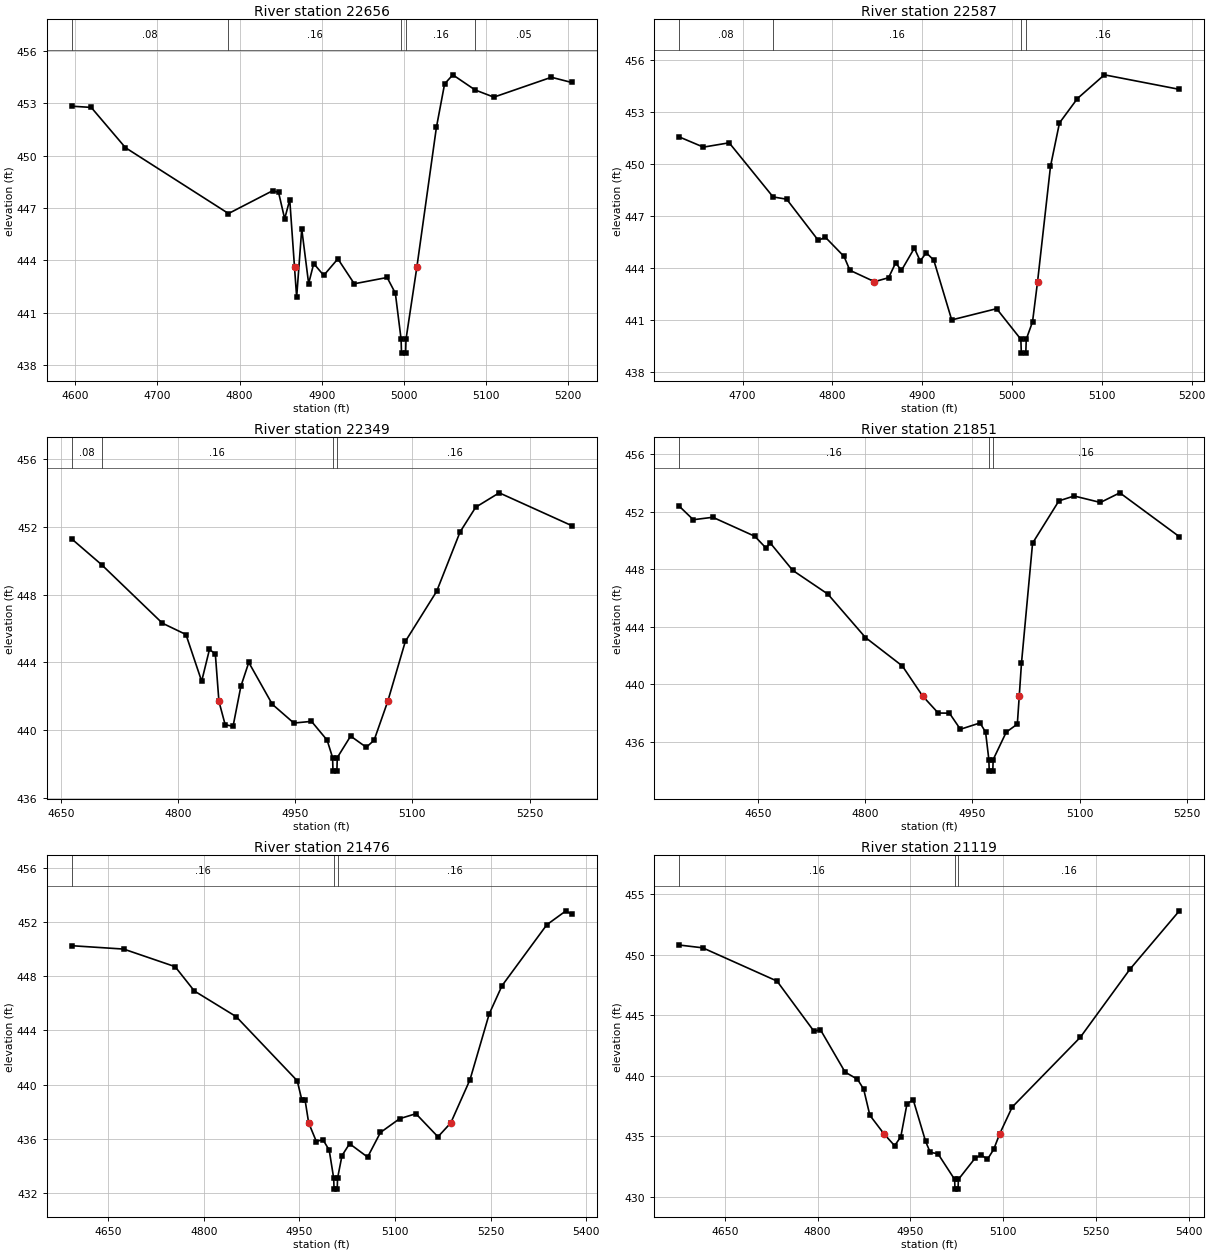
Type RM Length L Ch R = 1,22656,69,69,69
BEGIN DESCRIPTION:
Mapping XS 6728065b
END DESCRIPTION:
XS GIS Cut Line= 3
      2844044.20      6991356.99      2844227.78      6991110.91
      2844529.86      6991112.21
#Sta/Elev= 30
  4595.5  452.84  4619.3  452.77  4661.0  450.46  4786.5  446.68  4840.3  447.99
  4847.5  447.89  4854.9  446.38  4861.1  447.47  4866.9  443.60  4869.5  441.88
  4875.7  445.80  4884.1  442.66  4890.3  443.81  4902.5  443.13  4919.7  444.08
  4939.7  442.65  4979.7  443.01  4989.7  442.11  4996.7  439.47  4997.2  438.67
  5002.2  438.67  5002.7  439.47  5015.9  443.60  5039.7  451.62  5049.7  454.12
  5059.7  454.64  5086.9  453.77  5109.7  453.36  5179.7  454.50  5204.6  454.20
#Mann=5,-1,0
  4595.5    0.08       0  4786.5    0.16       0  4996.7    0.07       0
  5002.7    0.16       0  5086.9    0.05       0
Bank Sta=4866.9,5015.9
Exp/Cntr=0.3,0.1

Type RM Length L Ch R = 1,22587,238,238,238
BEGIN DESCRIPTION:
WILLIAMS CREEK 31.0
END DESCRIPTION:
XS GIS Cut Line= 3
      2844074.11      6991392.18      2844248.62      6991177.09
      2844528.54      6991176.01
#Sta/Elev= 30
  4629.4  451.57  4656.3  450.98  4685.0  451.23  4733.9  448.10  4749.0  447.97
  4784.2  445.59  4792.1  445.77  4812.9  444.66  4819.4  443.86  4846.8  443.20
  4862.5  443.43  4870.4  444.29  4876.8  443.85  4891.2  445.14  4897.7  444.40
  4904.5  444.87  4912.8  444.45  4932.8  440.99  4982.8  441.64  5009.8  439.87
  5010.3  439.07  5015.3  439.07  5015.8  439.87  5022.8  440.88  5028.4  443.20
  5042.8  449.87  5052.8  452.38  5072.8  453.79  5102.8  455.16  5186.3  454.32
#Mann=4,-1,0
  4629.4    0.08       0  4733.9    0.16       0  5009.8    0.07       0
  5015.8    0.16       0
Bank Sta=4846.8,5028.4
Exp/Cntr=0.3,0.1

Type RM Length L Ch R = 1,22349,498,498,498
BEGIN DESCRIPTION:
WILLIAMS CREEK 30.0
END DESCRIPTION:
XS GIS Cut Line= 3
      2844089.47      6991408.55      2844378.78      6991379.62
      2844727.81      6991362.64
#Sta/Elev= 30
  4663.9  451.29  4702.1  449.77  4780.0  446.31  4810.2  445.64  4830.3  442.88
  4840.3  444.76  4847.8  444.49  4852.4  441.69  4860.4  440.31  4870.5  440.22
  4880.5  442.58  4890.6  443.99  4920.7  441.52  4948.3  440.41  4970.9  440.51
  4990.9  439.40  4997.9  438.37  4998.4  437.57  5003.4  437.57  5003.9  438.37
  5021.0  439.64  5041.0  438.98  5051.0  439.39  5068.5  441.69  5091.0  445.23
  5131.1  448.19  5161.1  451.70  5181.1  453.16  5211.2  454.01  5304.1  452.07
#Mann=4,-1,0
  4663.9    0.08       0  4702.1    0.16       0  4997.9    0.07       0
  5003.9    0.16       0
Bank Sta=4852.4,5068.5
Exp/Cntr=0.3,0.1

Type RM Length L Ch R = 1,21851,375,375,375
BEGIN DESCRIPTION:
WILLIAMS CREEK 29.0
END DESCRIPTION:
XS GIS Cut Line= 3
      2844255.59      6991831.37      2844588.89      6991636.95
      2844856.25      6991473.75
#Sta/Elev= 30
  4540.3  452.37  4559.9  451.43  4587.2  451.60  4645.9  450.28  4661.6  449.46
  4667.4  449.82  4698.9  447.91  4748.0  446.26  4800.6  443.24  4852.2  441.26
  4880.4  439.18  4902.3  437.99  4918.0  437.98  4933.3  436.86  4960.7  437.30
  4968.5  436.67  4973.1  434.75  4973.6  433.95  4978.6  433.95  4979.1  434.75
  4997.4  436.66  5012.9  437.22  5015.6  439.18  5018.7  441.46  5034.2  449.80
  5071.0  452.74  5092.3  453.08  5129.0  452.63  5156.2  453.30  5239.4  450.25
#Mann=3,-1,0
  4540.3    0.16       0  4973.1    0.07       0  4979.1    0.16       0
Bank Sta=4880.4,5015.6
Exp/Cntr=0.3,0.1

Type RM Length L Ch R = 1,21476,357,357,357
BEGIN DESCRIPTION:
WILLIAMS CREEK 28.0
END DESCRIPTION:
XS GIS Cut Line= 3
      2844344.09      6991983.30      2844704.78      6991936.43
      2845124.05      6991897.36
#Sta/Elev= 30
  4592.5  450.27  4674.1  450.02  4754.8  448.72  4785.0  446.92  4850.7  445.02
  4946.4  440.28  4953.8  438.84  4958.8  438.84  4964.4  437.16  4976.5  435.78
  4986.6  435.93  4996.6  435.15  5003.7  433.06  5004.2  432.26  5009.2  432.26
  5009.7  433.06  5016.7  434.74  5028.6  435.62  5056.9  434.63  5077.0  436.45
  5107.1  437.47  5132.7  437.84  5167.3  436.13  5187.4  437.16  5217.6  440.36
  5247.7  445.22  5267.8  447.31  5338.1  451.82  5368.2  452.85  5377.3  452.58
#Mann=3,-1,0
  4592.5    0.16       0  5003.7    0.07       0  5009.7    0.16       0
Bank Sta=4964.4,5187.4
Exp/Cntr=0.3,0.1

Type RM Length L Ch R = 1,21119,320,320,320
BEGIN DESCRIPTION:
WILLIAMS CREEK 27.0
END DESCRIPTION:
XS GIS Cut Line= 3
      2844317.14      6992278.88      2844725.00      6992275.00
      2845125.02      6992275.00
#Sta/Elev= 30
  4576.5  450.81  4614.4  450.58  4734.4  447.83  4794.4  443.66  4804.4  443.82
  4844.4  440.30  4864.4  439.71  4874.4  438.89  4884.4  436.73  4907.1  435.20
  4924.4  434.21  4934.4  434.95  4944.4  437.67  4954.4  438.02  4974.4  434.58
  4981.9  433.66  4994.4  433.55  5021.4  431.42  5021.9  430.62  5026.9  430.62
  5027.4  431.42  5054.4  433.18  5064.4  433.44  5074.4  433.09  5084.4  433.90
  5094.2  435.20  5114.4  437.41  5224.4  443.18  5304.4  448.80  5384.4  453.64
#Mann=3,-1,0
  4576.5    0.16       0  5021.4    0.07       0  5027.4    0.16       0
Bank Sta=4907.1,5094.2
Exp/Cntr=0.3,0.1

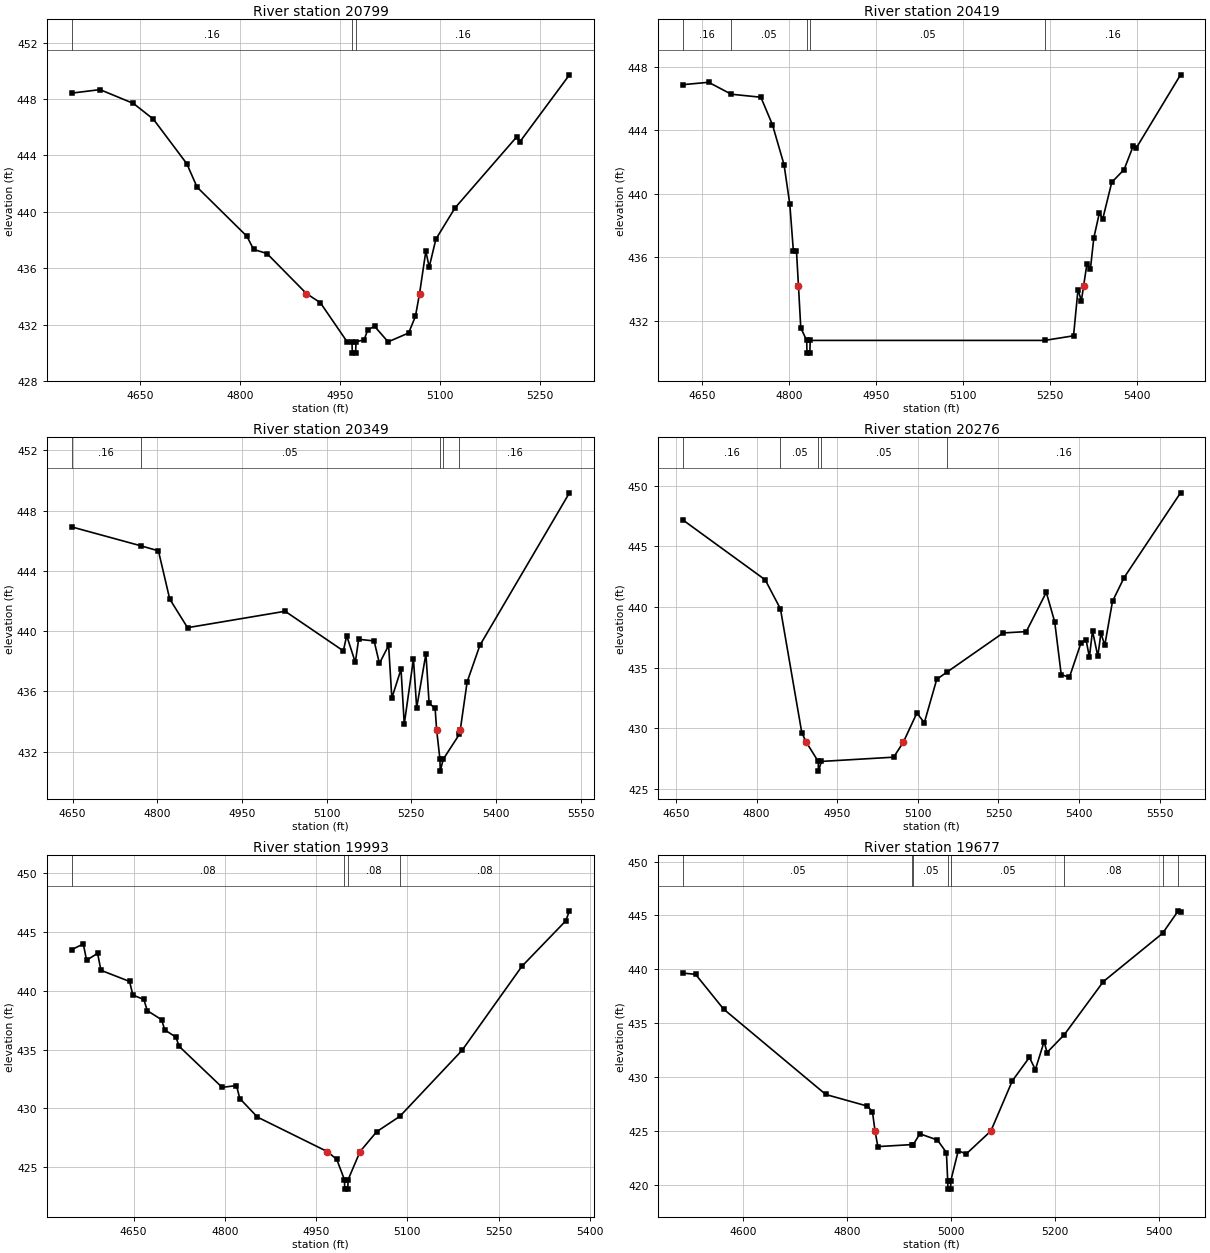
Type RM Length L Ch R = 1,20799,380,380,380
BEGIN DESCRIPTION:
WILLIAMS CREEK 26.0
END DESCRIPTION:
XS GIS Cut Line= 3
      2844322.40      6992621.11      2844727.13      6992597.23
      2845060.66      6992523.60
#Sta/Elev= 30
  4546.9  448.42  4589.6  448.67  4639.7  447.69  4669.7  446.57  4719.8  443.41
  4735.2  441.75  4810.0  438.26  4820.0  437.33  4840.0  437.04  4899.2  434.20
  4920.1  433.55  4960.4  430.77  4967.6  430.77  4968.1  429.97  4973.1  429.97
  4973.6  430.77  4985.9  430.92  4991.1  431.61  5001.4  431.88  5021.8  430.77
  5052.6  431.40  5062.8  432.58  5069.0  434.20  5078.4  437.20  5083.5  436.08
  5093.5  438.06  5122.1  440.27  5214.6  445.31  5219.7  444.98  5293.9  449.72
#Mann=3,-1,0
  4546.9    0.16       0  4967.6    0.07       0  4973.6    0.16       0
Bank Sta=4899.2,5069
Exp/Cntr=0.3,0.1

Type RM Length L Ch R = 1,20419,70,70,70
BEGIN DESCRIPTION:
Mapping XS e53be8d0
END DESCRIPTION:
XS GIS Cut Line= 5
      2844230.12      6992985.69      2844422.23      6992975.92
      2844555.69      6992917.33      2844690.24      6992838.12
      2845003.24      6992649.67
#Sta/Elev= 30
  4616.3  446.86  4661.2  447.01  4700.3  446.26  4751.4  446.07  4771.4  444.34
  4791.4  441.83  4801.4  439.33  4807.5  436.40  4812.9  436.40  4816.3  434.20
  4820.3  431.56  4830.5  430.77  4831.0  429.97  4836.0  429.97  4836.5  430.77
  5241.3  430.77  5291.2  431.06  5298.9  433.97  5304.7  433.26  5308.6  434.20
  5314.4  435.60  5320.3  435.25  5326.2  437.22  5335.8  438.79  5341.6  438.41
  5357.2  440.72  5378.5  441.52  5394.1  442.99  5399.9  442.90  5475.9  447.48
#Mann=5,-1,0
  4616.3    0.16       0  4700.3    0.05       0  4830.5   0.035       0
  4836.5    0.05       0  5241.3    0.16       0
Bank Sta=4816.3,5308.6
Exp/Cntr=0.3,0.1

Type RM Length L Ch R = 1,20349,73,73,73
BEGIN DESCRIPTION:
Mapping XS cfff0398
END DESCRIPTION:
XS GIS Cut Line= 6
      2844231.27      6993023.67      2844412.46      6993014.99
      2844525.31      6992985.69      2844617.54      6992932.52
      2844729.30      6992863.08      2845035.29      6992701.40
#Sta/Elev= 30
  4648.3  446.92  4770.5  445.67  4802.2  445.33  4822.2  442.13  4853.8  440.23
  5026.7  441.32  5129.8  438.69  5135.7  439.70  5151.0  437.93  5156.9  439.46
  5184.3  439.35  5193.7  437.86  5210.0  439.05  5215.7  435.56  5232.0  437.47
  5237.7  433.83  5254.0  438.15  5259.7  434.91  5276.1  438.50  5281.7  435.22
  5292.4  434.87  5295.1  433.43  5300.9  431.51  5301.4  430.71  5306.9  431.51
  5335.3  433.15  5336.9  433.43  5349.1  436.63  5371.7  439.06  5530.4  449.18
#Mann=5,-1,0
  4648.3    0.16       0  4770.5    0.05       0  5300.9   0.035       0
  5306.9    0.05       0  5335.3    0.16       0
Bank Sta=5295.1,5336.9
Exp/Cntr=0.3,0.1

Type RM Length L Ch R = 1,20276,283,283,283
BEGIN DESCRIPTION:
WILLIAMS CREEK 25.0
END DESCRIPTION:
XS GIS Cut Line= 4
      2844221.52      6993073.58      2844446.10      6993065.98
      2844614.28      6993008.48      2845066.72      6992744.82
#Sta/Elev= 30
  4662.5  447.19  4816.1  442.24  4844.5  439.84  4884.2  429.63  4892.7  428.84
  4914.7  427.27  4915.2  426.47  4920.7  427.27  5055.0  427.62  5072.9  428.84
  5098.2  431.26  5112.1  430.46  5135.2  434.04  5153.5  434.61  5258.6  437.86
  5301.7  437.97  5338.9  441.21  5354.6  438.77  5366.7  434.43  5381.9  434.20
  5403.4  437.03  5413.0  437.28  5419.1  435.86  5424.9  438.03  5434.8  435.94
  5440.6  437.85  5447.7  436.84  5462.1  440.47  5483.6  442.42  5588.6  449.41
#Mann=5,-1,0
  4662.5    0.16       0  4844.5    0.05       0  4914.7   0.035       0
  4920.7    0.05       0  5153.5    0.16       0
Bank Sta=4892.7,5072.9
Exp/Cntr=0.3,0.1

Type RM Length L Ch R = 1,19993,316,316,316
BEGIN DESCRIPTION:
WILLIAMS CREEK 24.0
END DESCRIPTION:
XS GIS Cut Line= 3
      2844164.68      6993141.36      2844518.41      6993293.27
      2844951.22      6993265.14
#Sta/Elev= 30
  4547.9  443.49  4567.2  443.98  4572.6  442.60  4590.7  443.18  4596.2  441.74
  4643.3  440.79  4648.7  439.63  4666.8  439.26  4672.3  438.31  4695.8  437.54
  4701.3  436.66  4719.4  436.06  4724.8  435.27  4795.5  431.78  4819.1  431.93
  4824.5  430.83  4853.5  429.25  4968.2  426.32  4983.9  425.66  4996.6  423.92
  4997.1  423.12  5002.1  423.12  5002.6  423.92  5022.3  426.32  5049.7  428.01
  5087.6  429.31  5190.0  434.93  5288.4  442.08  5360.4  445.94  5366.6  446.80
#Mann=4,-1,0
  4547.9    0.08       0  4996.6    0.07       0  5002.6    0.08       0
  5087.6    0.08       0
Bank Sta=4968.2,5022.3
Exp/Cntr=0.3,0.1

Type RM Length L Ch R = 1,19677,369,369,369
BEGIN DESCRIPTION:
Mapping XS 6fb33872
END DESCRIPTION:
XS GIS Cut Line= 3
      2844080.08      6993642.66      2844522.75      6993627.47
      2844987.19      6993408.27
#Sta/Elev= 30
  4484.1  439.65  4509.0  439.53  4562.9  436.30  4759.2  428.37  4839.2  427.29
  4848.8  426.77  4853.7  424.98  4859.2  423.53  4925.7  423.72  4927.3  423.72
  4939.8  424.72  4973.7  424.14  4990.9  422.97  4993.3  420.38  4993.8  419.58
  4998.9  419.58  4999.4  420.38  5013.6  423.14  5029.0  422.85  5076.3  424.98
  5117.5  429.64  5150.3  431.82  5161.7  430.68  5178.6  433.29  5184.1  432.27
  5217.4  433.93  5292.4  438.86  5406.1  443.34  5436.2  445.43  5440.6  445.31
#Mann=8,-1,0
  4484.1    0.05       0  4925.7    0.16       0  4927.3    0.05       0
  4993.3    0.03       0  4999.4    0.05       0  5217.4    0.08       0
  5406.1     0.1       0  5436.2    0.08       0
Bank Sta=4853.7,5076.3
Exp/Cntr=0.3,0.1

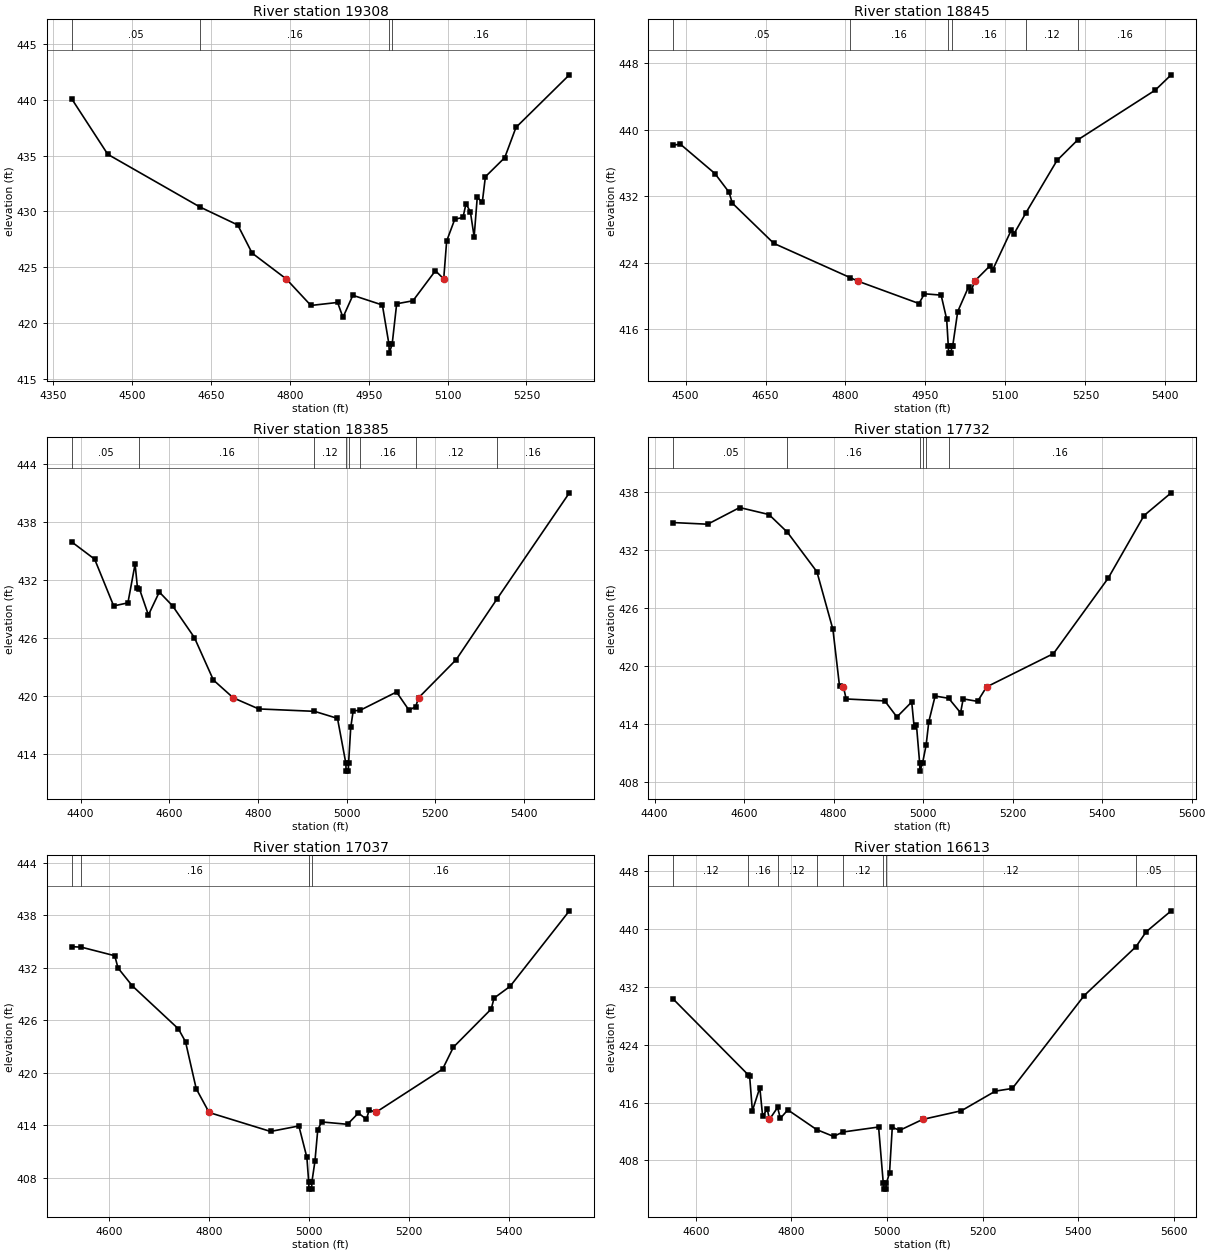
Type RM Length L Ch R = 1,19308,463,463,463
BEGIN DESCRIPTION:
WILLIAMS CREEK 23.0
END DESCRIPTION:
XS GIS Cut Line= 3
      2844197.25      6994007.24      2844724.57      6993909.59
      2845076.16      6993696.90
#Sta/Elev= 30
  4384.5  440.10  4453.4  435.11  4628.8  430.39  4700.7  428.78  4728.0  426.26
  4792.9  423.95  4839.9  421.57  4890.7  421.84  4900.9  420.50  4919.7  422.48
  4975.9  421.61  4988.4  418.10  4988.9  417.30  4994.5  418.10  5003.1  421.72
  5034.1  421.99  5076.8  424.68  5092.6  423.95  5098.2  427.34  5113.7  429.30
  5129.2  429.45  5135.0  430.67  5143.3  429.97  5150.5  427.72  5156.4  431.25
  5166.0  430.81  5171.9  433.10  5208.7  434.81  5230.1  437.52  5331.7  442.23
#Mann=4,-1,0
  4384.5    0.05       0  4628.8    0.16       0  4988.4    0.07       0
  4994.5    0.16       0
Bank Sta=4792.9,5092.6
Exp/Cntr=0.3,0.1

Type RM Length L Ch R = 1,18845,460,460,460
BEGIN DESCRIPTION:
WILLIAMS CREEK 22.0
END DESCRIPTION:
XS GIS Cut Line= 3
      2844375.15      6994413.07      2844835.25      6994269.83
      2845271.84      6994153.12
#Sta/Elev= 30
  4477.1  438.13  4490.0  438.27  4555.1  434.72  4581.7  432.46  4587.6  431.17
  4665.5  426.32  4809.0  422.19  4823.7  421.76  4937.8  419.08  4948.2  420.25
  4979.4  420.09  4989.8  417.20  4992.9  413.91  4993.4  413.11  4998.5  413.11
  4999.0  413.91  5001.2  414.00  5010.5  418.11  5030.9  421.09  5036.1  420.63
  5042.1  421.76  5070.9  423.61  5076.1  423.13  5111.0  427.91  5116.2  427.48
  5138.8  430.03  5196.8  436.30  5235.6  438.77  5381.1  444.76  5410.9  446.60
#Mann=6,-1,0
  4477.1    0.05       0  4809.0    0.16       0  4992.9    0.07       0
  4999.0    0.16       0  5138.8    0.12       0  5235.6    0.16       0
Bank Sta=4823.7,5042.1
Exp/Cntr=0.3,0.1

Type RM Length L Ch R = 1,18385,653,653,653
BEGIN DESCRIPTION:
WILLIAMS CREEK 21.0
END DESCRIPTION:
XS GIS Cut Line= 4
      2844466.33      6994901.34      2844969.79      6994708.20
      2845123.87      6994638.76      2845405.96      6994334.97
#Sta/Elev= 30
  4379.5  435.95  4431.6  434.15  4474.5  429.31  4506.6  429.63  4522.8  433.65
  4528.1  431.20  4532.5  431.09  4552.8  428.37  4577.4  430.75  4607.5  429.31
  4656.5  426.04  4699.4  421.64  4744.1  419.80  4801.6  418.65  4927.4  418.40
  4979.3  417.67  4998.2  413.01  4998.7  412.21  5003.8  412.21  5004.3  413.01
  5009.2  416.75  5014.7  418.44  5030.9  418.52  5112.4  420.40  5140.7  418.51
  5155.8  418.90  5162.1  419.80  5246.8  423.74  5338.6  430.00  5502.3  441.02
#Mann=8,-1,0
  4379.5    0.05       0  4532.5    0.16       0  4927.4    0.12       0
  4998.2    0.07       0  5004.3    0.12       0  5030.9    0.16       0
  5155.8    0.12       0  5338.6    0.16       0
Bank Sta=4744.1,5162.1
Exp/Cntr=0.3,0.1

Type RM Length L Ch R = 1,17732,695,695,695
BEGIN DESCRIPTION:
WILLIAMS CREEK 20.0
END DESCRIPTION:
XS GIS Cut Line= 3
      2844995.83      6995402.65      2845295.05      6994975.95
      2845467.20      6994410.43
#Sta/Elev= 30
  4441.9  434.83  4518.6  434.66  4590.1  436.38  4655.5  435.66  4696.7  433.83
  4762.7  429.75  4798.4  423.81  4813.2  417.95  4822.0  417.86  4828.0  416.62
  4914.3  416.42  4941.4  414.76  4974.5  416.31  4979.9  413.73  4985.1  413.92
  4992.3  409.97  4992.8  409.17  4998.6  409.97  5006.7  411.86  5012.7  414.28
  5026.8  416.92  5057.1  416.69  5083.7  415.19  5089.5  416.63  5121.7  416.37
  5141.7  417.86  5291.2  421.30  5413.5  429.09  5493.5  435.55  5554.2  437.90
#Mann=6,-1,0
  4441.9    0.05       0  4696.7    0.16       0  4992.3    0.07       0
  4998.6    0.16       0  5006.7    0.12       0  5057.1    0.16       0
Bank Sta=4822,5141.7
Exp/Cntr=0.3,0.1

Type RM Length L Ch R = 1,17037,424,424,424
BEGIN DESCRIPTION:
WILLIAMS CREEK 19.0
END DESCRIPTION:
XS GIS Cut Line= 3
      2845352.62      6995674.33      2845625.73      6995355.79
      2845904.71      6994851.39
#Sta/Elev= 30
  4524.4  434.42  4544.1  434.36  4610.8  433.38  4617.4  431.97  4646.0  429.93
  4738.2  425.01  4752.4  423.54  4773.8  418.16  4799.6  415.44  4922.5  413.27
  4979.2  413.90  4995.2  410.30  4998.9  407.47  4999.4  406.67  5004.7  406.67
  5005.2  407.47  5011.3  409.84  5017.0  413.47  5024.9  414.36  5076.5  414.09
  5098.3  415.38  5114.3  414.66  5120.1  415.76  5132.7  415.44  5266.7  420.40
  5288.4  422.92  5364.0  427.28  5369.7  428.53  5401.8  429.88  5520.4  438.52
#Mann=4,-1,0
  4524.4    0.05       0  4544.1    0.16       0  4998.9    0.07       0
  5005.2    0.16       0
Bank Sta=4799.6,5132.7
Exp/Cntr=0.3,0.1

Type RM Length L Ch R = 1,16613,418,418,418
BEGIN DESCRIPTION:
WILLIAMS CREEK 18.0
END DESCRIPTION:
XS GIS Cut Line= 3
      2845555.36      6995832.66      2846011.07      6995563.57
      2846423.24      6995259.87
#Sta/Elev= 30
  4553.1  430.28  4709.7  419.83  4712.6  419.69  4718.4  414.87  4734.0  418.05
  4739.8  414.14  4749.6  415.08  4754.1  413.67  4771.1  415.32  4776.9  413.82
  4792.5  414.99  4852.7  412.27  4888.2  411.32  4907.8  411.93  4982.4  412.62
  4992.2  404.84  4992.7  404.04  4998.0  404.04  4998.5  404.84  5005.2  406.24
  5011.0  412.57  5026.7  412.17  5074.5  413.67  5155.6  414.87  5226.6  417.58
  5262.1  417.95  5412.5  430.79  5520.9  437.55  5542.0  439.59  5594.3  442.49
#Mann=8,-1,0
  4553.1    0.12       0  4709.7    0.16       0  4771.1    0.12       0
  4852.7    0.16       0  4907.8    0.12       0  4992.2    0.07       0
  4998.5    0.12       0  5520.9    0.05       0
Bank Sta=4754.1,5074.5
Exp/Cntr=0.3,0.1