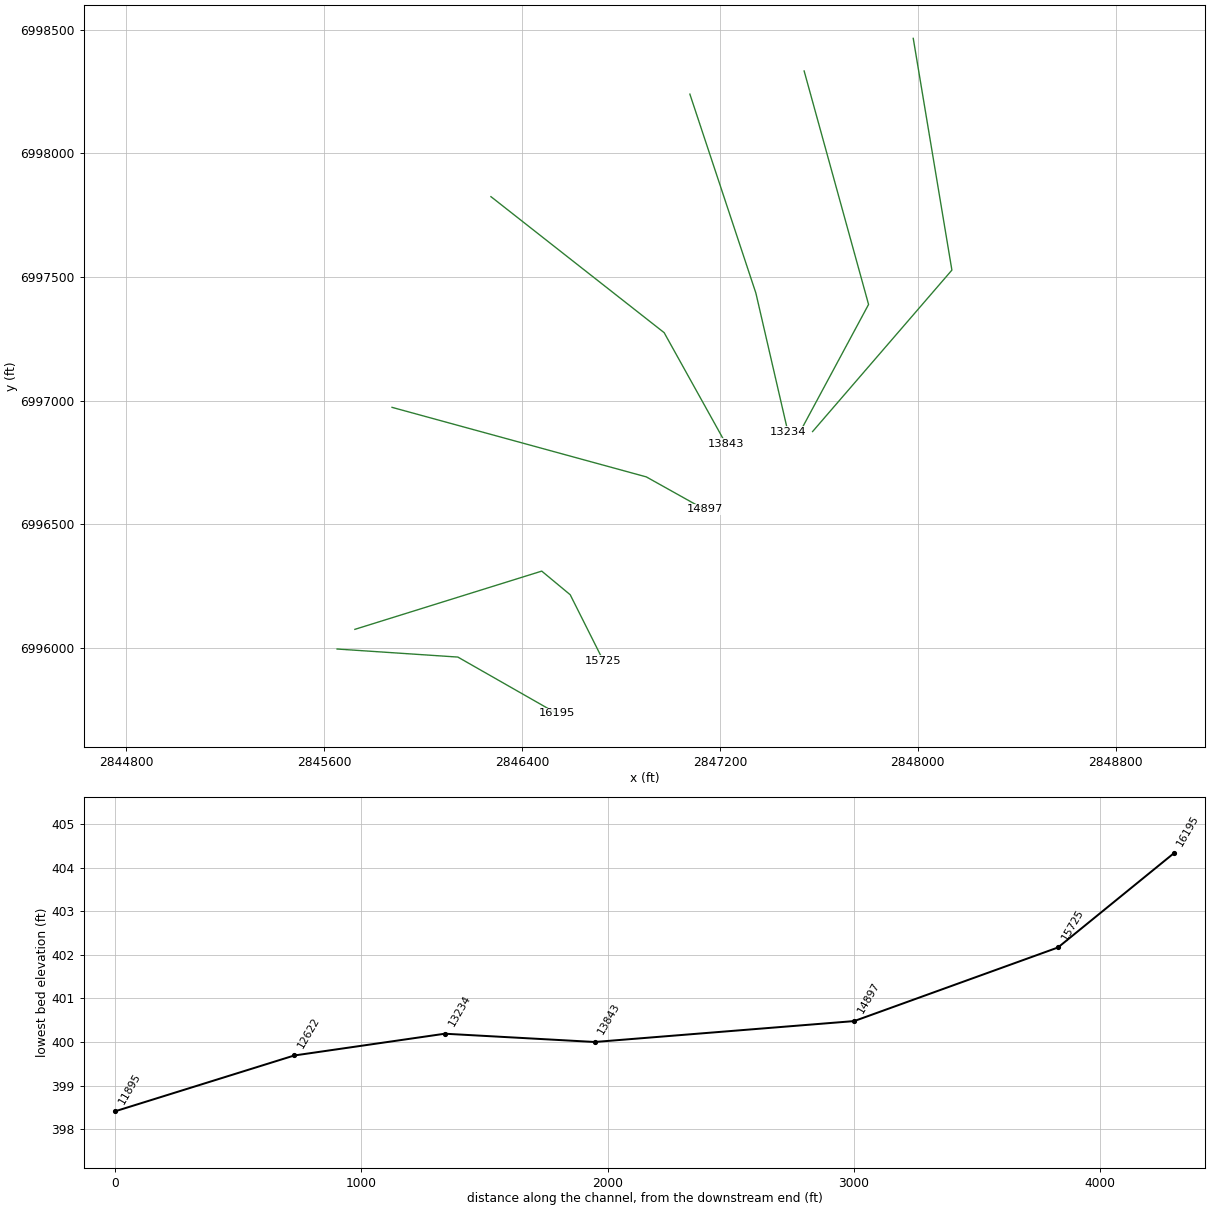
HEC-RAS study WILLIAMS CREEK.prj: WILLIAMS CREEK Base Level Engineering

--- WILLIAMS CREEK.g01 (geometry) --- (continued)

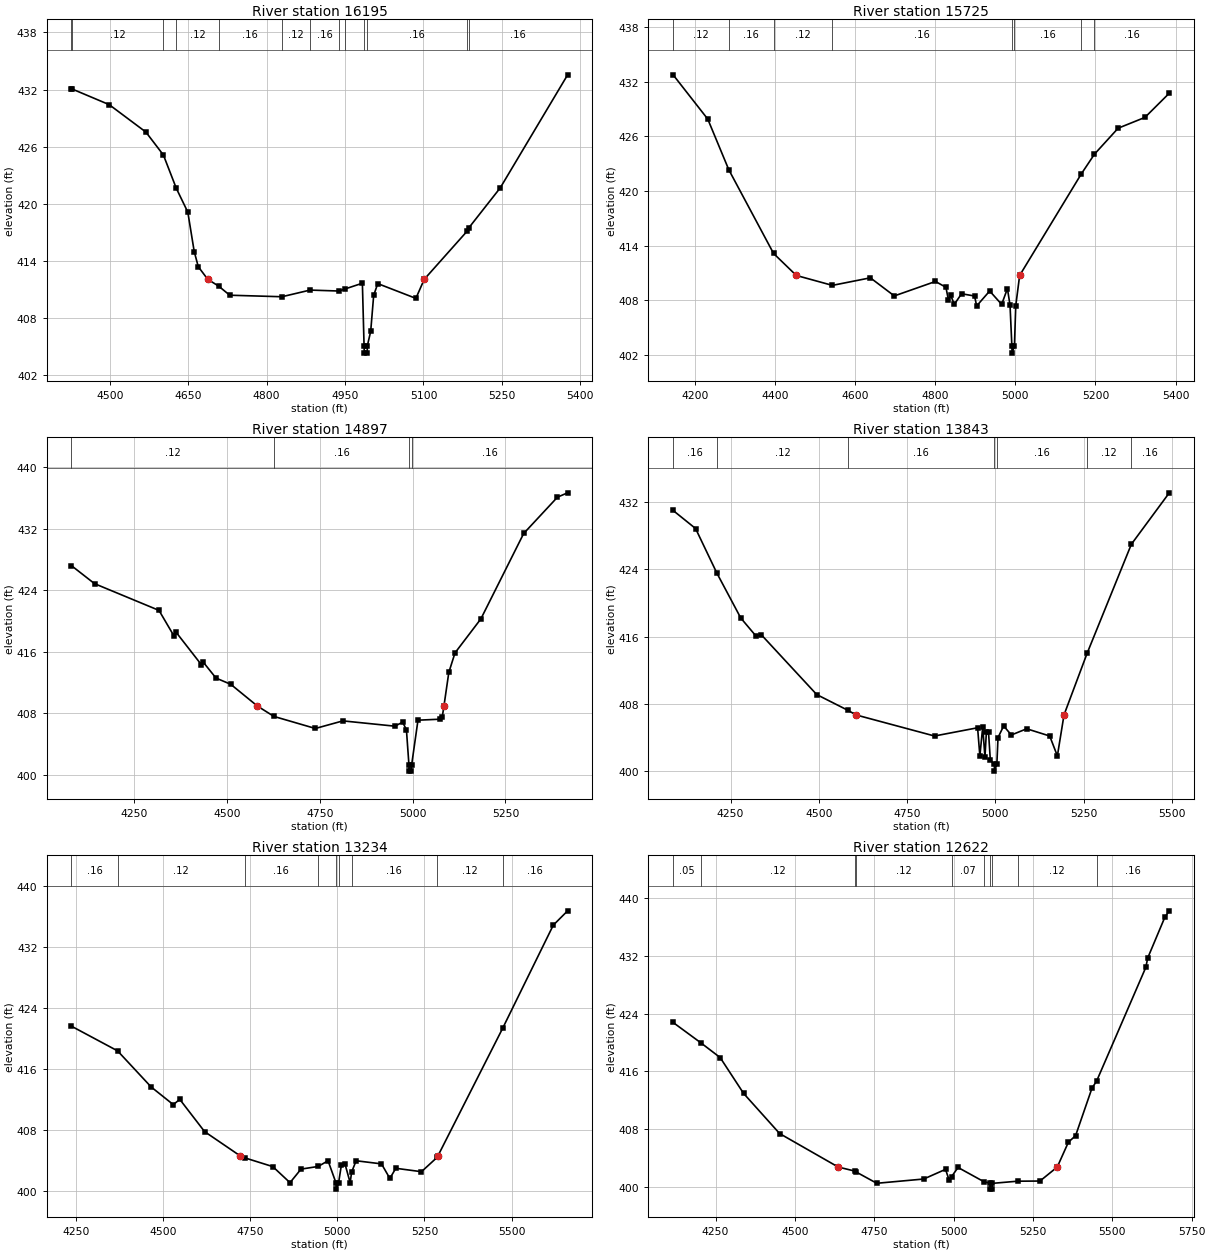
Type RM Length L Ch R = 1,16195,470,470,470
BEGIN DESCRIPTION:
Mapping XS 4cac6315
END DESCRIPTION:
XS GIS Cut Line= 3
      2845653.02      6995995.42      2846141.28      6995962.87
      2846540.33      6995735.15
#Sta/Elev= 30
  4426.9  432.05  4428.6  432.05  4499.0  430.42  4569.2  427.54  4602.7  425.13
  4627.4  421.63  4649.4  419.13  4661.6  415.00  4669.4  413.40  4687.5  412.08
  4708.2  411.37  4729.6  410.41  4829.3  410.25  4883.2  410.95  4938.4  410.85
  4949.6  411.06  4983.2  411.67  4986.4  405.13  4986.9  404.33  4992.3  404.33
  4992.8  405.13  4999.1  406.62  5004.8  410.40  5012.6  411.63  5085.5  410.08
  5101.5  412.08  5183.9  417.16  5186.7  417.48  5246.8  421.68  5375.7  433.55
#Mann=13,-1,0
  4426.9    0.16       0  4428.6    0.12       0  4602.7    0.16       0
  4627.4    0.12       0  4708.2    0.16       0  4829.3    0.12       0
  4883.2    0.16       0  4938.4    0.12       0  4949.6    0.16       0
  4986.4    0.07       0  4992.8    0.16       0  5183.9    0.12       0
  5186.7    0.16       0
Bank Sta=4687.5,5101.5
Exp/Cntr=0.3,0.1

Type RM Length L Ch R = 1,15725,828,828,828
BEGIN DESCRIPTION:
WILLIAMS CREEK 17.0
END DESCRIPTION:
XS GIS Cut Line= 4
      2845725.00      6996075.00      2846480.25      6996310.53
      2846595.27      6996215.04      2846728.79      6995948.87
#Sta/Elev= 30
  4145.9  432.77  4232.4  427.90  4284.9  422.33  4396.6  413.13  4453.4  410.71
  4543.4  409.62  4638.2  410.45  4698.0  408.46  4800.7  410.05  4826.8  409.41
  4833.2  407.98  4838.5  408.56  4847.7  407.53  4865.8  408.70  4898.3  408.45
  4903.5  407.36  4936.0  409.00  4965.9  407.53  4980.3  409.26  4986.8  407.45
  4991.4  402.97  4991.9  402.17  4997.8  402.97  5001.1  407.38  5010.8  410.71
  5164.5  421.86  5197.6  424.05  5256.6  426.90  5323.6  428.09  5384.3  430.75
#Mann=8,-1,0
  4145.9    0.12       0  4284.9    0.16       0  4396.6    0.12       0
  4543.4    0.16       0  4991.4    0.07       0  4997.8    0.16       0
  5164.5    0.12       0  5197.6    0.16       0
Bank Sta=4453.4,5010.8
Exp/Cntr=0.3,0.1

Type RM Length L Ch R = 1,14897,1054,1054,1054
BEGIN DESCRIPTION:
WILLIAMS CREEK 16.0
END DESCRIPTION:
XS GIS Cut Line= 3
      2845875.24      6996972.85      2846903.00      6996691.61
      2847138.83      6996559.82
#Sta/Elev= 30
  4081.6  427.22  4143.6  424.88  4317.2  421.40  4356.8  418.13  4362.0  418.63
  4431.0  414.35  4436.2  414.67  4470.7  412.59  4510.4  411.78  4582.1  408.95
  4626.6  407.60  4738.1  406.03  4812.3  407.02  4952.2  406.33  4973.0  406.85
  4983.3  405.87  4990.1  401.28  4990.7  400.48  4996.8  400.48  4997.3  401.28
  5014.4  407.11  5074.5  407.24  5079.6  407.49  5084.3  408.95  5097.4  413.32
  5114.1  415.87  5183.8  420.30  5299.0  431.41  5390.0  436.14  5417.3  436.70
#Mann=4,-1,0
  4081.6    0.12       0  4626.6    0.16       0  4990.1    0.07       0
  4997.3    0.16       0
Bank Sta=4582.1,5084.3
Exp/Cntr=0.3,0.1

Type RM Length L Ch R = 1,13843,609,609,609
BEGIN DESCRIPTION:
WILLIAMS CREEK 15.0
END DESCRIPTION:
XS GIS Cut Line= 3
      2846274.99      6997825.01      2846975.00      6997275.00
      2847224.99      6996825.02
#Sta/Elev= 30
  4087.3  431.02  4150.9  428.87  4211.5  423.54  4278.9  418.22  4322.3  416.06
  4336.8  416.24  4494.0  409.11  4582.6  407.23  4605.1  406.69  4827.5  404.18
  4949.5  405.16  4955.9  401.81  4964.0  405.25  4970.3  401.66  4974.4  404.66
  4980.4  404.66  4985.5  401.35  4996.8  400.80  4997.3  400.00  5004.0  400.80
  5007.3  403.99  5023.3  405.38  5045.0  404.30  5088.5  405.04  5153.7  404.18
  5175.4  401.81  5194.2  406.69  5259.4  414.00  5384.9  427.00  5492.3  433.12
#Mann=7,-1,0
  4087.3    0.16       0  4211.5    0.12       0  4582.6    0.16       0
  4996.8    0.07       0  5004.0    0.16       0  5259.4    0.12       0
  5384.9    0.16       0
Bank Sta=4605.1,5194.2
Exp/Cntr=0.3,0.1

Type RM Length L Ch R = 1,13234,612,612,612
BEGIN DESCRIPTION:
WILLIAMS CREEK 14.0
END DESCRIPTION:
XS GIS Cut Line= 3
      2847079.00      6998239.69      2847345.81      6997434.83
      2847475.01      6996874.98
#Sta/Elev= 30
  4238.1  421.61  4370.2  418.37  4466.6  413.62  4530.0  411.30  4548.6  411.99
  4619.8  407.75  4722.5  404.54  4734.5  404.31  4815.3  403.15  4864.6  401.04
  4896.2  402.82  4945.2  403.17  4973.7  403.92  4996.6  400.99  4997.1  400.19
  5003.8  400.99  5012.1  403.40  5022.6  403.45  5037.1  401.03  5041.3  402.43
  5054.2  403.92  5126.9  403.51  5150.9  401.60  5168.0  402.93  5241.5  402.48
  5286.0  404.35  5288.5  404.54  5474.1  421.32  5619.5  434.90  5660.6  436.78
#Mann=9,-1,0
  4238.1    0.16       0  4370.2    0.12       0  4734.5    0.16       0
  4945.2    0.12       0  4996.6    0.07       0  5003.8    0.12       0
  5041.3    0.16       0  5286.0    0.12       0  5474.1    0.16       0
Bank Sta=4722.5,5288.5
Exp/Cntr=0.3,0.1

Type RM Length L Ch R = 1,12622,727,727,727
BEGIN DESCRIPTION:
WILLIAMS CREEK 13.0
END DESCRIPTION:
XS GIS Cut Line= 3
      2847540.79      6998333.51      2847801.22      6997389.02
      2847524.98      6996874.97
#Sta/Elev= 30
  4116.2  422.78  4203.6  419.96  4264.4  417.92  4338.3  412.95  4451.8  407.39
  4636.4  402.75  4689.6  402.18  4691.1  402.11  4757.9  400.50  4905.7  401.09
  4974.5  402.43  4986.0  400.93  4993.6  401.43  5014.0  402.69  5094.5  400.74
  5114.9  400.49  5115.4  399.69  5121.7  399.69  5122.3  400.49  5201.6  400.79
  5272.0  400.81  5326.5  402.75  5361.6  406.19  5384.3  407.10  5436.0  413.69
  5450.5  414.66  5605.6  430.42  5611.4  431.70  5665.7  437.38  5679.5  438.25
#Mann=10,-1,0
  4116.2    0.05       0  4203.6    0.12       0  4689.6    0.16       0
  4691.1    0.12       0  4993.6    0.07       0  5094.5    0.05       0
  5114.9    0.07       0  5122.3    0.05       0  5201.6    0.12       0
  5450.5    0.16       0
Bank Sta=4636.4,5326.5
Exp/Cntr=0.3,0.1

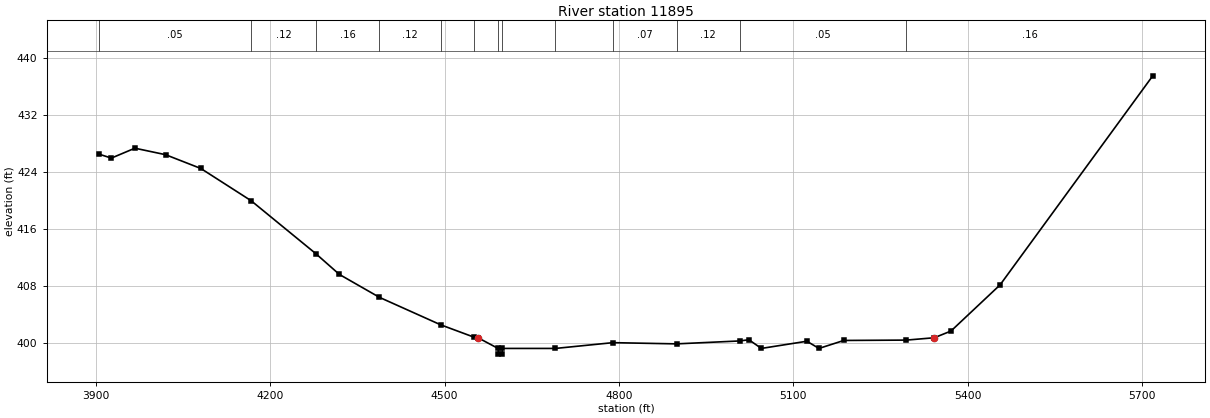
Type RM Length L Ch R = 1,11895,0,0,0
BEGIN DESCRIPTION:
WILLIAMS CREEK 12.0
END DESCRIPTION:
XS GIS Cut Line= 3
      2847981.78      6998465.38      2848138.02      6997527.91
      2847575.03      6996875.03
#Sta/Elev= 30
  3906.1  426.47  3926.8  425.93  3967.3  427.32  4020.0  426.41  4080.8  424.47
  4167.2  419.95  4278.5  412.52  4319.1  409.60  4388.1  406.38  4493.3  402.53
  4550.1  400.81  4557.6  400.71  4592.2  399.21  4592.7  398.41  4599.0  398.41
  4599.6  399.21  4690.9  399.21  4789.7  400.02  4899.2  399.85  5007.9  400.26
  5023.7  400.43  5045.2  399.21  5123.5  400.22  5144.3  399.21  5187.1  400.33
  5294.9  400.38  5342.7  400.71  5371.4  401.65  5455.9  408.13  5718.6  437.48
#Mann=13,-1,0
  3906.1    0.05       0  4167.2    0.12       0  4278.5    0.16       0
  4388.1    0.12       0  4493.3    0.16       0  4550.1    0.05       0
  4592.2    0.07       0  4599.6    0.05       0  4690.9    0.12       0
  4789.7    0.07       0  4899.2    0.12       0  5007.9    0.05       0
  5294.9    0.16       0
Bank Sta=4557.6,5342.7
Exp/Cntr=0.3,0.1

Chan Stop Cuts=-1